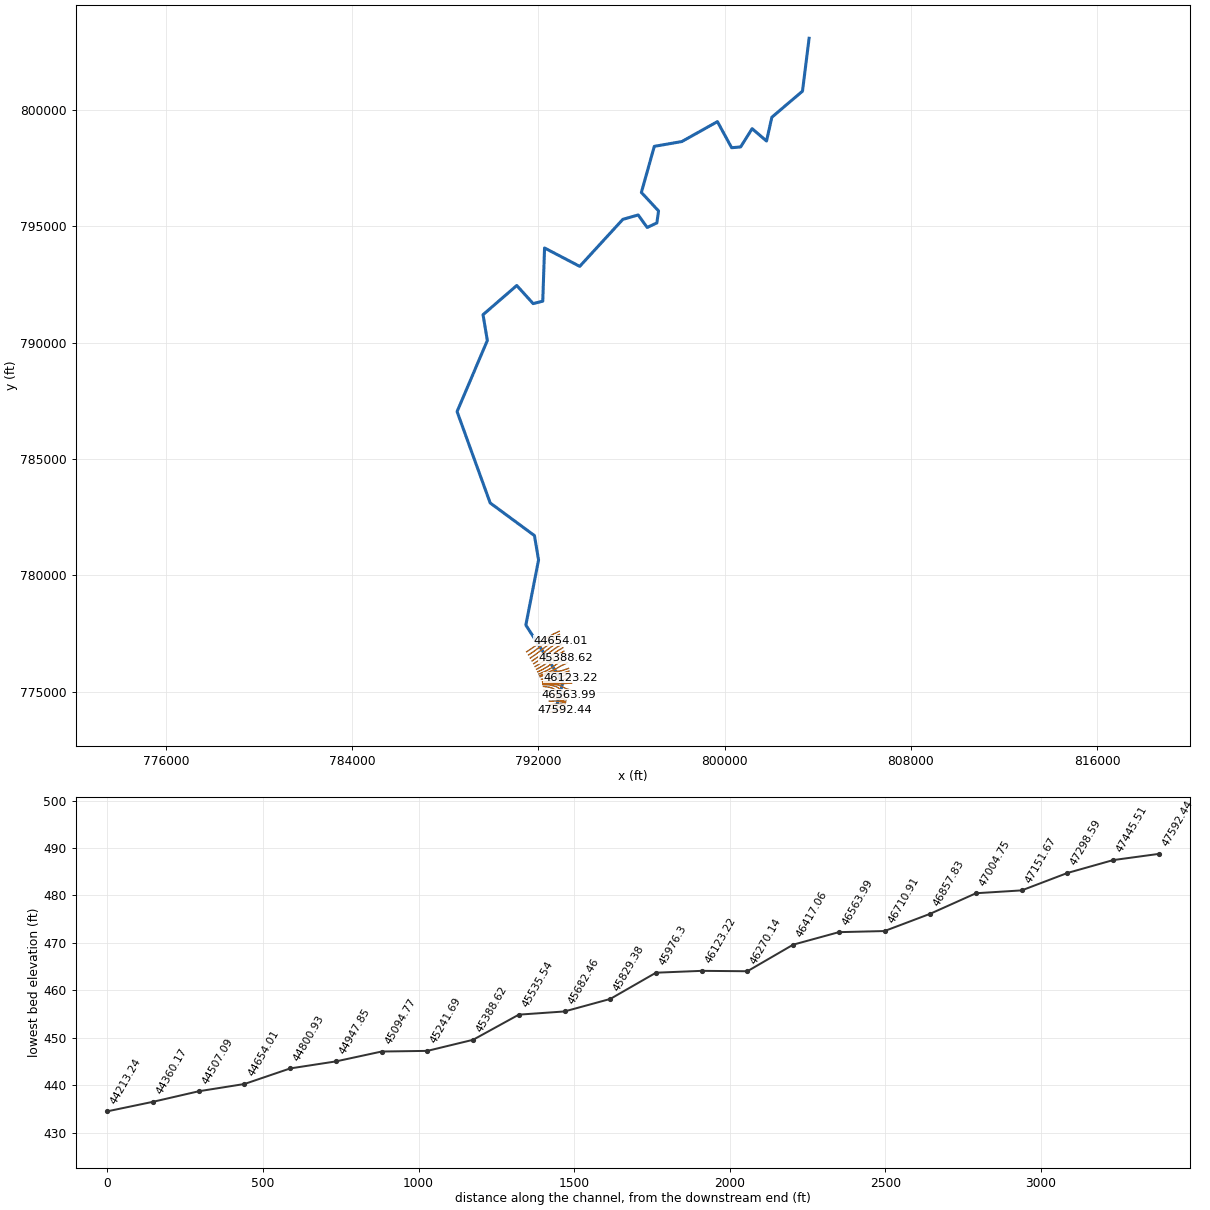
--- 17465_ras.prj (project) ---

Proj Title=17465
Current Plan=p01
Default Exp/Contr=0.3,0.1
English Units
Geom File=g01
Flow File=f01
Plan File=p01
Y Axis Title=Elevation
X Axis Title(PF)=Main Channel Distance
X Axis Title(XS)=Station
BEGIN DESCRIPTION:
RFD model 17465 exported to HEC-RAS
END DESCRIPTION:

--- 17465_ras.p01 (plan) ---

Plan Title=Plan 01
Program Version=4.10
Short Identifier=Plan 01
Geom File=g01
Flow File=f01
Subcritical Flow
Calc Critical at every XS
Secant Critical Depth

--- 17465_ras.f01 (steady flow) ---

Flow Title=Flow 01
Program Version=5.01
Number of Profiles= 6
Profile Names=10yr,25yr,50yr,100yr,100plus,500yr
River Rch & RM=17465,151,47592.44
 5713.45  9552.413539.5618842.9626933.8538318.08
River Rch & RM=17465,151,47445.51
 5718.37 9560.3913548.96 18854.426950.2138333.85
River Rch & RM=17465,151,47298.59
 5721.26 9565.0813554.4918861.1426959.8338343.12
River Rch & RM=17465,151,47151.67
 5731.98 9582.4713574.9618886.0426995.4238377.41
River Rch & RM=17465,151,47004.75
 5766.44 9638.3813640.7318966.0427109.7838487.48
River Rch & RM=17465,151,46857.83
  5767.6 9640.2613642.9418968.7327113.6238491.17
River Rch & RM=17465,151,46710.91
 5780.92 9661.8813668.3518999.6227157.7838533.63
River Rch & RM=17465,151,46563.99
 5782.95 9665.1713672.2119004.3227164.4938540.08
River Rch & RM=17465,151,46417.06
 5811.92 9712.1613727.4119071.4127260.3938632.21
River Rch & RM=17465,151,46270.14
 5840.61 9758.6913782.0219137.7527355.21 38723.2
River Rch & RM=17465,151,46123.22
  5846.4 9768.0913793.0519151.1427374.3638741.56
River Rch & RM=17465,151, 45976.3
 5853.07  9778.913805.7319166.5427396.3738762.65
River Rch & RM=17465,151,45829.38
 5855.97  9783.613811.2519173.2327405.9338771.83
River Rch & RM=17465,151,45682.46
 5857.71 9786.4213814.5519177.2527411.6738777.32
River Rch & RM=17465,151,45535.54
 5890.76    984013877.3619253.4827520.6438881.69
River Rch & RM=17465,151,45388.62
 5894.23 9845.6513883.97 19261.5 27532.138892.66
River Rch & RM=17465,151,45241.69
 5905.83 9864.4513905.9919288.2227570.2938929.21
River Rch & RM=17465,151,45094.77
 5910.18  9871.513914.2519298.2427584.6138942.91
River Rch & RM=17465,151,44947.85
 5932.22 9907.2313956.0719348.9627657.1139012.22
River Rch & RM=17465,151,44800.93
 5951.07 9937.7913991.83 19392.327719.0739071.41
River Rch & RM=17465,151,44654.01
 5964.13 9958.9514016.5719422.2927761.9439112.33
River Rch & RM=17465,151,44507.09
 5970.51 9969.2914028.6619436.9527782.8839132.32
River Rch & RM=17465,151,44360.17
 5973.99 9974.9314035.2619444.94 27794.339143.22
River Rch & RM=17465,151,44213.24
 5979.21 9983.3914045.1519456.9227811.4439159.57
River Rch & RM=17465,151,44066.32
  5985.6 9993.7414057.2419471.5727832.3739179.53
River Rch & RM=17465,151, 43919.4
 5987.63 9997.0314061.0819476.2327839.0339185.88
River Rch & RM=17465,151,43772.48
 5991.1110002.6714067.6819484.2127850.4539196.77
River Rch & RM=17465,151,43625.56
 5994.5910008.3214074.27 19492.227861.8639207.65
River Rch & RM=17465,151,43390.91
 6244.3710412.8414545.2620061.5128675.6239979.87
River Rch & RM=17465,151,43197.83
 6247.5710418.0214551.2620068.7528685.9839989.65
River Rch & RM=17465,151,43048.36
 6262.6810442.4914579.6520102.9928734.9140035.86
River Rch & RM=17465,151,42898.88
  6265.310446.7214584.5620108.9128743.3840043.85
River Rch & RM=17465,151,42749.41
 6281.5810473.0714615.1220145.7528796.0440093.54
River Rch & RM=17465,151,42599.94
 6284.4910477.7814620.5820152.3328805.4440102.41
River Rch & RM=17465,151,42450.47
 6290.8910488.1314632.5720166.7928826.1240121.91
River Rch & RM=17465,151,   42301
 6379.0410630.7414797.6720365.6629110.3740389.52
River Rch & RM=17465,151,42151.53
 6382.8210636.8614804.7520374.1829122.5440400.96
River Rch & RM=17465,151,42002.06
 6389.2210647.2214816.7220388.5929143.1440420.32
River Rch & RM=17465,151,41852.58
 6390.6810649.5714819.4420391.8629147.8240424.72
River Rch & RM=17465,151,41703.11
 6422.9810701.8214879.8220464.5129251.6740522.23
River Rch & RM=17465,151,41553.64
 6434.6310720.6514901.5720490.6729289.0540557.32
River Rch & RM=17465,151,41404.17
 6439.5810728.6614910.8120501.7829304.9440572.22
River Rch & RM=17465,151, 41254.7
 6440.7410730.5414912.9920504.3929308.6840575.72
River Rch & RM=17465,151,41105.23
 6449.19 10744.214928.7520523.3529335.7740601.13
River Rch & RM=17465,151,40955.76
 6450.6410746.5514931.4720526.6129340.4440605.51
River Rch & RM=17465,151,40806.28
 6457.3410757.3814943.9620541.6429361.9140625.64
River Rch & RM=17465,151,40656.81
 6459.3810760.6714947.7720546.2129368.4540631.77
River Rch & RM=17465,151,40507.34
 6477.1410789.39 14980.920586.0429425.3840685.11
River Rch & RM=17465,151,40357.87
 6480.3410794.5714986.8820593.2229435.6440694.73
River Rch & RM=17465,151, 40208.4
 6486.1710803.9914997.7420606.2729454.29 40712.2
River Rch & RM=17465,151, 40111.4
 6492.2810813.8815009.1420619.9729473.8840730.54
River Rch & RM=17465,151,39899.91
 6496.07   10820 15016.220628.45   2948640741.88
River Rch & RM=17465,151,39758.22
 6497.5310822.3515018.9120631.7129490.6640746.24
River Rch & RM=17465,151, 39609.2
 6500.1510826.59 15023.820637.5829499.05 40754.1
River Rch & RM=17465,151,39460.19
  6501.610828.9515026.5120640.8429503.7140758.46
River Rch & RM=17465,151,39311.17
 6503.6410832.2415030.3120645.4129510.2440764.57
River Rch & RM=17465,151,39162.15
 6515.2910851.0815052.0220671.4829547.5140799.44
River Rch & RM=17465,151,38864.12
 6517.3310854.3715055.8220676.0429554.0340805.54
River Rch & RM=17465,151,38715.11
 8430.5513935.0118528.5724791.3835436.4346145.38
River Rch & RM=17465,151,38566.09
 8435.5613943.0518537.4624801.7835451.2946158.48
River Rch & RM=17465,151,38417.08
 8436.15   13944 18538.5   2480335453.0446160.02
River Rch & RM=17465,151,38268.06
 8778.1714492.39 19142.225507.9836460.7247044.88
River Rch & RM=17465,151,38119.05
 8779.6514494.7619144.79   2551136465.0547048.66
River Rch & RM=17465,151,37970.03
 8782.0114498.5419148.9525515.8436471.9747054.71
River Rch & RM=17465,151,37821.01
 8784.9714503.2819154.14 25521.936480.6347062.27
River Rch & RM=17465,151,   37672
 8786.1514505.1719156.2225524.3236484.0847065.29
River Rch & RM=17465,151,37373.97
 8818.0514556.2919212.2925589.6436577.4647146.87
River Rch & RM=17465,151,37224.95
 8877.7414651.9219317.0825711.6736751.8947299.07
River Rch & RM=17465,151,36926.92
 8955.1814775.9619452.8425869.6436977.6947495.76
River Rch & RM=17465,151, 36777.9
 8956.3714777.8619454.9225872.0636981.1347498.76
River Rch & RM=17465,151,36628.89
  8961.114785.43 19463.225881.69 36994.947510.74
River Rch & RM=17465,151,36479.87
 8965.2414792.0619470.4525890.1237006.9647521.23
River Rch & RM=17465,151,36330.86
 9020.8314881.0819567.7426003.2337168.6447661.79
River Rch & RM=17465,151,36181.84
 9024.3814886.7619573.9526010.4537178.9547670.75
River Rch & RM=17465,151,36032.83
 9026.15 14889.619577.0526014.0637184.1147675.22
River Rch & RM=17465,151,35883.81
 9027.9314892.4519580.1626017.6637189.26 47679.7
River Rch & RM=17465,151, 35734.8
 9030.2914896.2319584.2926022.4737196.1347685.67
River Rch & RM=17465,151,35585.78
 9034.1414902.3919591.0226030.29 37207.347695.37
River Rch & RM=17465,151,35436.76
 9035.6214904.7619593.6126033.29 37211.647699.11
River Rch & RM=17465,151,35287.75
 9052.1814931.2819622.5626066.94 37259.747740.86
River Rch & RM=17465,151,35138.73
 9053.9614934.1219625.6626070.5437264.8447745.33
River Rch & RM=17465,151,34989.72
  9057.814940.2819632.3826078.3537276.0147755.02
River Rch & RM=17465,151,34691.69
14023.2922835.4627927.9135493.5250733.9258845.66
River Rch & RM=17465,151,34542.67
14026.6122840.7127933.2435499.4550742.3958852.31
River Rch & RM=17465,151,34393.65
14032.9522850.7327943.4235510.7750758.5658865.02
River Rch & RM=17465,151,34244.64
14035.0722854.0727946.8135514.5450763.9658869.25
River Rch & RM=17465,151,34095.62
14037.4822857.8927950.6935518.8550770.1158874.09
River Rch & RM=17465,151,33946.61
14051.98 22880.827973.9635544.7150807.0858903.13
River Rch & RM=17465,151,33797.59
14128.0723001.0528096.0435680.3451000.9559055.32
River Rch & RM=17465,151,33648.58
14138.3423017.2828112.5135698.6351027.0959075.82
River Rch & RM=17465,151,33499.56
14139.8523019.6728114.9335701.3251030.9459078.83
River Rch & RM=17465,151,33350.54
 14162.823055.9428151.7335742.1851089.3559124.64
River Rch & RM=17465,151,33201.53
14164.3123058.3228154.1535744.8751093.1859127.65
River Rch & RM=17465,151,32924.63
14223.5223151.87   2824935850.17 51243.7 59245.6
River Rch & RM=17465,151,32710.02
14228.6623159.9928257.22 35859.351256.7559255.82
River Rch & RM=17465,151,32247.39
14240.44 23178.628276.0935880.2351286.6859279.26
River Rch & RM=17465,151,31998.54
14245.2723186.2428283.8335888.8251298.9559288.88
River Rch & RM=17465,151, 31749.7
20435.41 32910.937835.7246288.7566164.4670444.52
River Rch & RM=17465,151,31500.86
20459.6932948.8437871.9546327.5266219.8770484.48
River Rch & RM=17465,151,31252.01
20468.2932962.29 37884.846341.2666239.5170498.64
River Rch & RM=17465,151,31003.17
20480.8932981.98 37903.646361.3766268.2670519.38
River Rch & RM=17465,151,30754.33
20486.7332991.1137912.3146370.6966281.5770528.98
River Rch & RM=17465,151,30505.48
20557.4133101.5838017.7546483.4666442.7770645.13
River Rch & RM=17465,151,30256.64
20560.4833106.3938022.3346488.3666449.7770650.18
River Rch & RM=17465,151, 30007.8
20564.1733112.1538027.8346494.2466458.1770656.23
River Rch & RM=17465,151,29758.95
20566.0233115.0338030.5846497.1866462.3870659.26
River Rch & RM=17465,151,29510.11
20567.8633117.9138033.3346500.1266466.5970662.28
River Rch & RM=17465,151,29261.26
20571.24 33123.238038.3746505.5166474.2970667.84
River Rch & RM=17465,151,29012.42
20574.31   3312838042.9546510.4166481.2970672.88
River Rch & RM=17465,151, 28619.2
   2075633411.9138313.6146799.6866894.7770970.37
River Rch & RM=17465,151,28017.05
20778.4433446.9838347.0146835.3666945.7771007.02
River Rch & RM=17465,151,27021.67
20790.1333465.24 38364.446853.9366972.32 71026.1
River Rch & RM=17465,151, 26026.3
20859.6333573.8238467.7846964.3467130.1371139.45
River Rch & RM=17465,151,24579.73
21168.8234056.7538926.8947454.1967830.3271641.31
River Rch & RM=17465,151,23537.86
21199.2934104.3238972.0647502.3667899.1671690.56
River Rch & RM=17465,151,23040.18
21217.7634133.1638999.4447531.5367940.8771720.39
River Rch & RM=17465,151, 21981.8
 22587.336269.6641016.8649675.1171004.8773896.09
River Rch & RM=17465,151,21049.43
22612.9236309.5941054.3849714.8571061.6673936.13
River Rch & RM=17465,151,20551.74
22662.6336387.0541127.1349791.8871171.7874013.73
River Rch & RM=17465,151,20054.05
22680.2336414.4841152.8849819.1571210.7574041.18
River Rch & RM=17465,151,19556.37
22694.1236436.13 41173.249840.6771241.5274062.85
River Rch & RM=17465,151,19058.68
22729.3236490.9841224.6949895.1871319.4374117.71
River Rch & RM=17465,151,18560.99
22750.6336524.1941255.8449928.1671366.57 74150.9
River Rch & RM=17465,151, 18063.3
 22816.1 36626.241351.5550029.4471511.3474252.77
River Rch & RM=17465,151,17565.62
22826.9136643.0441367.3550046.1571535.2374269.58
River Rch & RM=17465,151,17067.93
22834.9436655.5541379.0850058.5771552.9874282.06
River Rch & RM=17465,151,15574.87
24590.7339388.2343926.0552743.1875390.33 76958.2
River Rch & RM=17465,151,14081.81
24649.9339480.2644011.2952832.6975518.2777046.65
River Rch & RM=17465,151,13584.12
24703.5539563.6244088.4852913.7275634.0977126.69
River Rch & RM=17465,151,13086.43
25020.7740056.6344544.4153391.98 76317.777598.29
River Rch & RM=17465,151,12588.75
25117.86 40207.544683.7353538.0176526.4477742.01
River Rch & RM=17465,151, 12181.3
25127.7940222.9244697.9753552.9376547.7677756.69
River Rch & RM=17465,151,11688.08
25138.6440239.7944713.5453569.2476571.0877772.74
River Rch & RM=17465,151, 11527.1
 25140.540242.6844716.2153572.0476575.0877775.49
River Rch & RM=17465,151,11172.47
25148.2640254.7344727.34 53583.776591.7477786.95
River Rch & RM=17465,151,10638.66
25156.6440267.7544739.3553596.2876609.7377799.34
River Rch & RM=17465,151,10187.97
25226.45 40376.244839.4453701.13 76759.677902.41
River Rch & RM=17465,151,9695.725
25286.0340468.7644924.8153790.54 76887.477990.26
River Rch & RM=17465,151,9147.492
25304.0340496.7244950.5953817.5476925.9878016.78
River Rch & RM=17465,151,8542.477
25319.5440520.8244972.8253840.8176959.2678039.63
River Rch & RM=17465,151,7234.487
   2553040847.6945273.9954156.0277409.8178348.88
River Rch & RM=17465,151,6336.082
25545.52 40871.845296.1954179.2477443.0178371.63
River Rch & RM=17465,151,5757.743
25602.96   40961 45378.354265.1377565.7778455.77
River Rch & RM=17465,151,4773.248
27635.4644113.6148261.3857268.7181859.0481372.18
River Rch & RM=17465,151,4105.494
25601.4140958.5945376.08 54262.877562.4578453.51
Boundary for River Rch & Prof#=17465,151,1
Up Type= 0
Dn Type= 2
Boundary for River Rch & Prof#=17465,151,2
Up Type= 0
Dn Type= 2
Boundary for River Rch & Prof#=17465,151,2
Up Type= 0
Dn Type= 2
Boundary for River Rch & Prof#=17465,151,2
Up Type= 0
Dn Type= 2
Boundary for River Rch & Prof#=17465,151,2
Up Type= 0
Dn Type= 2
Boundary for River Rch & Prof#=17465,151,2
Up Type= 0
Dn Type= 2

--- 17465_ras.g01 (geometry) ---

Geom Title=17465
Program Version=4.10

River Reach=17465,151
Reach XY= 30
792724.896251917774168.513958451793050.856053681775407.258573374
791459.792184293777866.489926031792006.406596809780665.957946046
791829.997521042781711.526014779789926.537403048783115.416680155
788505.113788783787039.373861808 789805.47219044790094.523276503
789620.547819763791202.656263468791069.766569766792457.864596806
791774.193653078 791679.21876347792186.954069763791784.687513466
792263.798188955794069.875602563793775.463605731793280.119429819
795626.654643002   795299.094327796286.141685783795489.381504189
796673.933236422794951.354180154797089.662779481795146.924591253
797161.703617155795662.759651807796423.933236423796456.562513493
796979.560428858798436.345448563798164.033919006798643.400995745
799691.566935035799499.206103091800301.537403077798378.437513491
800688.256153049798410.989596811801183.366889328799196.572877238
801801.434688002798665.493063868802030.067634792799687.049964635
803346.756544681800808.628979349803631.231729479803079.926997782

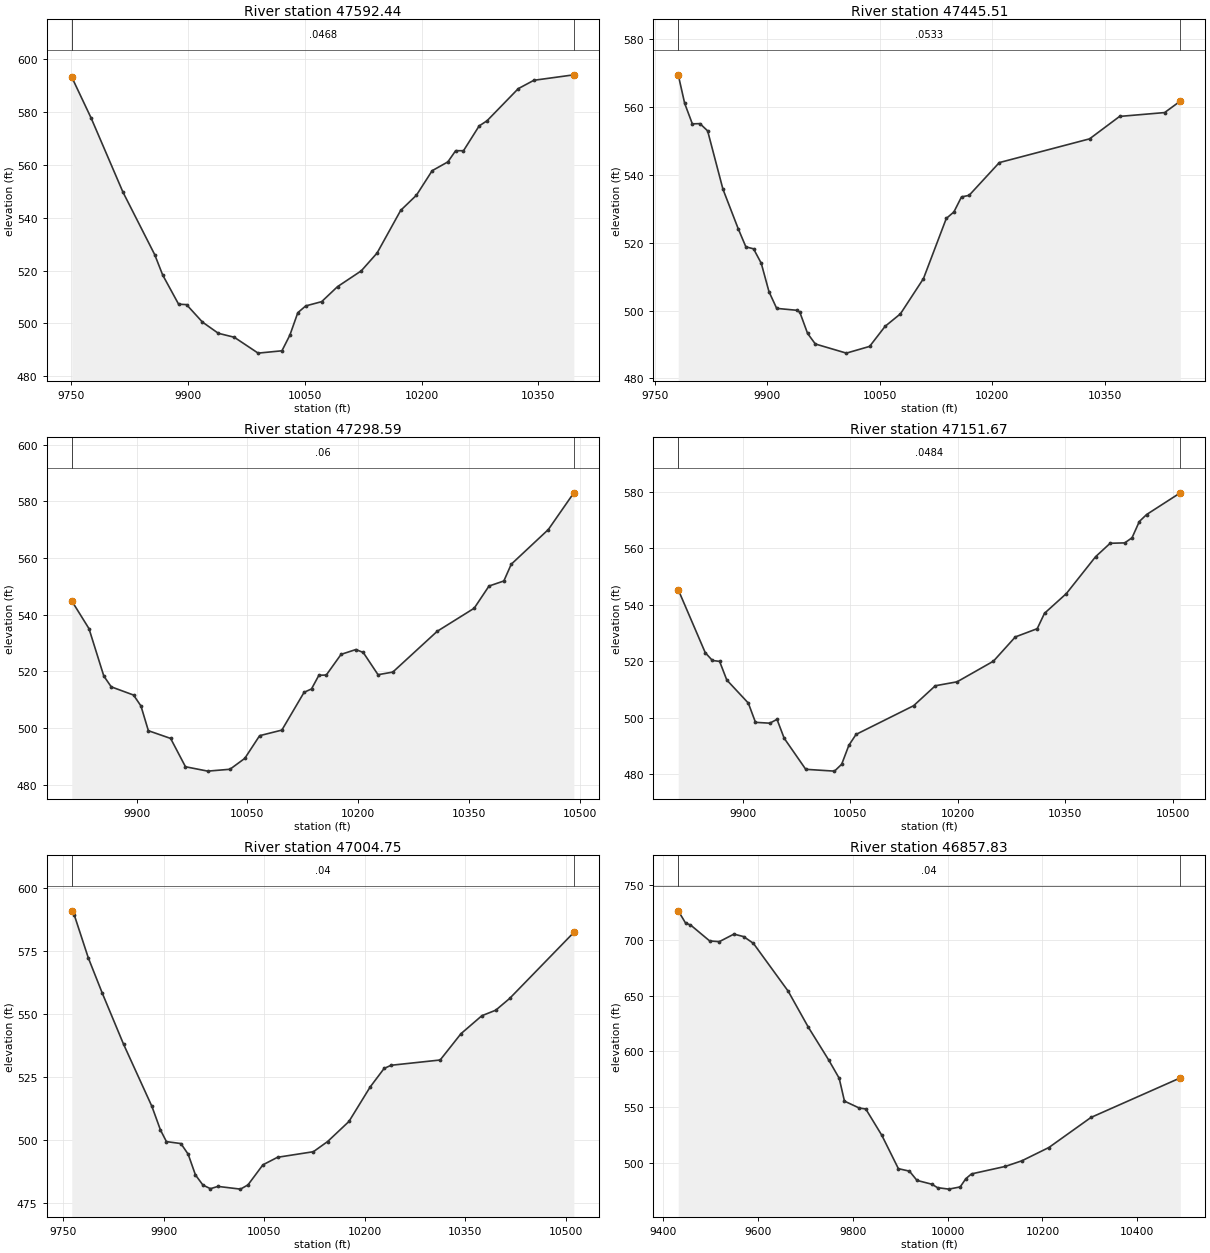
Type RM Length L Ch R = 1 ,47592.44,146.921300,146.921300,146.921300
XS GIS Cut Line= 6
792480.478040637774119.819372528792524.242484889774127.726289897
 792839.08735886774192.130078272 792927.22855277774205.875716107
793021.725801227774216.182926934793116.264764828774221.882362201
#Sta/Elev= 30
9750.779593.14649775.698577.63439816.455549.68929857.314525.99859867.529 518.314
9887.958507.28289898.173507.10439918.602500.50659939.032496.25929959.461494.7716
9990.105488.761810020.71489.645810030.91495.5749 10041.1504.064610051.29506.6231
10071.68508.221810092.07513.9015 10122.6519.883510142.85526.599810173.21542.7487
10193.45548.492210213.64557.758810233.76561.079210243.82565.322910253.88565.3096
   10274574.693210284.06576.622510324.22588.789110344.27591.9461 10395.6594.0136
#Mann= 3 , 0 , 0
9750.779  0.0468       09750.779  0.0468       0 10395.6  0.0468       0
#XS Ineff= 2 , 0
       09901.602                       0
Bank Sta=9750.779,10395.6
Exp/Cntr=0.3,0.1

Type RM Length L Ch R = 1 ,47445.51,146.921300,146.921300,146.921300
XS GIS Cut Line= 6
792476.553040409774263.922952189792566.187181179 774281.50385576
792792.789584739774336.730808779792856.089060132774347.241409711
792986.159350606774358.640590028793135.911188695 774358.51431001
#Sta/Elev= 30
9781.498569.54459790.106561.10759800.297555.08269810.487555.14999820.678553.0119
9841.059535.8303 9861.44524.14749871.631518.80429881.891518.22079892.161513.9477
9902.432505.58889912.702500.65339939.666500.08789943.539499.52159953.881493.2743
9964.222490.152410005.59487.453810036.58489.438910057.18495.353610077.66499.0475
10108.35509.447510138.76527.1811 10148.9529.096310159.03533.532410169.17  533.99
10209.41543.655710329.73550.658810369.74557.276910429.75  558.4110450.66561.7949
#Mann= 3 , 0 , 0
9781.498  0.0533       09781.498  0.0533       010450.66  0.0533       0
#XS Ineff= 2 , 0
       0 9927.71                       0
Bank Sta=9781.498,10450.66
Exp/Cntr=0.3,0.1

Type RM Length L Ch R = 1 ,47298.59,146.921400,146.921400,146.921400
XS GIS Cut Line= 6
792471.808708194774438.107720494792650.382845933774454.868532111
792799.127422387 774466.35671245792907.035794885774468.470487915
793021.941170647774463.436053762793149.347203898774451.955688476
#Sta/Elev= 30
9812.352544.82969835.645535.04649855.733518.30069865.777514.49519895.909 511.605
9905.953 507.7579915.997499.01159946.129496.28129966.217486.28399996.343484.7371
10026.43485.394410046.49489.243310066.55497.250710096.64499.223810126.73512.5621
10136.76513.758910146.77 518.58510156.77 518.66610176.78525.960610196.78527.6625
10206.78526.632110226.79518.781110246.79519.705710306.85534.1029 10356.9542.2494
10376.95550.083210397.03551.871610407.07557.788510457.26570.038110491.77582.9954
#Mann= 3 , 0 , 0
9812.352    0.06       09812.352    0.06       010491.77    0.06       0
#XS Ineff= 2 , 0
       09935.188                       0
Bank Sta=9812.352,10491.77
Exp/Cntr=0.3,0.1

Type RM Length L Ch R = 1 ,47151.67,146.921300,146.921300,146.921300
XS GIS Cut Line= 6
792467.356555326 774601.56533279792554.896313756774598.376441488
792702.400651441 774604.72300841792762.861126875774602.356308649
792881.899090708774585.840132233 793161.20019405774534.387847267
#Sta/Elev= 30
9810.275545.37939847.944523.0538 9857.95520.28439867.957519.97319877.964513.3742
9907.977505.19079917.978498.36319937.979498.0649 9947.98499.4242 9957.98492.7285
9988.052481.709410028.14481.067610038.15483.507210048.17490.225510058.18494.0819
10138.43504.2523 10168.7511.330710199.06512.727910249.77520.051110280.27528.6438
10310.78531.558510320.94537.016710351.45544.021810392.12557.065110412.46561.8377
 10432.8561.978310442.96563.782810453.13569.5501 10463.3572.029510510.28  579.72
#Mann= 3 , 0 , 0
9810.275  0.0484       09810.275  0.0484       010510.28  0.0484       0
#XS Ineff= 2 , 0
       09939.367                       0
Bank Sta=9810.275,10510.28
Exp/Cntr=0.3,0.1

Type RM Length L Ch R = 1 ,47004.75,146.921300,146.921300,146.921300
XS GIS Cut Line= 6
792461.221294159774826.817064011792571.673727323 774791.28107873
792761.660811564774703.586147523792855.211186532774670.191378404
792963.713774766774636.263246869793168.203720115774583.094187634
#Sta/Elev= 30
 9762.42591.0788 9766.35589.2772 9787.15572.35249807.958558.37349839.693538.1071
 9882.09 513.3569894.844503.98369903.751499.35689925.412498.57659936.243494.3454
9947.112486.11689958.302482.07849969.491480.63929980.681481.548910014.32480.4661
10025.55482.146810047.84490.116710069.67493.120510123.26495.3396 10144.5499.3837
10176.35507.355410207.93521.026510228.88528.439210239.36529.697310312.58531.7902
10343.69 542.25910374.81549.384410395.55551.581910416.29556.2429 10512.2 582.506
#Mann= 3 , 0 , 0
 9762.42    0.04       0 9762.42    0.04       0 10512.2    0.04       0
#XS Ineff= 2 , 0
       0                               0
Bank Sta=9762.42,10512.2
Exp/Cntr=0.3,0.1

Type RM Length L Ch R = 1 ,46857.83,146.921300,146.921300,146.921300
XS GIS Cut Line= 6
792229.469214228775075.696625849792394.195837244775043.055464943
 792557.19061044774983.239907724792946.089114463774752.466002677
793102.975546981774685.161802819793192.315652514774656.624030073
#Sta/Elev= 30
9431.901726.48499447.629715.30649457.757713.80249498.267699.37989518.557698.7551
9549.387705.5541 9569.94703.28539590.494697.20979663.729654.2461 9706.23621.8422
9749.654592.02369771.366 575.9049782.526555.30599813.618549.11169827.508548.2211
 9861.32524.55389896.257494.54389919.549492.31189935.476483.99629966.874480.5561
9978.787477.468310002.67476.141210026.58478.124210038.53485.538710050.49489.8403
10121.57496.5467 10156.7501.625710213.67513.579910302.47540.6205 10490.9576.2204
#Mann= 3 , 0 , 0
9431.901    0.04       09431.901    0.04       0 10490.9    0.04       0
#XS Ineff= 2 , 0
       0                               0
Bank Sta=9431.901,10490.9
Exp/Cntr=0.3,0.1

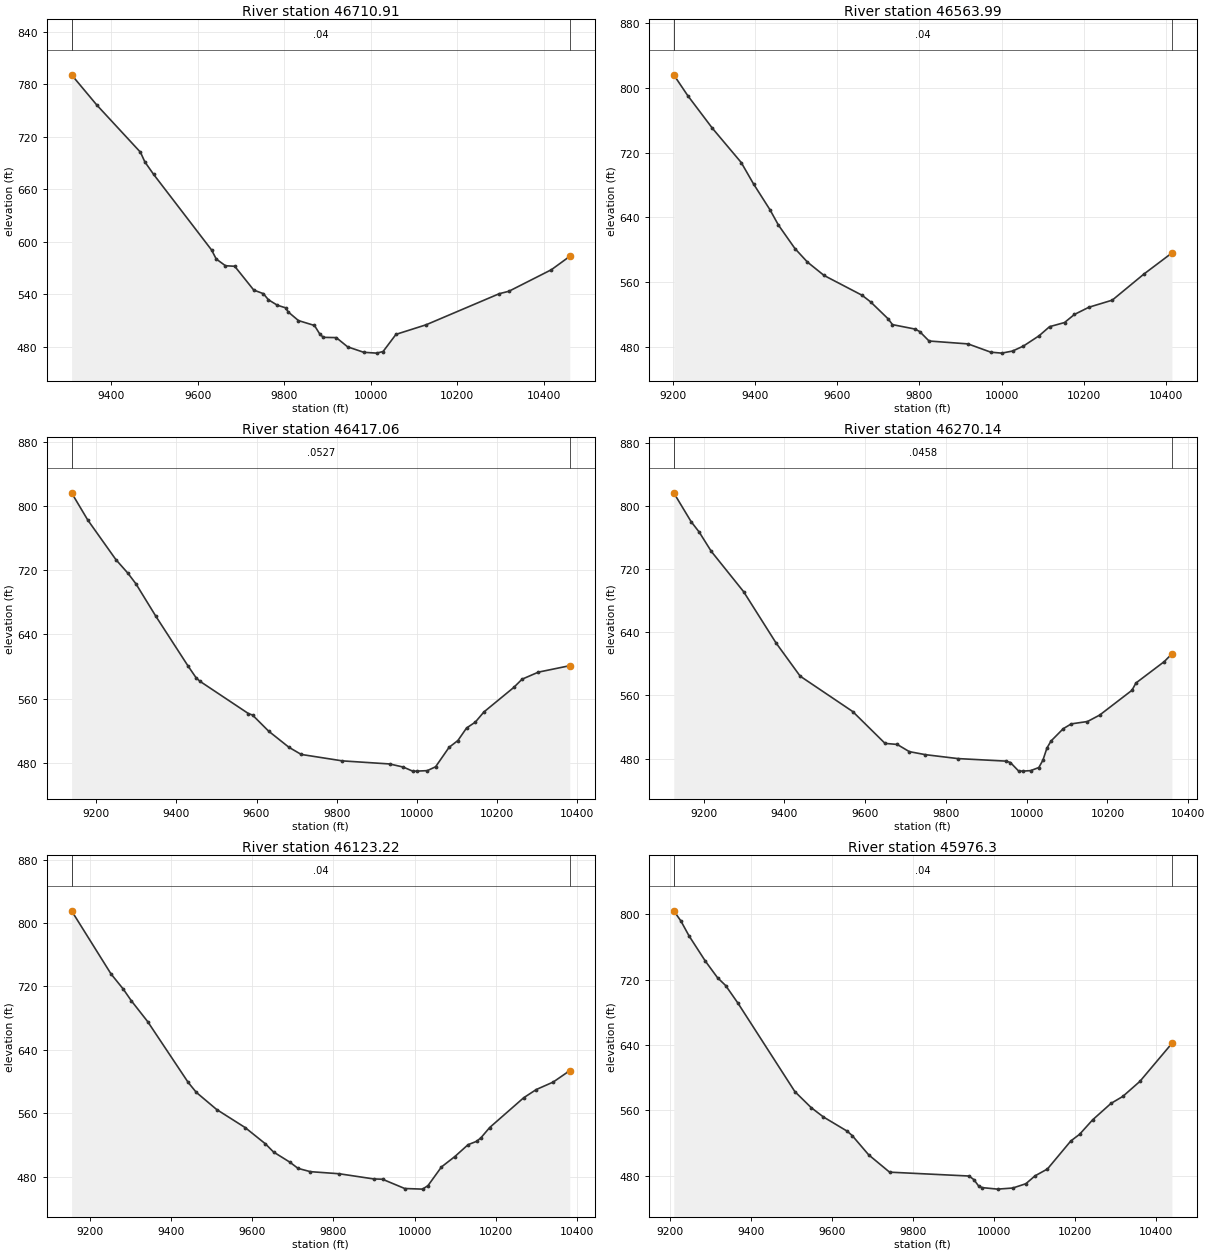
Type RM Length L Ch R = 1 ,46710.91,146.921400,146.921400,146.921400
XS GIS Cut Line= 6
792216.568945399  775231.1217159792465.756717765775196.827670521
792597.803337211775153.283415068792725.338410469775082.705783659
793005.501658637774856.352185318793234.796171611774746.657369066
#Sta/Elev= 30
9308.143790.94399366.718756.26959467.462702.39369477.658 691.2849498.058676.9417
9632.108590.41979642.693580.21099664.091572.4946 9685.49571.89129729.475544.6825
9751.747540.53649763.464533.55739784.095527.31139802.997524.36799809.388519.5418
9832.956509.73849869.926504.14379882.534494.11729890.635490.55229920.355490.2437
9946.722479.68419983.895473.4502 10013.8472.4959 10028.7474.339710058.52493.9732
10128.18504.9239 10297.5540.514810319.58543.272210417.94567.935210460.44583.2248
#Mann= 3 , 0 , 0
9308.143    0.04       09308.143    0.04       010460.44    0.04       0
#XS Ineff= 2 , 0
       0                               0
Bank Sta=9308.143,10460.44
Exp/Cntr=0.3,0.1

Type RM Length L Ch R = 1 ,46563.99,146.921300,146.921300,146.921300
XS GIS Cut Line= 6
792200.954424501775310.016137207792465.603856569 775297.57259877
792740.344919424775231.660208681792845.739039775775173.355431569
793101.604809576 774973.02002251793298.314861365774881.279069755
#Sta/Elev= 30
9202.692816.03789236.743790.34589296.766749.98589366.819707.72079396.931681.1339
9437.081649.10989457.156 630.597 9497.52601.42569527.851 584.7469568.364568.2023
9660.855543.7256 9681.69535.50829724.113514.66099734.805507.46299789.762501.9728
9800.885498.95259823.759487.23459918.553483.65419973.922473.436510000.44472.2607
10026.93474.830810053.41 481.029 10091.5493.732510116.86504.910410153.28 510.046
10177.27520.001910212.46528.915210269.43537.697610346.53569.9786 10414.6595.9933
#Mann= 3 , 0 , 0
9202.692    0.04       09202.692    0.04       0 10414.6    0.04       0
#XS Ineff= 2 , 0
       0                               0
Bank Sta=9202.692,10414.6
Exp/Cntr=0.3,0.1

Type RM Length L Ch R = 1 ,46417.06,146.921300,146.921300,146.921300
XS GIS Cut Line= 6
792194.653194044775341.853933171792573.359079066775332.617128268
792826.134186576775293.780432537792940.500406155775257.194036164
793187.809442042775134.896900641793389.950466215775075.491844237
#Sta/Elev= 30
9138.734816.36699179.094782.48459249.117733.22959279.123716.27469299.126703.0788
9349.136662.38869429.272600.53679449.317585.89599459.339581.38769579.842541.2919
9589.902539.51479630.266519.38169680.874499.28979711.443 490.4069814.022482.3916
9932.069478.54419966.093474.64039989.139469.6374    9999469.618510025.75470.2189
 10046.5475.057810080.07499.255210102.09507.750110123.77523.393610145.44 530.636
10167.12543.409610241.25573.817310262.08584.153410302.67592.940110381.02 601.004
#Mann= 3 , 0 , 0
9138.734  0.0527       09138.734  0.0527       010381.02  0.0527       0
#XS Ineff= 2 , 0
       0                               0
Bank Sta=9138.734,10381.02
Exp/Cntr=0.3,0.1

Type RM Length L Ch R = 1 ,46270.14,146.921400,146.921400,146.921400
XS GIS Cut Line= 6
792192.034704066 775355.08419831792382.776261252775359.548024074
792910.746068321775337.558855979793015.445083721775342.508015762
793230.503860392 775363.30331184793424.028759998 775370.88306035
#Sta/Elev= 30
9125.816816.50289168.821779.9877 9188.84766.78599218.844742.33459298.851691.3285
9378.875626.60519438.897584.32349569.051539.5159 9649.17 499.1479679.214497.8388
9709.259488.71829749.318484.85929829.366 479.9189949.519476.67349959.591474.9426
9979.741464.31279989.815464.022310009.95464.674210030.07 468.59210040.13477.8298
10050.19493.288410060.26502.149110090.38517.709210110.44523.866210150.54526.8537
10180.59  534.9610260.65566.362410270.66575.667710340.71602.724410359.75612.6176
#Mann= 3 , 0 , 0
9125.816  0.0458       09125.816  0.0458       010359.75  0.0458       0
#XS Ineff= 2 , 0
       0                               0
Bank Sta=9125.816,10359.75
Exp/Cntr=0.3,0.1

Type RM Length L Ch R = 1 ,46123.22,146.921300,146.921300,146.921300
XS GIS Cut Line= 6
792187.915231568775375.898375127792668.531128803775391.025622272
792805.223362632775405.528864634792910.567124144775435.524265699
793159.747495695 775551.18913828793374.837772664775612.738748093
#Sta/Elev= 30
9155.279 815.366 9252.52735.6457 9282.56716.60459302.584701.75699342.593675.6249
9442.617598.68899462.621586.16199512.633 564.5819582.649541.85559632.661521.2711
9652.702510.93989692.799498.15019712.942490.31159743.223486.16089814.582483.4999
9899.163476.97619921.022476.57719975.696464.893810019.65464.1042   10033468.5137
10066.28492.125910099.26505.2584 10131.6520.149110153.16524.533910163.83529.1536
10184.94541.845110268.71579.430710299.87589.849410341.21599.191710382.15613.6473
#Mann= 3 , 0 , 0
9155.279    0.04       09155.279    0.04       010382.15    0.04       0
#XS Ineff= 2 , 0
       0                               0
Bank Sta=9155.279,10382.15
Exp/Cntr=0.3,0.1

Type RM Length L Ch R = 1 , 45976.3,146.921300,146.921300,146.921300
XS GIS Cut Line= 6
792177.589662859775428.069669608792527.148785805 775466.31467757
792690.668936662775496.817744115792815.494355779775541.452764295
793097.193438603775696.038509519793340.521037161775781.462697662
#Sta/Elev= 30
9208.357804.3532  9225.9792.00559246.018 773.7819286.254742.9198 9316.43722.5121
9336.548712.90579366.725691.49479507.549583.04269547.784563.4947 9578.06552.0264
9636.206534.80539649.006529.32769689.932  505.619741.429484.48919937.781479.7489
9949.513475.35989961.245467.64969969.855465.576610008.24463.7133 10045.7465.0576
10077.98470.322910100.86480.0343 10131.3488.346110189.17 522.72810210.66530.7889
 10242.9548.516310288.34568.654410317.44577.169710359.66595.5894 10438.8642.1443
#Mann= 3 , 0 , 0
9208.357    0.04       09208.357    0.04       0 10438.8    0.04       0
#XS Ineff= 2 , 0
       0                               0
Bank Sta=9208.357,10438.8
Exp/Cntr=0.3,0.1

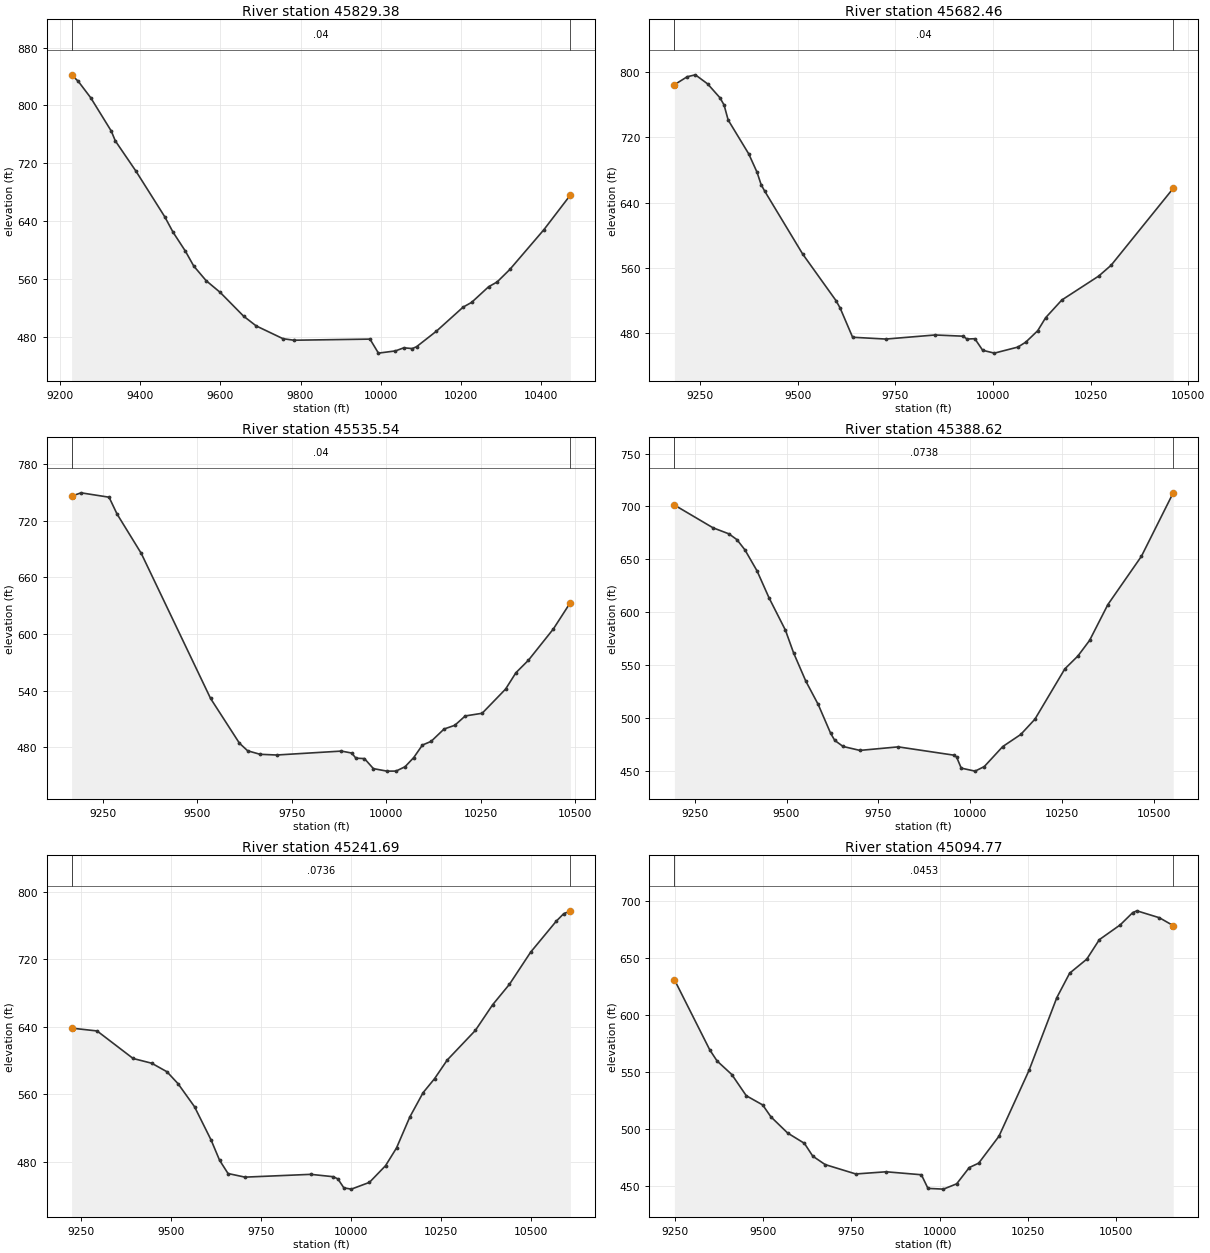
Type RM Length L Ch R = 1 ,45829.38,146.921400,146.921400,146.921400
XS GIS Cut Line= 6
792128.569330371775536.187960332 792309.18842225775575.940657557
792488.959049041775620.646323082792610.490149232775655.852520686
792871.529411542775741.186262665793317.969294534775892.342098922
#Sta/Elev= 30
9229.645842.28699246.469833.16479277.187810.71629328.384764.77939338.623751.0711
 9389.82709.49349461.794646.31569482.403625.09459513.317598.78569533.926 578.401
 9564.84 558.1829599.833542.01579658.178509.20029689.412495.78569756.483478.0632
9783.573475.98939973.044477.52569994.126458.180410036.31461.2178 10057.4465.5338
 10078.5464.467910089.05467.020610138.69488.531210205.17521.703710226.32528.2206
10268.61549.789710289.76556.355610321.48573.657910406.06628.345310472.34 676.343
#Mann= 3 , 0 , 0
9229.645    0.04       09229.645    0.04       010472.34    0.04       0
#XS Ineff= 2 , 0
       0                               0
Bank Sta=9229.645,10472.34
Exp/Cntr=0.3,0.1

Type RM Length L Ch R = 1 ,45682.46,146.921300,146.921300,146.921300
XS GIS Cut Line= 6
792073.788255438775647.817320592792698.732824682775864.306599948
792785.472261432775882.123246794792889.424707986775886.782150095
792976.387010017775900.178580552793294.918879952776005.673303959
#Sta/Elev= 30
9183.587784.31539216.287 794.074 9237.24796.4152 9268.67785.29859300.159768.3652
9310.711759.52619321.263741.06529374.022699.53719395.126677.23339405.678 661.978
9414.612654.18529512.201576.89599597.494519.91459608.156510.78729640.141474.9889
9725.434472.77949851.576 477.7759923.132476.28419933.264 472.8129953.336473.2051
9973.388459.025910003.39455.545210063.57462.945510083.74468.9694 10114.3482.9386
 10134.8498.971110176.16520.598210270.68549.920310302.41563.1205 10461.6 657.361
#Mann= 3 , 0 , 0
9183.587    0.04       09183.587    0.04       0 10461.6    0.04       0
#XS Ineff= 2 , 0
       09887.724                       0
Bank Sta=9183.587,10461.6
Exp/Cntr=0.3,0.1

Type RM Length L Ch R = 1 ,45535.54,146.921300,146.921300,146.921300
XS GIS Cut Line= 6
792051.330844223775693.579592508792283.466990426775777.678111353
792702.451149068775960.629049892792767.502291483775994.260308603
792952.526816544776106.129378906793245.738898556776247.474879173
#Sta/Elev= 30
9167.686745.88979192.714749.36939266.733744.74259287.882726.95099352.047685.1877
9535.305531.76579611.549484.45029633.402476.38219666.181472.68629709.886471.9278
9881.372476.07889908.496474.01619919.753468.54999942.268468.14659965.936457.5166
10001.76454.8698 10025.7454.903410049.65459.503210072.73469.257610095.62482.4779
 10118.5486.307410152.83499.4069 10181.3503.376310208.92513.268810253.63516.0928
10315.58541.6853   10343559.023510376.04572.231410442.12605.404310486.98633.2273
#Mann= 3 , 0 , 0
9167.686    0.04       09167.686    0.04       010486.98    0.04       0
#XS Ineff= 2 , 0
       09858.894                       0
Bank Sta=9167.686,10486.98
Exp/Cntr=0.3,0.1

Type RM Length L Ch R = 1 ,45388.62,146.921300,146.921300,146.921300
XS GIS Cut Line= 6
792017.698233772775762.113968531792268.734861527775868.905901882
792539.303406883 776011.50447217792884.904200842776257.822188044
793006.285365021776333.916738686793190.952180373776435.485342293
#Sta/Elev= 30
9194.868701.36889299.863679.83699343.158674.10449364.921668.64429386.857658.8959
 9419.76639.01959452.664613.31069496.909582.9845 9519.13   561.59552.461534.7281
9586.183512.63369620.018485.35599631.296478.62169653.853472.90169699.608469.1801
9804.008472.52679956.578464.61659962.889462.82129975.401452.410810013.01449.5695
10038.14453.867810088.39472.8206 10137.4484.259310175.91498.692310257.42546.3383
10292.82558.475610324.76573.277910374.53 607.19610465.79652.861710552.34712.9355
#Mann= 3 , 0 , 0
9194.868  0.0738       09194.868  0.0738       010552.34  0.0738       0
#XS Ineff= 2 , 0
       09871.214                       0
Bank Sta=9194.868,10552.34
Exp/Cntr=0.3,0.1

Type RM Length L Ch R = 1 ,45241.69,146.921400,146.921400,146.921400
XS GIS Cut Line= 6
791970.950809056775857.372871741792190.498045543775965.017112174
792390.123628693 776081.91968732792829.911252884776401.660201764
792946.765789953776479.444269355793141.174448569776594.151862395
#Sta/Elev= 30
 9223.17638.27959293.969634.91839394.089602.25429445.798596.61979488.077586.5207
9518.787572.43099564.686545.04429610.842505.4504 9634.34481.51169657.838465.7573
9704.953461.46189887.807464.77519950.418461.9562 9963.15459.30969979.764 448.713
10000.52447.233610050.78455.2648 10095.5475.039810125.96496.052510162.95532.8112
10199.93561.743610231.58578.224710267.04600.489110345.18635.6137   10393665.9591
10439.93690.3664 10498.6728.362310570.09765.294610590.46774.010510609.11777.4659
#Mann= 3 , 0 , 0
 9223.17  0.0736       0 9223.17  0.0736       010609.11  0.0736       0
#XS Ineff= 2 , 0
       09880.695                       0
Bank Sta=9223.17,10609.11
Exp/Cntr=0.3,0.1

Type RM Length L Ch R = 1 ,45094.77,146.921300,146.921300,146.921300
XS GIS Cut Line= 6
791916.434587253775968.462531279792061.970684208776046.228959954
 792250.76829499 776162.07811454792763.902524923 776534.87210808
792895.266728197776624.141816517793094.034220529 776744.41133925
#Sta/Elev= 30
9249.562630.84069349.674569.23879370.317559.5323 9412.03547.6428 9452.93529.0604
9499.358520.98049522.706510.5471 9570.08496.32859617.455487.29089641.255476.0232
9676.332468.63239763.007460.40479849.053462.31519948.738459.70959967.319447.7466
10011.07447.096410048.54451.736410084.29466.037810110.98469.900710168.34 493.503
10253.62551.418710332.23615.1955 10368.5636.599910416.87648.874310452.58666.0283
10511.63678.960810547.05689.742910558.86691.296310622.59685.222710661.65678.3193
#Mann= 3 , 0 , 0
9249.562  0.0453       09249.562  0.0453       010661.65  0.0453       0
#XS Ineff= 2 , 0
       09888.216                       0
Bank Sta=9249.562,10661.65
Exp/Cntr=0.3,0.1

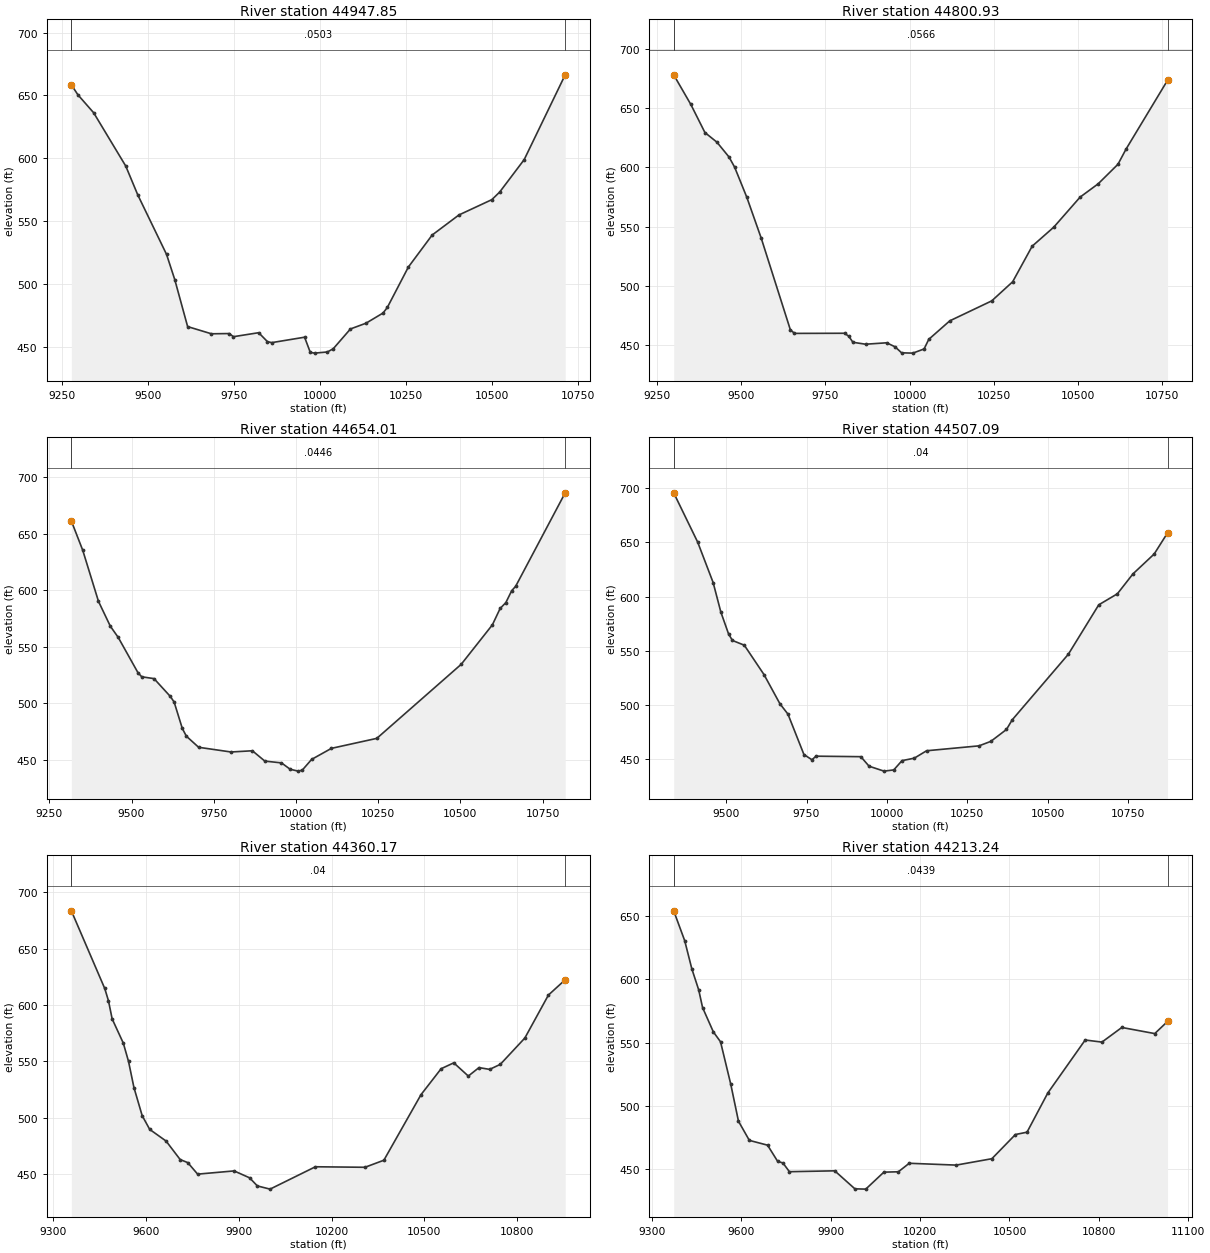
Type RM Length L Ch R = 1 ,44947.85,146.921300,146.921300,146.921300
XS GIS Cut Line= 6
791858.369670513776086.783493711792023.578812857 776184.31727357
792134.182217192776256.587509911792778.544035762776725.204176862
792885.727639958776796.029101134793047.198294602 776893.70085312
#Sta/Elev= 30
 9275.84658.40699294.942 650.4569340.886636.14199434.256593.78889469.413570.7545
9553.032523.53729576.923503.52119614.408466.11849683.686460.39279735.646460.5837
9747.812458.0853 9821.27461.26169846.764454.17739859.242 453.3599955.024457.6833
9971.544445.63379984.022445.014710021.49445.942510038.53448.523910088.57464.2409
10133.93468.824610183.53476.930610195.92481.317410257.21513.479610326.53538.9506
10404.39554.894810500.28567.076610523.25  573.1610594.55598.956310713.85  666.35
#Mann= 3 , 0 , 0
 9275.84  0.0503       0 9275.84  0.0503       010713.85  0.0503       0
#XS Ineff= 2 , 0
       09783.685                       0
Bank Sta=9275.84,10713.85
Exp/Cntr=0.3,0.1

Type RM Length L Ch R = 1 ,44800.93,146.921400,146.921400,146.921400
XS GIS Cut Line= 6
791796.143245963776208.305918747792014.858037578776348.738353523
792170.505069427776459.832165274792691.868761772776845.980988154
792801.547054694776919.472190516793001.270269154777040.096434215
#Sta/Elev= 30
9299.966677.96189350.804652.99129392.625629.33929428.152621.24489464.134608.7328
9480.705600.21479516.926574.80499559.918540.16899646.094463.2181 9658.38460.1561
9806.797460.26989819.304457.80719831.812452.67079869.335 451.0419931.872 452.241
9956.887448.84749976.184443.794910009.52443.534310042.97447.0539 10056.8455.1328
10119.18470.724610243.68487.543610305.74503.6277 10363.7533.624310427.82549.6519
   10506 574.96610559.57586.158210618.35602.642310641.86615.201810765.36673.3469
#Mann= 3 , 0 , 0
9299.966  0.0566       09299.966  0.0566       010765.36  0.0566       0
#XS Ineff= 2 , 0
       09809.806                       0
Bank Sta=9299.966,10765.36
Exp/Cntr=0.3,0.1

Type RM Length L Ch R = 1 ,44654.01,146.921300,146.921300,146.921300
XS GIS Cut Line= 6
791725.507305942776327.699410282791990.361473101776505.506982022
792477.476835264776877.167015179792600.342603328776965.483404383
792709.911000641777039.315081049792955.450653817 777186.14645808
#Sta/Elev= 30
 9317.05661.24189351.663 635.362 9399.52590.22339435.485568.32099459.462558.4184
9519.473527.26139531.053523.57999568.401521.98069617.875506.25249629.561501.2701
9654.304478.00139666.727471.12129703.994 461.319 9802.29457.16599867.415458.2404
9905.311449.11159955.839447.54239982.327441.920610006.39440.254810019.05 441.115
10047.59450.621210107.69460.367110245.75469.203910502.25 534.60710597.12569.4986
10620.66583.952210637.91589.097710655.96599.713310667.73603.485810818.44686.1139
#Mann= 3 , 0 , 0
 9317.05  0.0446       0 9317.05  0.0446       010818.44  0.0446       0
#XS Ineff= 2 , 0
       09837.182                       0
Bank Sta=9317.05,10818.44
Exp/Cntr=0.3,0.1

Type RM Length L Ch R = 1 ,44507.09,146.921300,146.921300,146.921300
XS GIS Cut Line= 6
791652.702363727776450.759091365791900.047108001776618.965311631
792366.940093199 776979.91785541792478.283651996 777060.69442128
792712.388372833777214.185628215792911.660995728777325.725993219
#Sta/Elev= 30
9336.957695.87399411.454650.34489459.535612.98449483.576585.66439507.693565.3367
9519.705559.43859556.449555.08139617.689527.93429667.187500.96559692.088491.4305
9741.891454.03119766.792449.21869779.331452.53879918.757 452.0699944.357443.2741
9990.776438.721810021.13439.8434 10046.7448.400110085.04450.704810123.13457.5374
10286.06462.077310322.76466.193610371.51477.205410389.23486.051210564.03 546.789
10658.45592.3908 10716.3602.571310764.77620.9683 10830.8639.361910872.27658.8587
#Mann= 3 , 0 , 0
9336.957    0.04       09336.957    0.04       010872.27    0.04       0
#XS Ineff= 2 , 0
       09863.015                       0
Bank Sta=9336.957,10872.27
Exp/Cntr=0.3,0.1

Type RM Length L Ch R = 1 ,44360.17,146.921400,146.921400,146.921400
XS GIS Cut Line= 6
791574.989666608776582.114181178791805.399421597776738.495957979
792278.091387939777091.453128303792490.235450482777237.668902216
792743.375623608777388.761936599792901.396309976777469.326410257
#Sta/Elev= 30
9357.882683.51359465.917614.5879 9477.92603.75639489.922587.60029526.087566.0469
 9542.97549.79539560.429526.68229587.084501.73059611.482489.5121 9664.46479.1799
9710.021462.75439734.736460.01839766.585449.80659884.635452.66689934.793446.5361
9959.872439.3466   10001436.501710147.86456.348710308.25455.888110369.39462.1519
 10489.6520.354810554.68543.358910595.59548.598310642.69536.857910677.22544.3631
10711.72542.787310746.22547.243210825.64570.601610901.99608.764810956.24622.3231
#Mann= 3 , 0 , 0
9357.882    0.04       09357.882    0.04       010956.24    0.04       0
#XS Ineff= 2 , 0
       0 9875.06                       0
Bank Sta=9357.882,10956.24
Exp/Cntr=0.3,0.1

Type RM Length L Ch R = 1 ,44213.24,146.921300,146.921300,146.921300
XS GIS Cut Line= 6
791493.842527218776719.274390229791685.130387663776846.321030172
 792235.54033609 777230.18581427 792452.09733596777371.585712183
792666.656029105777492.996829614792894.194311112777600.562834249
#Sta/Elev= 30
9372.945653.93389409.875630.38579433.759608.22179456.793591.65199469.904577.6204
9506.049558.46899530.145550.65799564.365517.30819590.386488.02729626.872472.9276
9687.972 469.1539722.085456.31399739.484455.16489761.292448.23749913.473448.9235
9981.078434.732410017.61 434.49110078.41447.879110127.06448.168610163.54454.8772
10321.18453.432410440.95458.474310520.01477.552210558.91479.384710628.64 510.272
 10754.2552.075310810.41550.419810877.19561.9628 10987.7557.140211030.58566.6977
#Mann= 3 , 0 , 0
9372.945  0.0439       09372.945  0.0439       011030.58  0.0439       0
#XS Ineff= 2 , 0
       09880.783                       0
Bank Sta=9372.945,11030.58
Exp/Cntr=0.3,0.1