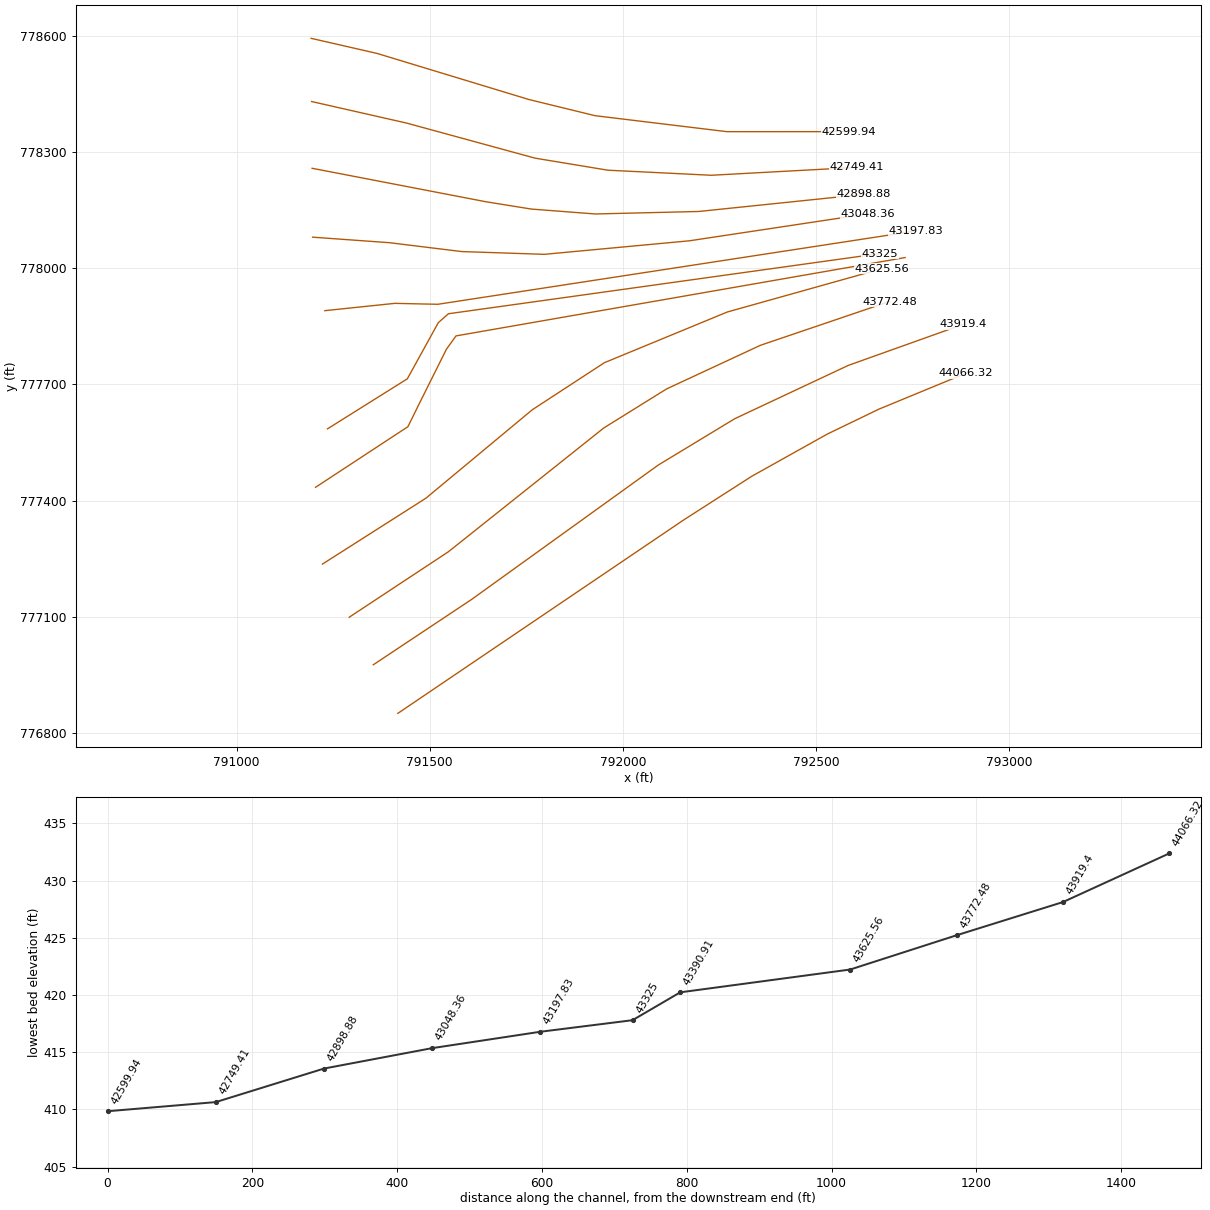
HEC-RAS study 17465_ras.prj: 17465

--- 17465_ras.g01 (geometry) --- (continued)

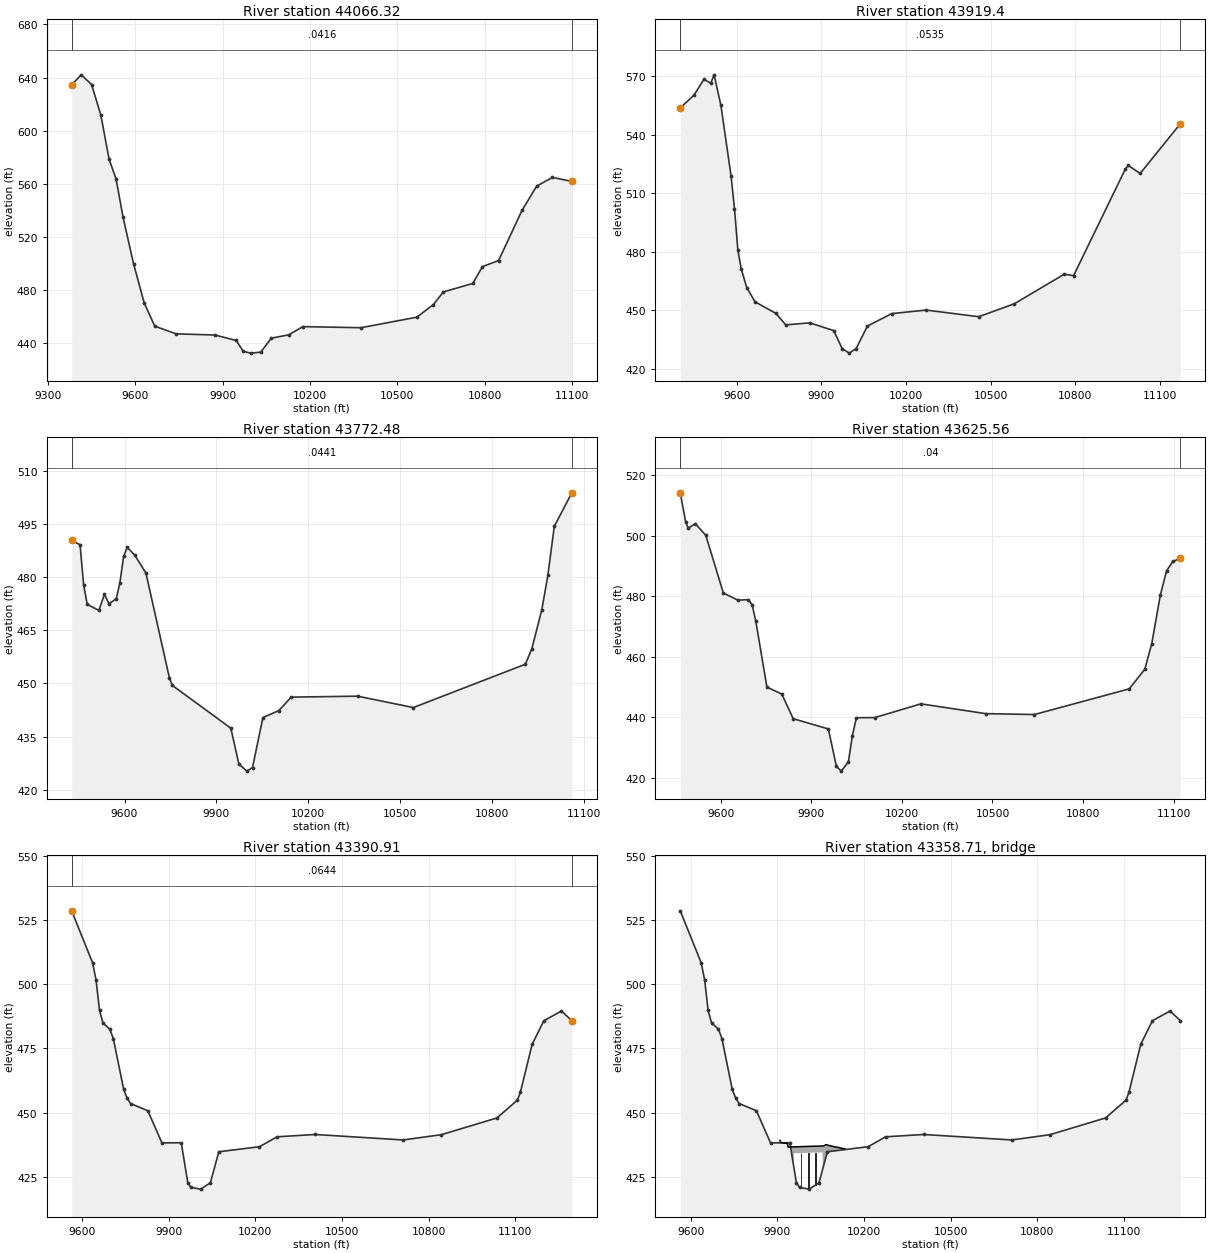
Type RM Length L Ch R = 1 ,44066.32,146.921300,146.921300,146.921300
XS GIS Cut Line= 6
791417.275263239776850.549836479792156.284280441777349.440655377
792333.433879733  777462.8490257792529.208052361777571.939231455
792663.009806721777636.341206107  792887.1703946777728.554202019
#Sta/Elev= 30
9381.943634.49879414.709642.02949450.402634.67779482.267611.53859510.462578.4731
9534.486563.4331 9558.51534.58739594.546 499.5959630.867 470.2419667.363452.6678
9740.354446.9065 9874.17445.99619946.863441.89029970.926433.72549996.744432.3708
10031.12433.091710067.27443.617610127.51446.1785 10175.7452.345110375.17451.5088
10566.84459.443510623.95468.968410657.99  478.4610758.97 484.86810792.26497.5386
10847.75502.128910928.04539.892410978.53 558.21311032.54564.730111099.08561.7547
#Mann= 3 , 0 , 0
9381.943  0.0416       09381.943  0.0416       011099.08  0.0416       0
#XS Ineff= 2 , 0
       09880.098                       0
Bank Sta=9381.943,11099.08
Exp/Cntr=0.3,0.1

Type RM Length L Ch R = 1 , 43919.4,146.921300,146.921300,146.921300
XS GIS Cut Line= 6
791353.735562326776976.020638253791608.402796908777144.910170945
792091.620769722 777491.92255417792289.581402158777611.596805535
792583.165102696777749.106784254792880.235629898777854.921025714
#Sta/Elev= 30
9400.321553.8662    9449560.43929484.391568.5471 9508.22566.49389520.243570.8226
9544.289555.15539580.359518.87829592.382502.23199604.405480.88069616.456471.1399
9636.215461.6437 9665.23454.4291 9738.86448.50689774.074442.61059859.026443.6391
9943.977439.66249973.879430.46159998.617428.118610023.27 430.43710063.36441.9856
10148.92448.368110270.92 450.19810457.65446.790610583.39453.404710760.82468.6134
 10793.6467.839910976.34 522.32910986.98524.380811029.52520.255111172.06545.7673
#Mann= 3 , 0 , 0
9400.321  0.0535       09400.321  0.0535       011172.06  0.0535       0
#XS Ineff= 2 , 0
       09881.375        10125.07       0
Bank Sta=9400.321,11172.06
Exp/Cntr=0.3,0.1

Type RM Length L Ch R = 1 ,43772.48,146.921400,146.921400,146.921400
XS GIS Cut Line= 6
791291.515589156 777098.88539537791548.389807841 777268.05137811
791950.449688903777587.605964239792112.883281517 777688.35326276
792355.922315189777801.079792579792689.767407259777914.113859802
#Sta/Elev= 30
9427.405490.47729454.825489.22919466.501477.88019478.177472.37589516.122470.6773
9534.404 475.2039549.212472.51159573.103474.00859585.048478.54719596.994485.9527
9608.939488.49519633.105 486.3219669.797481.27159746.613451.57599755.925449.4734
9947.187  437.369973.398427.21879999.619425.217210018.01426.242810051.94440.3789
10103.85442.3299 10144.2446.142910361.32 446.41610543.01443.195910908.89455.4427
10930.07 459.77910962.75470.878810982.42480.549811003.43494.432511060.68503.9204
#Mann= 3 , 0 , 0
9427.405  0.0441       09427.405  0.0441       011060.68  0.0441       0
#XS Ineff= 2 , 0
       09891.903        10118.94       0
Bank Sta=9427.405,11060.68
Exp/Cntr=0.3,0.1

Type RM Length L Ch R = 1 ,43625.56,234.652100,234.652100,234.652100
XS GIS Cut Line= 6
791222.059158797777236.039865412791489.981150288777406.215280287
791765.448841921777634.705877935791952.063400934777756.193776689
792270.064569398777887.044315541792669.292357118777998.656002299
#Sta/Elev= 30
 9465.32514.18289483.317 504.5349491.828502.4884 9515.03504.00169549.834500.1491
9608.166481.05559656.782 478.7099691.381478.90529703.587477.19149715.792471.6988
9752.408449.99379801.804447.67669839.567439.55339956.112436.16349982.667423.7998
    9999422.225910022.49 425.28310035.76433.992610049.03439.867310109.81439.9097
10262.55444.449810477.91441.220410639.13440.928510953.11 449.41411004.73455.8931
11027.65464.312511056.35 480.443   11077488.445611097.65491.502611122.73492.5079
#Mann= 3 , 0 , 0
 9465.32    0.04       0 9465.32    0.04       011122.73    0.04       0
#XS Ineff= 2 , 0
       09910.042        10121.49       0
Bank Sta=9465.32,11122.73
Exp/Cntr=0.3,0.1

Type RM Length L Ch R = 1 ,43390.91,65.903400,65.903400,65.903400
XS GIS Cut Line= 6
791204.315100163777434.391921625791443.403872371777590.895996511
 791474.74972719777654.320270061791543.158595353777791.138006389
791567.861200243777825.339114442 792730.43790251 778027.69359535
#Sta/Elev= 30
9563.967528.57969636.497508.32039648.449 501.6369660.401489.80069672.353484.9103
9696.256 482.5159708.208478.85739744.064  459.059756.016 455.6259767.968453.5528
9827.727450.74699876.611438.22139943.391438.30219965.952422.78199977.133420.8791
10010.47420.234810044.21422.703910073.44434.783410214.23 436.74610275.13440.6049
10407.08441.508210711.59439.376810843.55441.4199 11036.4447.944311107.46454.9076
11117.61457.971311158.21476.564811198.81485.798811259.71489.578511295.68485.8204
#Mann= 3 , 0 , 0
9563.967  0.0644       09563.967  0.0644       011295.68  0.0644       0
#XS Ineff= 2 , 0
       09919.496        10110.84       0
Bank Sta=9563.967,11295.68
Exp/Cntr=0.3,0.1

Type RM Length L Ch R = 3 ,43358.71,,,
BEGIN DESCRIPTION:
END DESCRIPTION:
Bridge Culvert--1,0,-1,-1, 0
Deck Dist Width WeirC Skew NumUp NumDn MinLoCord MaxHiCord MaxSubmerge Is_Ogee
21.951700,22.000000,2.6,0, 23, 23, , , 0.95, 0, 0,0,,
 9908.81 9911.97 9913.39 9923.20 9934.43 9935.39 9937.08 9957.02 9957.0210057.02
10057.0210061.0710067.3810069.1510075.3010080.3210090.0310091.4310102.5310113.04
10113.6310124.7310133.37
  439.20  438.58  438.29  438.19  437.99  437.75  436.62  436.69  436.69  437.04
  437.04  437.06  437.58  437.53  437.34  437.19  436.94  436.90  436.61  436.44
  436.43  436.09  435.92
 -560.80 -561.42 -561.71 -561.81 -562.01 -562.25 -563.38 -563.31  434.19  434.54
 -562.96 -562.94 -562.42 -562.47 -562.66 -562.81 -563.06 -563.10 -563.39 -563.56
 -563.57 -563.91 -564.08
 9908.81 9911.97 9913.39 9923.20 9934.43 9935.39 9937.08 9944.55 9944.5510044.55
10044.5510061.0710067.3810069.1510075.3010080.3210090.0310091.4310102.5310113.04
10113.6310124.7310133.37
  439.20  438.58  438.29  438.19  437.99  437.75  436.62  436.64  436.64  437.00
  437.00  437.06  437.58  437.53  437.34  437.19  436.94  436.90  436.61  436.44
  436.43  436.09  435.92
 -560.80 -561.42 -561.71 -561.81 -562.01 -562.25 -563.38 -563.36  434.14  434.50
 -563.00 -562.94 -562.42 -562.47 -562.66 -562.81 -563.06 -563.10 -563.39 -563.56
 -563.57 -563.91 -564.08
Pier Skew, UpSta & Num, DnSta & Num=  ,9981.52, 2 ,9969.05, 2 , 0 , 0 , 0 ,,
    2.00    2.00
 -563.23  436.77
    2.00    2.00
 -563.27  436.73
Pier Skew, UpSta & Num, DnSta & Num=  ,10007.02, 2 ,9994.55, 2 , 0 , 0 , 0 ,,
    2.00    2.00
 -563.13  436.87
    2.00    2.00
 -563.18  436.82
Pier Skew, UpSta & Num, DnSta & Num=  ,10032.52, 2 ,10020.05, 2 , 0 , 0 , 0 ,,
    2.00    2.00
 -563.04  436.96
    2.00    2.00
 -563.09  436.91
BR Coef=-1 , 0 , 0 ,, 0 ,,,0.8,0,1,0,
WSPro=,,,, 1 ,,,, 0 ,,,, 0 ,,,,-1 ,-1 ,-1 , 0 , 0 , 0 , 0 , 0
BC Design=,, 0 ,, 0 ,,,,,,

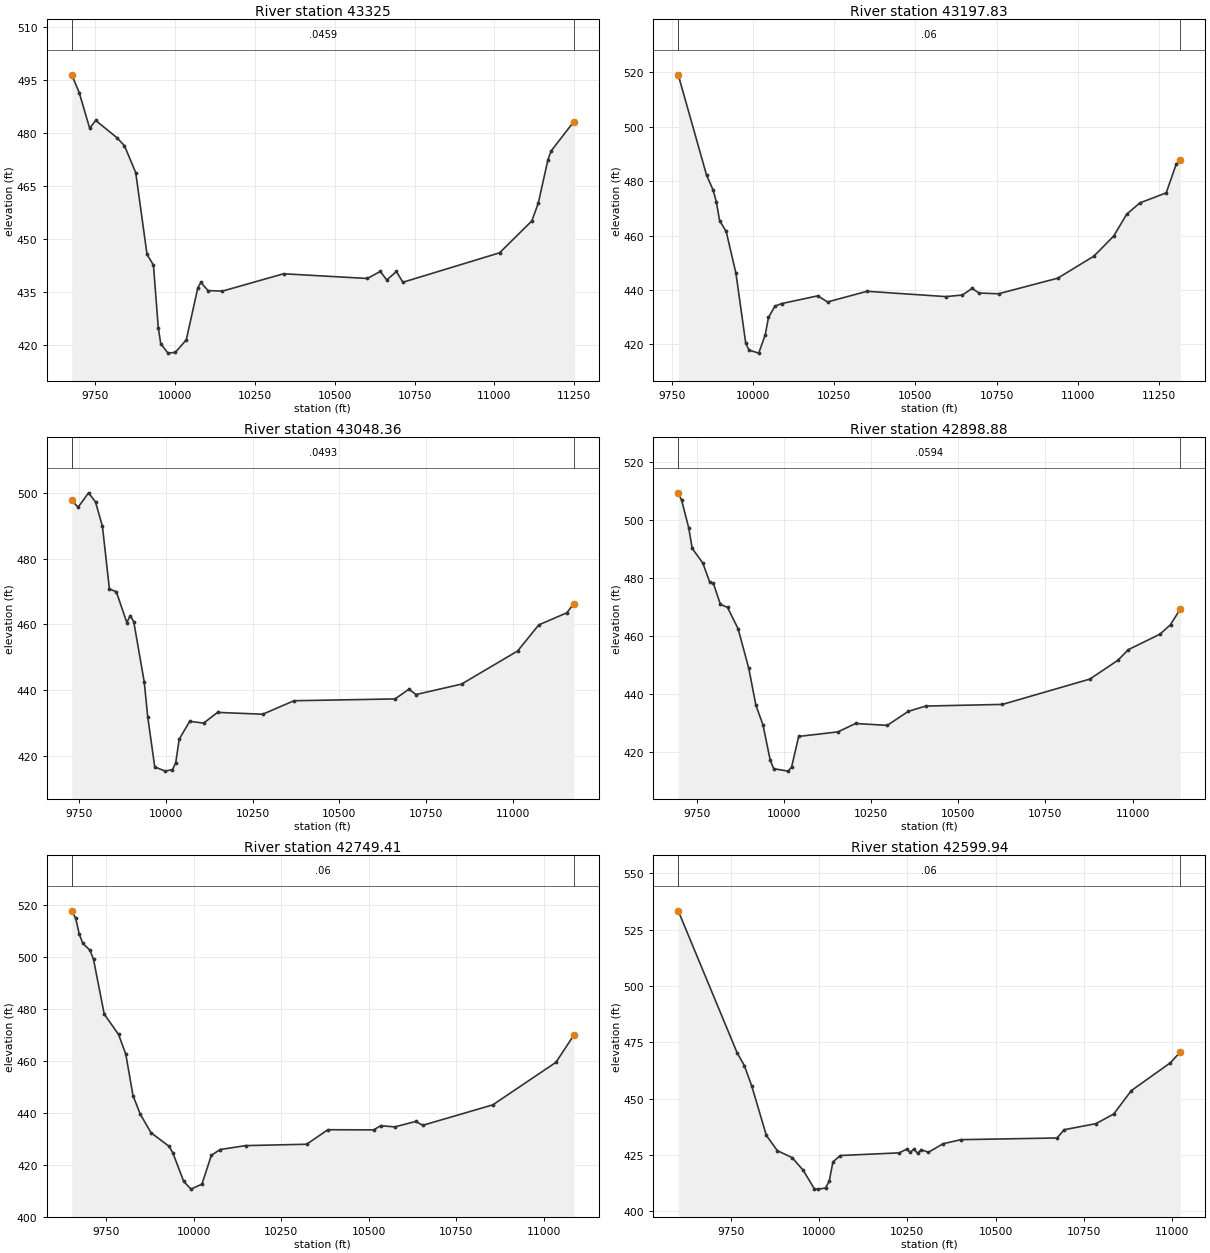
Type RM Length L Ch R = 1 ,   43325,127.177000,127.177000,127.177000
XS GIS Cut Line= 5
791235.180505157777585.289457127791441.928397417  777714.5636141
791522.032420158 777859.47907342791548.225270063777882.564423367
 792665.27760309778037.982063681
#Sta/Elev= 30
9676.802496.56459700.177491.52119732.843481.44479751.705483.66049818.117478.7839
9841.705476.50999877.086468.87989912.468445.72759932.564442.7156 9947.66425.0291
9955.416420.46529978.268417.799710001.12418.0189 10035.4421.548110071.68436.3386
 10081.1437.806410103.51435.502510148.17435.3406   10340440.2611 10602.5438.9276
10642.89440.921910663.08438.505310693.37440.904810713.56437.855311016.45446.1937
11117.41455.209711137.61460.2664 11167.9472.563111177.99475.045411248.95483.3161
#Mann= 3 , 0 , 0
9676.802  0.0459       09676.802  0.0459       011248.95  0.0459       0
#XS Ineff= 2 , 0
       09912.802        10099.55       0
Bank Sta=9676.802,11248.95
Exp/Cntr=0.3,0.1

Type RM Length L Ch R = 1 ,43197.83,149.471400,149.471400,149.471400
XS GIS Cut Line= 6
791228.321526259777890.514017597791409.540862411777909.415785596
791453.705186039777908.429807425791455.703448653 777908.34646152
791520.953973174777907.014428422 792757.87381804778096.283384219
#Sta/Elev= 30
9770.167519.09489857.315 482.2279877.424476.76589887.478472.35749897.532465.4715
9917.641461.53629947.803446.11929977.834420.45959987.837417.914110017.84416.7907
10037.85423.516210047.85429.9001 10067.9 434.07210088.13434.995110199.41437.8483
10229.76435.610510351.16439.526510593.95437.567610644.54438.159710674.89440.6064
10695.12438.897210755.82438.614810937.91444.342611049.19452.436411109.89459.7897
11150.36467.895611190.82472.020411271.75475.7089 11302.1486.131811315.13487.9082
#Mann= 3 , 0 , 0
9770.167    0.06       09770.167    0.06       011315.13    0.06       0
#XS Ineff= 2 , 0
       0                10076.46       0
Bank Sta=9770.167,11315.13
Exp/Cntr=0.3,0.1

Type RM Length L Ch R = 1 ,43048.36,149.471400,149.471400,149.471400
XS GIS Cut Line= 6
791196.674797861778080.321120165791395.720120083778066.031072184
791582.626361897  778043.1456554791796.615197258778036.004783801
 792172.11142314778070.951236029 792634.90523301 778140.64154696
#Sta/Elev= 30
9728.722497.72679747.073495.65319777.116500.03419797.145497.27169817.174489.8114
9837.202470.80689857.285469.91269887.419460.57189897.463462.69659907.508460.7688
9937.669442.48569947.744431.84289967.894416.64529998.118415.359810019.09415.8311
10028.34417.867610038.42425.071610068.64430.511310108.94429.974810149.08433.2337
10279.25 432.672 10369.3436.776210660.67437.329810700.97440.299310721.15438.6605
10852.45441.842411014.24451.9251   11075459.847711156.01463.534711176.16466.3562
#Mann= 3 , 0 , 0
9728.722  0.0493       09728.722  0.0493       011176.16  0.0493       0
#XS Ineff= 2 , 0
       0                10107.51       0
Bank Sta=9728.722,11176.16
Exp/Cntr=0.3,0.1

Type RM Length L Ch R = 1 ,42898.88,149.471400,149.471400,149.471400
XS GIS Cut Line= 6
791195.352184152778258.212664647 791645.21710867778171.789719334
  791762.4357279778152.954324895791928.338586286 778140.23179217
792196.230586783778146.664775589792622.766030391778190.764706143
#Sta/Elev= 30
9696.636509.34019706.386506.76929726.597497.36459736.702 490.2149767.019485.2026
 9787.23478.53969797.336478.18679817.648470.95159837.997469.93119868.521462.5247
9899.044448.92689919.428436.25589939.885429.42029960.342417.43719970.571414.4057
10011.48413.574710021.71414.920610042.16425.514210154.67427.078210205.31429.9645
10296.29429.323310356.58434.138710406.67435.966310626.78436.535210877.52445.2533
10958.04451.732110988.24455.400211078.83460.717211109.02464.003911136.97469.3774
#Mann= 3 , 0 , 0
9696.636  0.0594       09696.636  0.0594       011136.97  0.0594       0
#XS Ineff= 2 , 0
       0                10120.94       0
Bank Sta=9696.636,11136.97
Exp/Cntr=0.3,0.1

Type RM Length L Ch R = 1 ,42749.41,149.471400,149.471400,149.471400
XS GIS Cut Line= 6
791194.070512594 778430.59748978791439.854749692778374.996910124
791772.592194292778284.366947263791961.194737439778253.246281229
792228.800120642778240.192712047792605.855553562778260.588610452
#Sta/Elev= 30
9651.865517.68129663.001 514.8019673.206508.7738 9683.41505.16699703.818 502.524
9714.022498.97699744.635477.93579785.506470.12899806.128462.56499826.749446.6345
9847.371439.52269878.303432.31279930.073427.0897 9940.47424.6162 9971.66 413.591
9992.454410.644310023.63412.576810050.53423.647710075.57425.8751 10148.3427.3777
10322.62427.9086 10383.3433.488610514.15433.436210534.22435.044610574.26434.5767
10634.31 436.67410654.31435.195910854.37443.058611034.81 459.42311085.83 469.868
#Mann= 3 , 0 , 0
9651.865    0.06       09651.865    0.06       011085.83    0.06       0
#XS Ineff= 2 , 0
       0                10123.31       0
Bank Sta=9651.865,11085.83
Exp/Cntr=0.3,0.1

Type RM Length L Ch R = 1 ,42599.94,149.471400,149.471400,149.471400
XS GIS Cut Line= 6
791192.857145565778593.795355655791363.423871817778554.850701027
791756.244072312778435.902293806791927.836879657778394.034336789
792269.294654075778352.745859272792583.517469652 778352.82327947
#Sta/Elev= 30
9601.765533.31029768.083470.43759788.771 464.6819809.553455.69429851.117433.6874
 9882.29426.90359924.117423.83029955.564418.16249987.012409.95379997.495409.8465
10018.49410.320810028.99413.424510039.49421.905110060.48424.761710227.31425.9397
10247.99427.585110258.34426.193210268.68427.599310278.98425.774110289.23427.3443
10309.72426.186910350.72429.970510401.59431.790110673.74432.545310693.79436.2024
10783.87438.903510833.87443.159110883.87453.5561 10993.9465.847911022.43 470.683
#Mann= 3 , 0 , 0
9601.765    0.06       09601.765    0.06       011022.43    0.06       0
#XS Ineff= 2 , 0
       0                10119.07       0
Bank Sta=9601.765,11022.43
Exp/Cntr=0.3,0.1