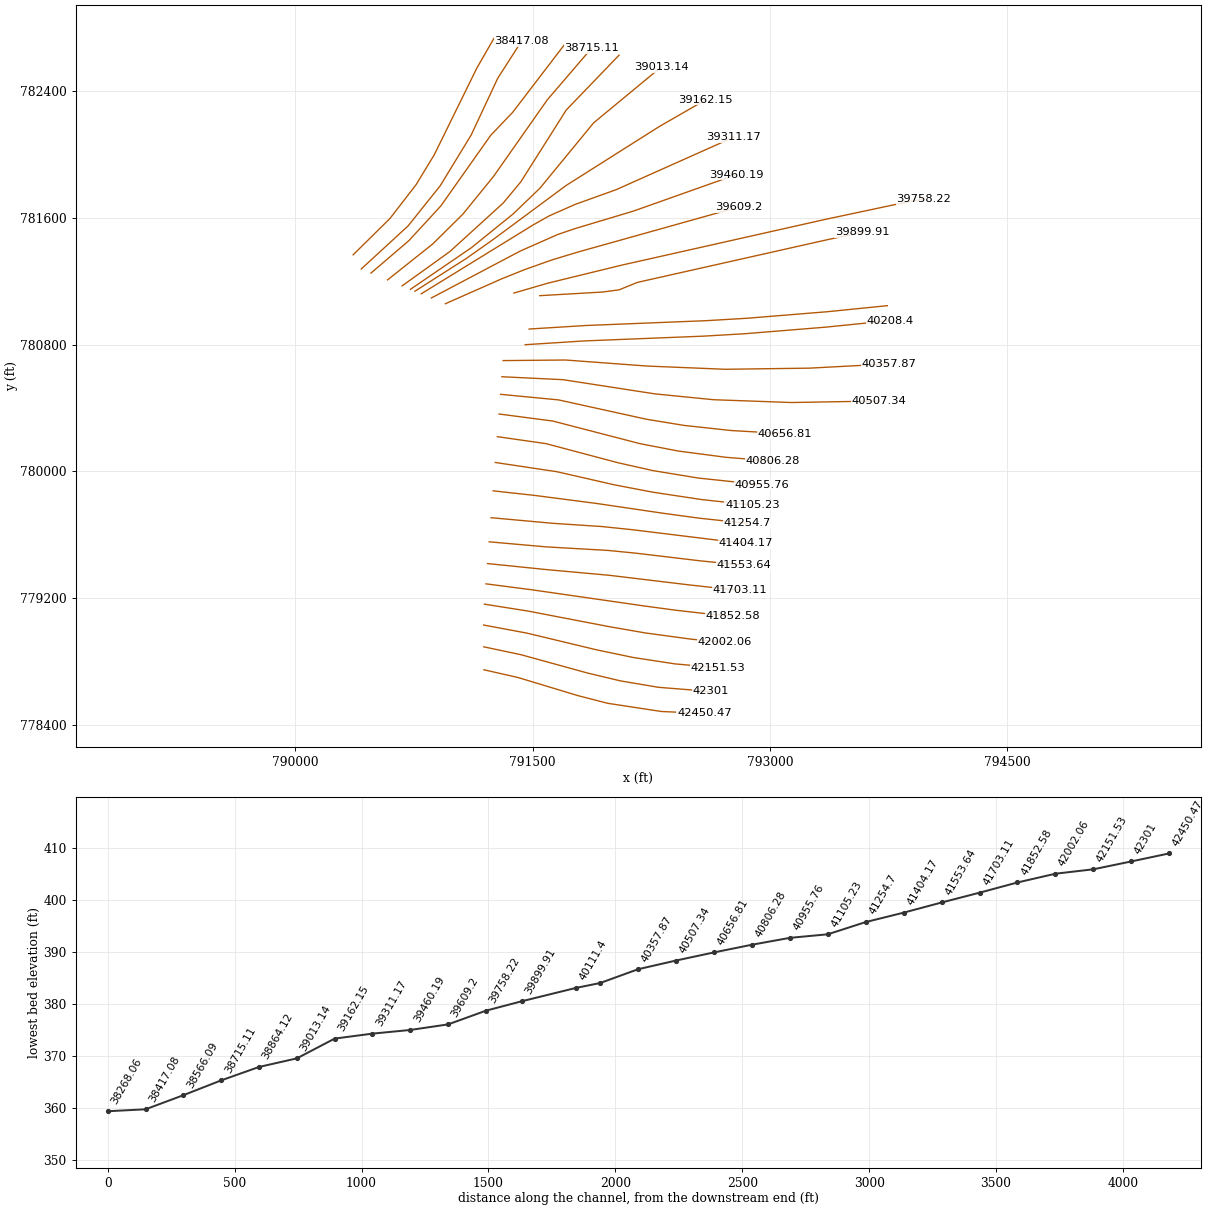
HEC-RAS study 17465_ras.prj: 17465

--- 17465_ras.g01 (geometry) --- (continued)

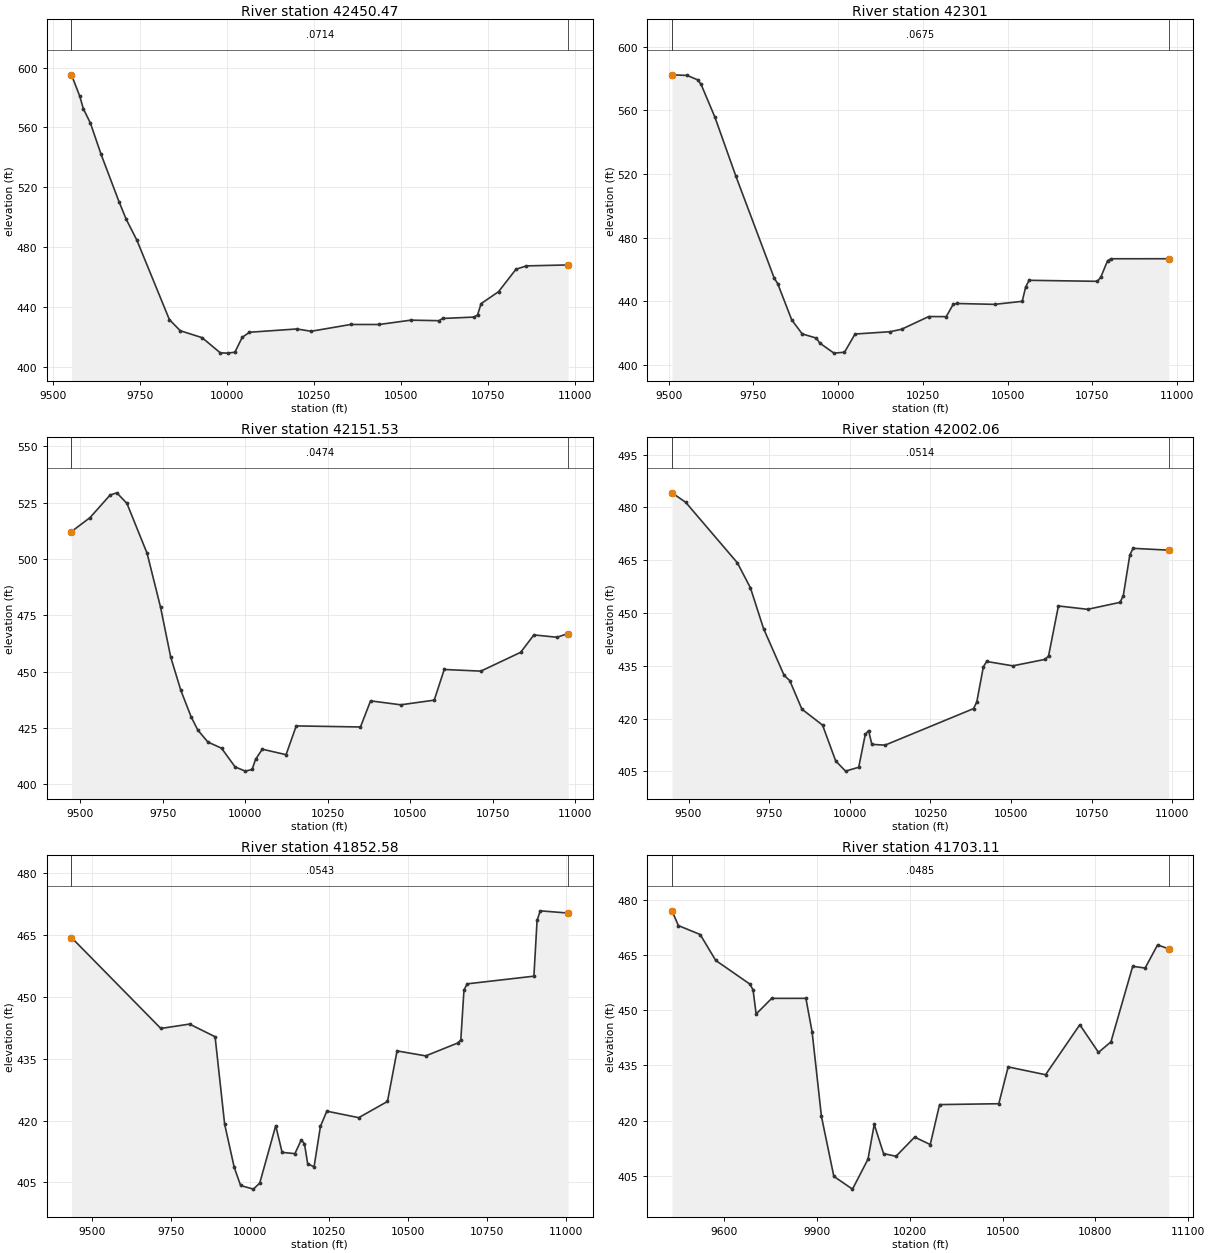
Type RM Length L Ch R = 1 ,42450.47,149.471400,149.471400,149.471400
XS GIS Cut Line= 6
 791191.72128378778746.568766227791407.186595865778697.717235674
791785.972411916778583.208672282791973.421430963778534.936214952
792313.510851929778483.024044954 792584.76277768778471.128595382
#Sta/Elev= 30
9553.556595.22429577.289580.92249587.484572.58319607.874562.90049638.459542.0368
9689.919510.37169710.512498.63769741.402484.51949834.665431.39429865.863423.9765
9928.451 419.3389980.852409.173310001.82408.975610022.75409.588310043.68 419.521
10064.61422.946210200.38 425.14810241.85423.608110355.21428.148310436.83428.1346
 10528.1 431.04510609.03430.686510619.09432.174210709.62433.100610719.65434.5728
10729.68442.083710779.81450.093410829.85465.106410859.88467.3627 10979.7467.9993
#Mann= 3 , 0 , 0
9553.556  0.0714       09553.556  0.0714       0 10979.7  0.0714       0
#XS Ineff= 2 , 0
       0                10113.98       0
Bank Sta=9553.556,10979.7
Exp/Cntr=0.3,0.1

Type RM Length L Ch R = 1 ,   42301,149.471400,149.471400,149.471400
XS GIS Cut Line= 6
 791190.64316612778891.575591946 791426.90944338 778841.51961303
791847.113970422778725.835222801792054.263299593778676.550034268
792294.490953031778635.885573028792624.876212114778609.450783072
#Sta/Elev= 30
9509.809582.27899554.954 581.8979585.488  579.129595.666576.26819636.625555.5773
9698.137518.70069811.391454.58489821.726451.07939863.067428.34589894.073419.5043
9935.667416.87859946.066413.7258 9987.66407.429110018.84407.9905   10050419.4275
10153.86420.898510187.21422.420810267.52430.417810318.96430.353910339.45438.0033
10349.69438.615210461.95438.073110543.27439.970510553.38448.922910563.49453.1821
10765.09452.543810775.15455.159910795.22465.475510805.25466.720510975.42466.7365
#Mann= 3 , 0 , 0
9509.809  0.0675       09509.809  0.0675       010975.42  0.0675       0
#XS Ineff= 2 , 0
       0                10118.01       0
Bank Sta=9509.809,10975.42
Exp/Cntr=0.3,0.1

Type RM Length L Ch R = 1 ,42151.53,149.471400,149.471400,149.471400
XS GIS Cut Line= 6
791189.619065393779029.317140162791463.145597894778978.201744663
791905.290336078778872.206169577792134.592832951778824.389372024
792399.517437898778783.711915361792668.528519462778759.975980807
#Sta/Elev= 30
 9472.85512.18059529.015518.35769589.864528.36659610.205529.34929640.813524.6812
9702.028502.50569742.838478.56879773.565456.49219804.337441.70349835.109430.1216
9855.624424.14959886.396418.79989927.576416.0953 9968.79407.78069999.703405.9168
10020.29406.642110030.58411.098110051.17415.6463 10123.2413.213110154.08 425.977
10348.78 425.49710379.35437.086910470.92435.331410572.32437.400810602.66451.0058
10713.66450.2695 10834.3458.613410874.48466.328110944.68465.292910978.25466.9563
#Mann= 3 , 0 , 0
 9472.85  0.0474       0 9472.85  0.0474       010978.25  0.0474       0
#XS Ineff= 2 , 0
       0                               0
Bank Sta=9472.85,10978.25
Exp/Cntr=0.3,0.1

Type RM Length L Ch R = 1 ,42002.06,149.471400,149.471400,149.471400
XS GIS Cut Line= 6
791194.697940885779161.094117612791468.936687184779117.711163472
791982.063197689779019.244893259792213.730967543778978.991519923
792505.908071495778939.375170289792715.037129691778920.350498822
#Sta/Elev= 30
9448.697484.16579491.011 481.4879651.403464.27499691.955457.15599732.526 445.603
9796.358432.29819813.878430.79869851.426422.69459915.638418.13619956.401407.9437
9986.973405.064810027.73406.1657 10048.1415.522910058.29416.579910068.48412.6756
10109.23412.446210383.78422.828310393.93424.754510414.23434.706310424.38436.2338
10505.49434.990610606.56436.848810616.67437.900710646.98452.013610737.65451.0566
10838.23453.039410848.27454.979410868.37466.468910878.41468.389410988.87467.8737
#Mann= 3 , 0 , 0
9448.697  0.0514       09448.697  0.0514       010988.87  0.0514       0
#XS Ineff= 2 , 0
       0                10199.35       0
Bank Sta=9448.697,10988.87
Exp/Cntr=0.3,0.1

Type RM Length L Ch R = 1 ,41852.58,149.471400,149.471400,149.471400
XS GIS Cut Line= 6
791204.567808239779289.402393198791492.128807382779252.207205304
792198.580404407779150.624251349792400.506855652779123.243383295
792611.904094278779099.026248775792762.968151211779085.629883357
#Sta/Elev= 30
9436.396464.41949719.166442.36699810.049443.43079890.839440.36229921.136419.1277
9951.432 408.666 9971.63404.264410012.03403.379210032.24404.857610082.77 418.781
10102.98412.3018 10143.4411.990910163.61415.328610173.72414.373610183.82409.5894
10204.03408.760610224.25418.605110244.46422.297110345.51420.722210436.46424.6582
10466.74436.919210557.56435.714610658.44438.827510668.51439.550810678.57451.6954
10688.64453.1919 10899.9455.055610909.94 468.58810919.98470.912411008.29470.3725
#Mann= 3 , 0 , 0
9436.396  0.0543       09436.396  0.0543       011008.29  0.0543       0
#XS Ineff= 2 , 0
       0                               0
Bank Sta=9436.396,11008.29
Exp/Cntr=0.3,0.1

Type RM Length L Ch R = 1 ,41703.11,149.471500,149.471500,149.471500
XS GIS Cut Line= 6
 791214.42823619779417.587956552791593.569249348779378.845492354
791985.014079476779343.412354444792483.732287129779283.383516225
792631.332312494779267.027296786792810.693414641779250.199757237
#Sta/Elev= 30
 9431.67477.00719452.349472.99869522.713470.57589572.974463.53859683.546457.0942
9693.598455.54319703.651448.97739753.911453.22899864.413453.2347 9884.49444.1135
9914.605421.18969954.759 404.87110014.98401.409910065.16409.557710085.24  418.99
10115.38411.064310155.58410.3324 10215.9415.544310266.26413.520110296.47424.3715
10487.84424.610710518.06434.608710638.93432.488310749.68446.062210810.04438.5565
10850.29441.414610920.61461.934210960.78461.468911000.96467.748911036.81466.6932
#Mann= 3 , 0 , 0
 9431.67  0.0485       0 9431.67  0.0485       011036.81  0.0485       0
#XS Ineff= 2 , 0
       0                               0
Bank Sta=9431.67,11036.81
Exp/Cntr=0.3,0.1

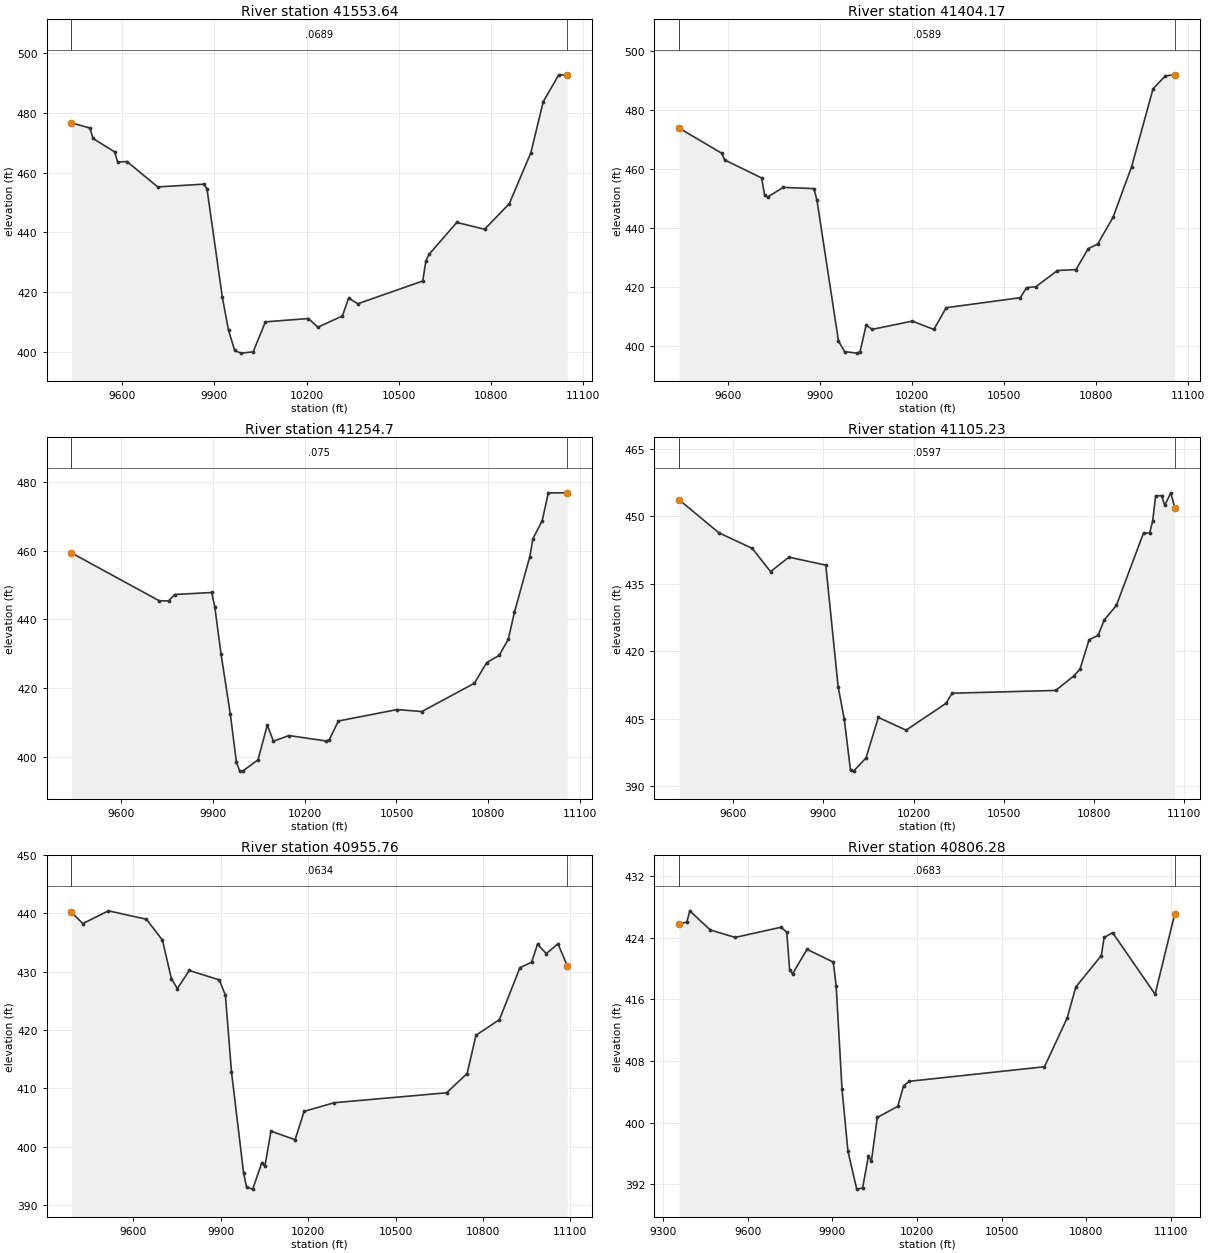
Type RM Length L Ch R = 1 ,41553.64,149.471400,149.471400,149.471400
XS GIS Cut Line= 6
791224.993348011 779554.93441021791583.546281663779523.140523233
 791975.92854531779500.552594755792151.743408945779483.273108244
792562.395488544779434.446744542792832.954175704779407.552242392
#Sta/Elev= 30
9434.203476.65899494.445 474.9069504.484471.41749574.759466.92989584.798463.5038
9614.916463.70099715.308455.19329865.764456.12639875.785454.48369925.866 418.165
9945.887407.15869965.908400.4408 9985.93 399.52310025.97 399.94910066.02409.9987
10206.38411.120710236.52408.208210316.91411.9562   10337417.956110367.16416.0635
10578.64423.688210588.71430.410810598.78432.573610689.41443.301610780.04441.0213
 10860.5449.565110930.89466.693210971.06483.724511021.26492.666511049.32492.7402
#Mann= 3 , 0 , 0
9434.203  0.0689       09434.203  0.0689       011049.32  0.0689       0
#XS Ineff= 2 , 0
       0                               0
Bank Sta=9434.203,11049.32
Exp/Cntr=0.3,0.1

Type RM Length L Ch R = 1 ,41404.17,149.471400,149.471400,149.471400
XS GIS Cut Line= 6
791236.712382917779707.281863968791625.573678388779671.972054618
791936.092842895779651.579167047792124.864334859779631.998990321
792711.014998841779560.243180496792845.548608404779547.490383528
#Sta/Elev= 30
9439.254473.7633 9578.11465.27069588.152462.96629708.645456.88039718.686450.9389
9728.728 450.4339778.933453.67339879.244453.27269889.265449.30659959.411401.6569
9979.452398.074710019.54397.567710029.56397.974210049.61407.045310069.65405.6158
10200.13408.4151 10270.5405.585510310.72412.950210552.59 416.33710572.75419.7554
10602.99420.036410673.55 425.53810733.98425.854510774.24432.958410804.44434.4543
10854.77443.520610915.17460.5917 10985.5487.081711025.67 491.44211056.36 491.786
#Mann= 3 , 0 , 0
9439.254  0.0589       09439.254  0.0589       011056.36  0.0589       0
#XS Ineff= 2 , 0
       0                               0
Bank Sta=9439.254,11056.36
Exp/Cntr=0.3,0.1

Type RM Length L Ch R = 1 , 41254.7,149.471400,149.471400,149.471400
XS GIS Cut Line= 6
  791249.7690298779877.018273435791509.371801914 779848.48886941
791903.527427982779797.311768957792325.570278963 779735.19897324
792553.731927958779704.173306331792856.723387315779671.654593669
#Sta/Elev= 30
9437.913459.31989724.936445.36869755.185 445.3389775.351447.20029896.348447.7907
9906.431443.53119926.597429.95279956.846412.52429977.012398.37599987.095395.9133
9997.178395.755710047.61399.048510077.87409.194210098.05404.461410148.59406.1217
10269.88404.543610279.99  404.8410310.31410.360310502.36413.691610583.12413.1158
10754.69421.363710794.94427.3614 10835.2429.447710865.39434.122810885.51442.0289
10935.83458.2579 10945.9463.472910976.09468.6386 10996.2476.786311058.16476.8195
#Mann= 3 , 0 , 0
9437.913   0.075       09437.913   0.075       011058.16   0.075       0
#XS Ineff= 2 , 0
       0                10372.06       0
Bank Sta=9437.913,11058.16
Exp/Cntr=0.3,0.1

Type RM Length L Ch R = 1 ,41105.23,149.471400,149.471400,149.471400
XS GIS Cut Line= 6
791263.548561315 780056.15218312791652.011728671779998.110430566
792017.014744213779914.762597903792259.284019923779868.478847528
792570.774239396779821.518987252792888.365393145779787.009184294
#Sta/Elev= 30
9419.836453.6973  9552.2446.35059663.386442.87319724.263437.71629785.305 440.926
9907.911439.1565 9948.98412.13699969.546404.86749990.111393.5503 10000.4393.3999
10041.55396.329510082.69405.3266 10174.9402.501810307.54408.451210327.87410.7044
10672.36411.324710732.96414.567310753.15416.076410783.37422.574410813.58423.5742
10833.72426.983610874.01430.1922 10964.5446.3231 10984.6446.263410994.65448.9136
 11004.7 454.548 11024.8454.591211034.84452.405311054.94455.214411068.37451.8984
#Mann= 3 , 0 , 0
9419.836  0.0597       09419.836  0.0597       011068.37  0.0597       0
#XS Ineff= 2 , 0
       0                10372.24       0
Bank Sta=9419.836,11068.37
Exp/Cntr=0.3,0.1

Type RM Length L Ch R = 1 ,40955.76,149.471400,149.471400,149.471400
XS GIS Cut Line= 6
791276.097342032780219.286332418791584.001223208780175.246650522
792039.294028308780054.470491815792259.905897143780004.926131768
792547.054406274779957.694123812792946.754245813779915.680915162
#Sta/Elev= 30
 9387.91440.19639426.996438.26629514.849440.45239645.043 439.0099700.236435.4193
 9730.87428.81529751.364427.11579792.352430.2215 9895.54428.59999916.305425.9666
9937.125412.81989978.767 395.4549989.177 392.99610010.01 392.71310041.27397.2524
10051.69396.630710072.53 402.65310155.47401.194210186.45406.052910289.22407.5341
10675.26409.238110745.86 412.547 10776.1419.104510856.65421.788110927.03430.7015
10967.24431.649410987.35434.744911017.45433.104911057.57434.806211089.42431.0371
#Mann= 3 , 0 , 0
 9387.91  0.0634       0 9387.91  0.0634       011089.42  0.0634       0
#XS Ineff= 2 , 0
       0                10358.93       0
Bank Sta=9387.91,11089.42
Exp/Cntr=0.3,0.1

Type RM Length L Ch R = 1 ,40806.28,149.471400,149.471400,149.471400
XS GIS Cut Line= 6
 791287.10542877780362.391460006791626.398276877780318.099641404
792179.587129635780174.740507497792421.889500517780128.237755396
792721.279380867780088.933046188793014.705411406780065.425150435
#Sta/Elev= 30
9356.708425.72839384.703426.06849394.739 427.497 9467.73425.01049555.765424.0485
9718.162425.3673 9738.65424.72899748.894419.79539759.137419.32819810.356422.5015
9903.362 420.8499913.709417.75949934.525404.33969955.341 396.3359986.566  391.39
10007.39391.544410028.22 395.69910038.63395.043310059.46 400.69310132.03402.1299
10152.75404.818710173.44405.382810651.97407.266610732.61413.608610762.81417.5978
10853.33421.690410863.37424.037610893.49424.6598   11044416.680111113.86427.1325
#Mann= 3 , 0 , 0
9356.708  0.0683       09356.708  0.0683       011113.86  0.0683       0
#XS Ineff= 2 , 0
       0                10343.85       0
Bank Sta=9356.708,11113.86
Exp/Cntr=0.3,0.1

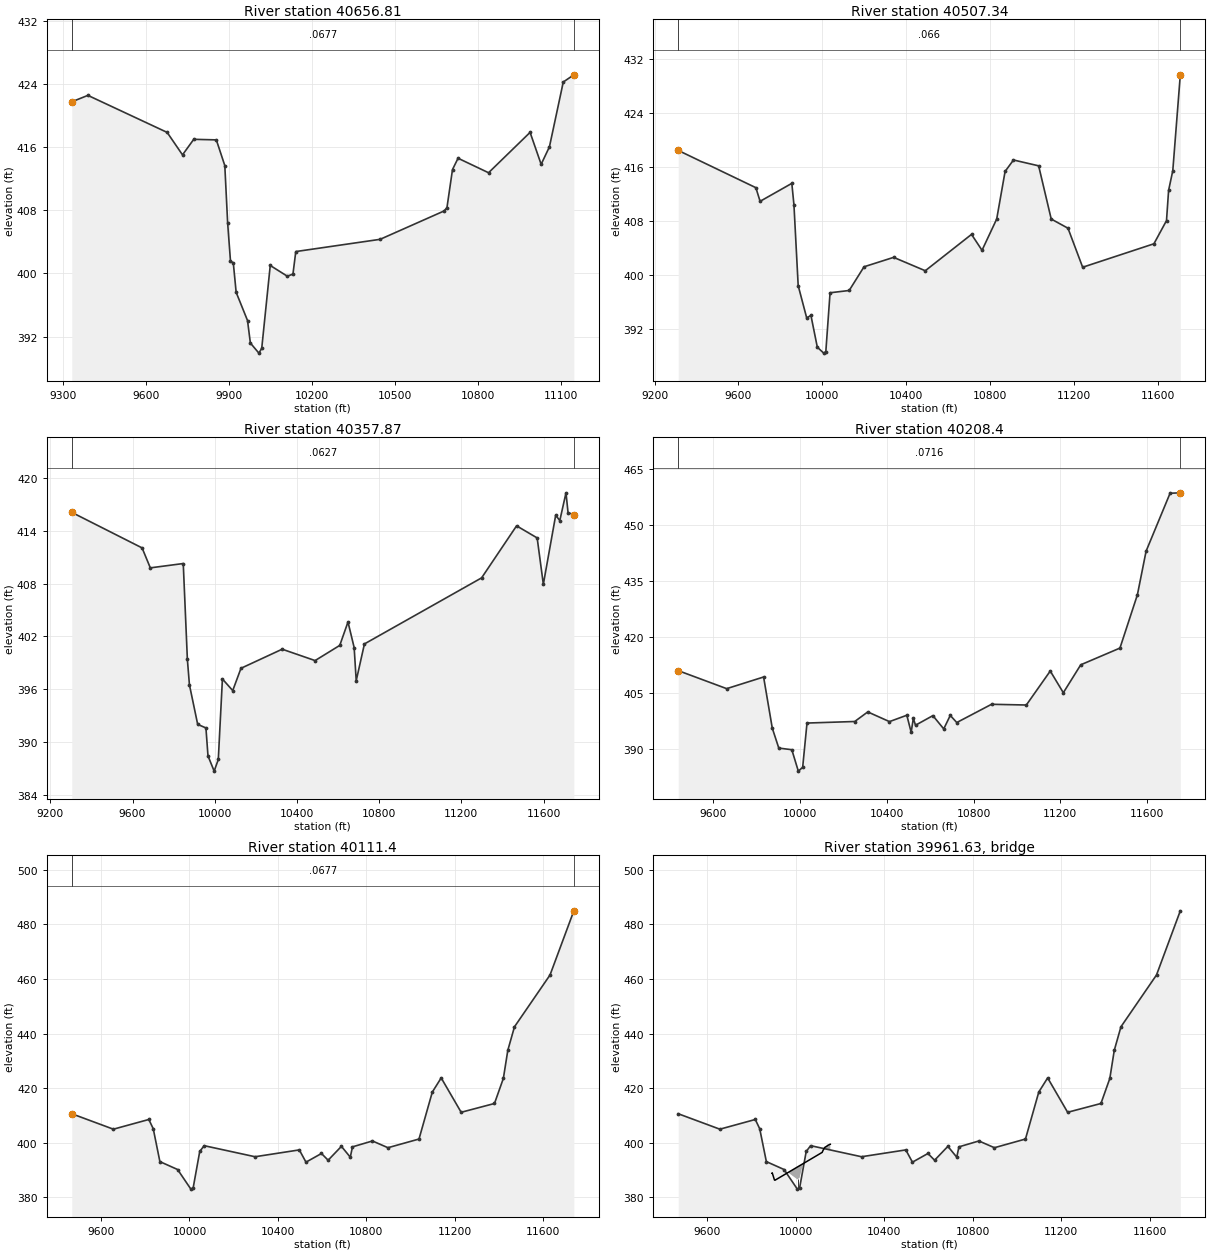
Type RM Length L Ch R = 1 ,40656.81,149.471400,149.471400,149.471400
XS GIS Cut Line= 6
791296.668443259780486.710648353791663.279993161780451.557053613
792217.850857179780329.610961263792456.584869448780290.377151459
792753.259890741780258.156808152793093.238677249780238.489199219
#Sta/Elev= 30
9330.496421.75839388.884422.57319675.797417.87979731.363415.03419772.044417.0036
9853.789416.93249884.498413.67299894.734406.42019904.978401.60189915.269401.3284
 9925.56397.61419966.723 394.0379977.014391.189210007.88389.907210018.15390.5138
10048.97401.016210110.62399.658910131.16399.923210141.44402.779110446.71404.3297
10678.61407.929910688.65408.345310708.74413.173610728.83414.606310839.25412.7686
 10989.6417.883411029.64413.836111059.67416.055911109.73424.2668   11148425.1773
#Mann= 3 , 0 , 0
9330.496  0.0677       09330.496  0.0677       0   11148  0.0677       0
#XS Ineff= 2 , 0
       0                10331.54       0
Bank Sta=9330.496,11148
Exp/Cntr=0.3,0.1

Type RM Length L Ch R = 1 ,40507.34,149.471400,149.471400,149.471400
XS GIS Cut Line= 6
791305.216941299780597.841122857791690.908601274780579.354369846
792273.618925629780489.460644066792642.919497411 780452.68777169
793135.514836608 780434.96726772793690.841661821780444.651257974
#Sta/Elev= 30
9312.663418.42079683.115412.89199703.225410.86969854.662413.53439864.779410.3552
9885.014398.36659925.549393.57959945.844393.94219976.286389.230910006.73 388.348
10016.86388.547410037.14397.301610128.36397.641310199.26401.159110340.52402.5561
10491.43400.570410712.12405.964510762.21403.603610832.29408.245110872.33415.3046
10912.36417.0007 11032.4416.136311092.41408.243211172.42406.878211242.42401.0891
11582.48404.5705 11642.5408.008111652.51412.485911672.52415.421211708.39429.6362
#Mann= 3 , 0 , 0
9312.663   0.066       09312.663   0.066       011708.39   0.066       0
#XS Ineff= 2 , 0
       0                10328.49       0
Bank Sta=9312.663,11708.39
Exp/Cntr=0.3,0.1

Type RM Length L Ch R = 1 ,40357.87,149.471400,149.471400,149.471400
XS GIS Cut Line= 6
791313.068086031780699.906004361791707.584455019780703.498348589
792224.063586017780665.320916482792717.245777427780644.982734475
793251.630704843780652.180477989793753.134353751780678.871779673
#Sta/Elev= 30
 9304.34416.10429646.486412.06229686.508409.79249846.813 410.2849866.873 399.378
9876.902 396.4869917.022391.99189957.141391.58769967.171388.40499997.261386.6739
10017.32387.998510037.39397.153110087.54395.834110127.67398.369710328.12400.5414
10488.33399.247110608.38400.974510648.39403.6367 10678.4400.730410688.41396.9583
10728.42401.140611298.56408.654711468.76414.5725 11568.9413.196111598.95407.9252
11659.04415.775711679.08 415.17311709.15 418.32611719.18416.070511747.38415.8558
#Mann= 3 , 0 , 0
 9304.34  0.0627       0 9304.34  0.0627       011747.38  0.0627       0
#XS Ineff= 2 , 0
       0                10269.29       0
Bank Sta=9304.34,11747.38
Exp/Cntr=0.3,0.1

Type RM Length L Ch R = 1 , 40208.4,97.003100,97.003100,97.003100
XS GIS Cut Line= 6
791452.150080952780800.190381731791829.004984863780824.283600892
792584.004845143780854.473375682792843.525799746780869.773360693
793349.769939116780910.930689148793761.934588222780952.492557486
#Sta/Elev= 30
9438.018 410.9459661.472406.11879831.695409.24089871.729395.53399901.754390.1939
9961.804 389.7589991.828384.018110011.84385.025510031.85396.9022   10252397.3163
10312.05399.884510412.13397.284610492.21398.993110512.23394.431110522.24398.1714
10532.25396.317910612.36398.888310662.45 395.334 10692.5398.948810722.55397.0373
10882.89401.928911043.34401.7345 11153.7410.842711213.94405.026111294.25412.5076
11475.07416.992811555.46431.252111595.65442.960711706.25458.481811753.45458.5927
#Mann= 3 , 0 , 0
9438.018  0.0716       09438.018  0.0716       011753.45  0.0716       0
#XS Ineff= 2 , 0
       0                10226.45       0
Bank Sta=9438.018,11753.45
Exp/Cntr=0.3,0.1

Type RM Length L Ch R = 1 , 40111.4,211.482700,211.482700,211.482700
XS GIS Cut Line= 6
791477.316544029780899.241748077791838.594542405 780921.67778934
792593.594402685 780951.86756413792853.115357288 780967.16754914
793359.359496658781008.324877595793742.049402886781046.750099402
#Sta/Elev= 30
9467.696410.63739655.869404.98569816.087408.53859836.111405.14619866.136393.1238
9946.203  390.2310006.25383.054110016.26383.367310046.28396.824710066.29398.9556
10296.45394.905610496.62397.405610526.65392.920410596.73396.095810626.79393.6287
10686.89 398.70610726.96394.750810736.98398.525410827.13400.675710897.31398.2097
11037.71401.385411097.88418.574311138.01423.755711228.36411.172311378.97414.3927
11419.16423.578511439.26 433.853 11469.4442.461311630.17461.418311737.82484.8935
#Mann= 3 , 0 , 0
9467.696  0.0677       09467.696  0.0677       011737.82  0.0677       0
#XS Ineff= 2 , 0
       0                10210.91       0
Bank Sta=9467.696,11737.82
Exp/Cntr=0.3,0.1

Type RM Length L Ch R = 3 ,39961.63,,,
BEGIN DESCRIPTION:
END DESCRIPTION:
Bridge Culvert--1,0,-1,-1, 0
Deck Dist Width WeirC Skew NumUp NumDn MinLoCord MaxHiCord MaxSubmerge Is_Ogee
90.741350,30.000000,2.6,0, 15, 15, , , 0.95, 0, 0,0,,
 9891.44 9892.63 9902.76 9904.85 9924.61 9924.6110064.6110064.6110118.5110122.44
10130.2410141.2310142.0510153.8610155.39
  388.88  389.03  386.39  386.30  387.24  387.24  393.92  393.92  396.50  397.24
  398.32  398.86  398.98  399.46  399.47
 -611.12 -610.97 -613.61 -613.70 -612.76  382.74  389.42 -606.08 -603.50 -602.76
 -601.68 -601.14 -601.02 -600.54 -600.53
 9891.44 9892.63 9902.76 9904.85 9920.97 9920.9710060.9710060.9710118.5110122.44
10130.2410141.2310142.0510153.8610155.39
  388.88  389.03  386.39  386.30  387.07  387.07  393.75  393.75  396.50  397.24
  398.32  398.86  398.98  399.46  399.47
 -611.12 -610.97 -613.61 -613.70 -612.93  382.57  389.25 -606.25 -603.50 -602.76
 -601.68 -601.14 -601.02 -600.54 -600.53
Pier Skew, UpSta & Num, DnSta & Num=  ,9951.41, 2 ,9947.77, 2 , 0 , 0 , 0 ,,
    4.00    4.00
 -611.48  388.52
    4.00    4.00
 -611.65  388.35
Pier Skew, UpSta & Num, DnSta & Num=  ,9980.21, 2 ,9976.57, 2 , 0 , 0 , 0 ,,
    4.00    4.00
 -610.10  389.90
    4.00    4.00
 -610.28  389.72
Pier Skew, UpSta & Num, DnSta & Num=  ,10009.01, 2 ,10005.37, 2 , 0 , 0 , 0 ,,
    4.00    4.00
 -608.73  391.27
    4.00    4.00
 -608.90  391.10
Pier Skew, UpSta & Num, DnSta & Num=  ,10037.81, 2 ,10034.17, 2 , 0 , 0 , 0 ,,
    4.00    4.00
 -607.35  392.65
    4.00    4.00
 -607.53  392.47
BR Coef=-1 , 0 , 0 ,, 0 ,,,0.8,0,1,0,
WSPro=,,,, 1 ,,,, 0 ,,,, 0 ,,,,-1 ,-1 ,-1 , 0 , 0 , 0 , 0 , 0
BC Design=,, 0 ,, 0 ,,,,,,

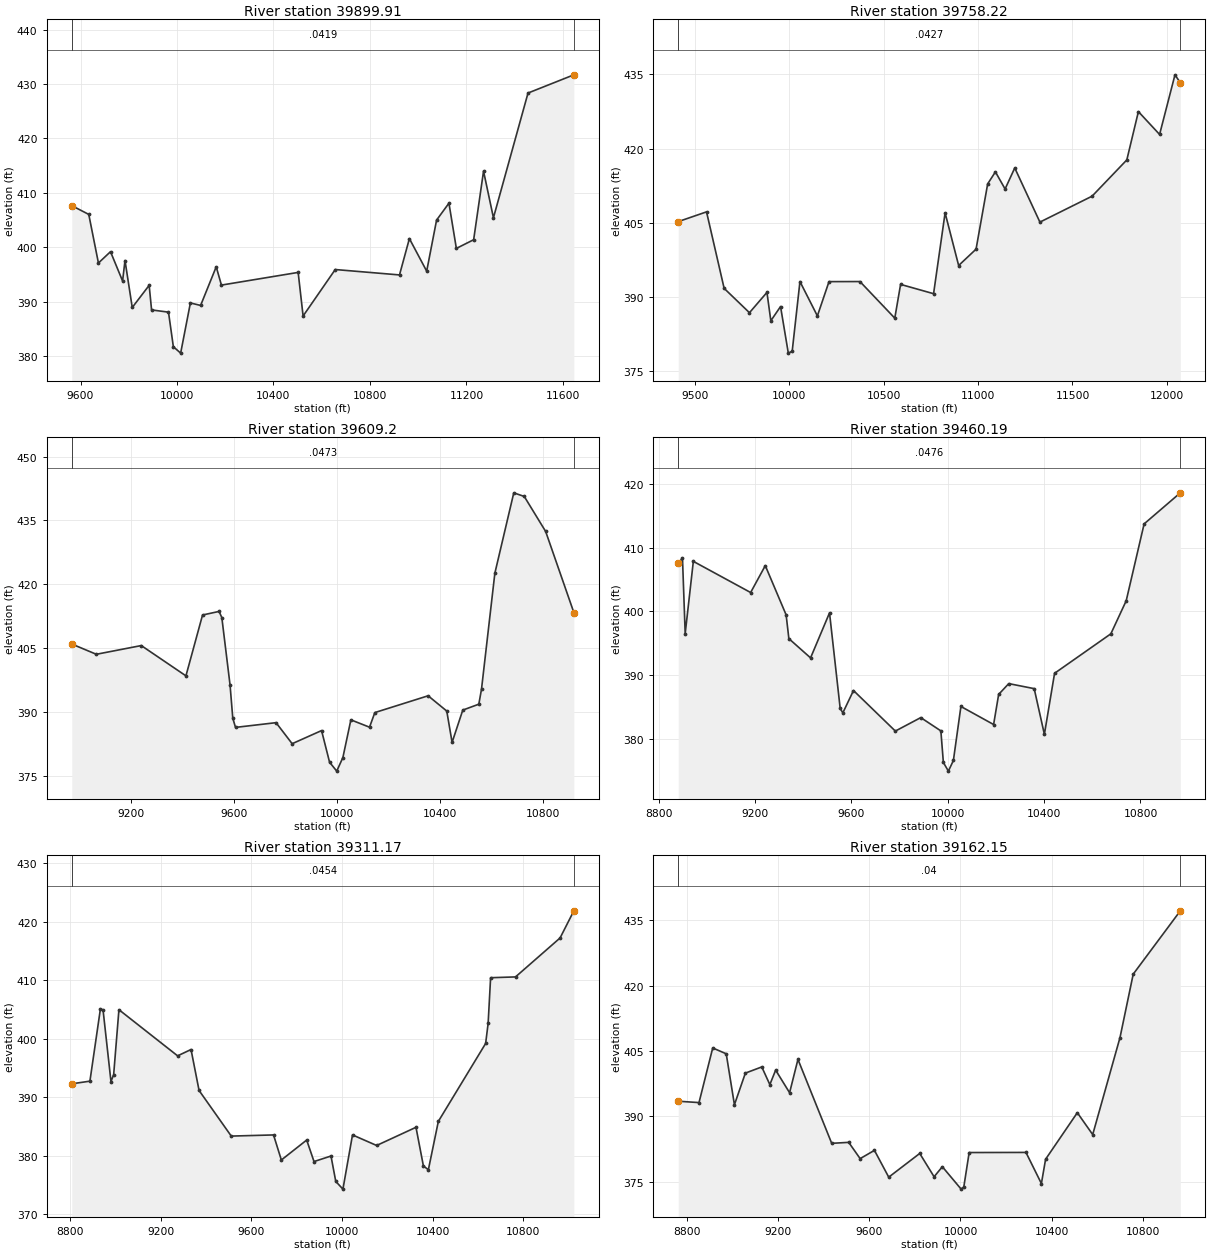
Type RM Length L Ch R = 1 ,39899.91,141.695800,141.695800,141.695800
XS GIS Cut Line= 6
791544.654385477781110.036094889791941.305045426 781132.92840983
792045.615829498781146.653512985792162.842879176781194.122212693
793364.660186499781464.000242487793580.856798652 781509.94723802
#Sta/Elev= 30
9563.776407.64369634.238 406.0339674.305397.08779724.388399.17449774.471393.7825
9784.488397.54519814.538388.90749884.654392.98499894.671 388.4589964.813388.0501
9984.986381.687110015.24380.509610055.59  389.74   10098389.283710162.73396.3938
10184.31393.026410502.45  395.3610522.95387.339310656.19395.888610922.66394.8962
10963.66401.5801 11035.4395.5887 11076.4404.984911127.64408.098311158.39399.7774
11230.13401.373311271.13413.984911312.12405.410611455.53428.362211645.54431.7118
#Mann= 3 , 0 , 0
9563.776  0.0419       09563.776  0.0419       011645.54  0.0419       0
#XS Ineff= 2 , 0
       09823.273        10156.71       0
Bank Sta=9563.776,11645.54
Exp/Cntr=0.3,0.1

Type RM Length L Ch R = 1 ,39758.22,149.015600,149.015600,149.015600
XS GIS Cut Line= 6
791381.334138311781126.693256588791596.767406439781189.227889712
792061.719646863781302.686277456 793345.44504206781590.957446747
793808.242279426781689.313024054793972.780881719781721.071066166
#Sta/Elev= 30
9411.771405.2578 9561.65407.22819654.924391.7717 9789.02386.85429881.669 390.958
9902.243385.22459953.679388.09839994.828378.687410015.38379.071310056.46393.1489
10148.83386.204910210.33393.132810374.31393.149110558.79385.753410589.54392.5742
10764.26390.694910825.27407.022710897.01396.390210989.25 399.69411050.75412.8788
11091.74  415.3111142.99411.847411194.23416.100311327.47405.156811603.76410.3958
11787.78417.722111849.12427.481811961.36422.868612042.83434.914612071.13433.3153
#Mann= 3 , 0 , 0
9411.771  0.0427       09411.771  0.0427       012071.13  0.0427       0
#XS Ineff= 2 , 0
       09840.255         10138.6       0
Bank Sta=9411.771,12071.13
Exp/Cntr=0.3,0.1

Type RM Length L Ch R = 1 , 39609.2,149.015700,149.015700,149.015700
XS GIS Cut Line= 6
 790947.90823475781058.975183635791303.008099198781216.028399945
791451.377903014781275.560375277791623.965487054781336.640857515
791789.295585679781386.573629676792800.435356065781669.463780053
#Sta/Elev= 30
8967.854405.92729063.443 403.5179238.404405.56659412.167398.44459476.817412.7506
9541.195413.59239551.855412.13799583.836396.31029594.496 388.4639605.109386.3292
9762.863 387.4429825.539382.49459939.988385.58299971.117378.1479    9999376.0495
10022.97379.242410054.07388.103710126.62386.377610147.35389.814810354.66393.7616
10427.21390.175710447.99382.8078 10489.6390.399110552.02391.784910562.43 395.309
10614.44422.584910688.06441.471110728.88440.615610812.11432.3882 10921.8413.3311
#Mann= 3 , 0 , 0
8967.854  0.0473       08967.854  0.0473       0 10921.8  0.0473       0
#XS Ineff= 2 , 0
       09845.359        10139.96       0
Bank Sta=8967.854,10921.8
Exp/Cntr=0.3,0.1

Type RM Length L Ch R = 1 ,39460.19,149.015600,149.015600,149.015600
XS GIS Cut Line= 6
790859.375923072781095.512328137791421.386501499 781391.91960363
791656.975013808781496.019917745791770.781612481781534.672010366
792137.638661689781644.605446778792786.658149437781874.591078769
#Sta/Elev= 30
8880.647407.51578898.258408.3705 8909.53396.52388943.346407.83819181.305402.9568
9242.101  407.179328.687399.45399340.024395.7335 9430.13392.71689508.862399.7705
9553.157 384.7899564.198384.1075 9608.36387.60329782.172381.25139887.782383.3614
9971.177 381.2819981.591376.334510002.41374.975710023.22376.646410054.43 385.106
10190.22382.278610211.19386.997710253.15388.686610358.73387.898310401.04380.7429
10443.35390.302710677.03396.487310740.79401.663610815.18413.707710965.47418.5747
#Mann= 3 , 0 , 0
8880.647  0.0476       08880.647  0.0476       010965.47  0.0476       0
#XS Ineff= 2 , 0
       09810.211         10144.5       0
Bank Sta=8880.647,10965.47
Exp/Cntr=0.3,0.1

Type RM Length L Ch R = 1 ,39311.17,149.015600,149.015600,149.015600
XS GIS Cut Line= 6
790795.417189151781121.907996104791501.429066149781556.077355278
 791601.52197509781612.739122164791768.317416329781686.611766158
792027.680130443781779.681921791792770.765870725782111.209450731
#Sta/Elev= 30
8807.242392.27678887.321392.73088933.711405.10228945.308404.91038980.255392.6635
8992.131393.84269015.374404.94899274.373397.05899333.563398.14079369.078 391.137
9511.135383.33829697.729383.53459732.202379.24939844.036382.66179876.357378.9843
 9951.31379.93039972.377375.586310003.97 374.26910046.23383.538610152.74381.7315
 10326.4384.840310359.13378.2294 10381.1377.585110425.05385.849510633.79399.1744
10644.78 402.58910655.76410.417310765.63410.553510962.28417.2124 11023.1421.8541
#Mann= 3 , 0 , 0
8807.242  0.0454       08807.242  0.0454       0 11023.1  0.0454       0
#XS Ineff= 2 , 0
       09778.273        10151.06       0
Bank Sta=8807.242,11023.1
Exp/Cntr=0.3,0.1

Type RM Length L Ch R = 1 ,39162.15,149.015600,149.015600,149.015600
XS GIS Cut Line= 6
 790755.72189695781138.290180186791077.746053743781343.421755276
791251.662051028781466.022060832791710.619205997781805.725682184
792300.855900159782178.934254167792594.800433937782347.929040815
#Sta/Elev= 30
8761.468393.4951 8852.62393.18328912.799405.72458972.066404.38599008.064392.6889
9056.061399.95049128.057401.37059163.447 397.3099188.931400.63629250.106395.4456
9286.811403.10069434.912383.82899509.535384.05129559.676380.31679622.425382.2127
9685.174376.05859821.193381.50429884.212376.15459920.426 378.457 10002.9373.3127
10014.64373.830210038.12381.7134 10287.4381.739410355.06374.591610373.48380.1739
 10512.7390.860710580.25385.839610699.99408.1089   10758422.677510964.66437.2124
#Mann= 3 , 0 , 0
8761.468    0.04       08761.468    0.04       010964.66    0.04       0
#XS Ineff= 2 , 0
       09763.595        10180.06       0
Bank Sta=8761.468,10964.66
Exp/Cntr=0.3,0.1

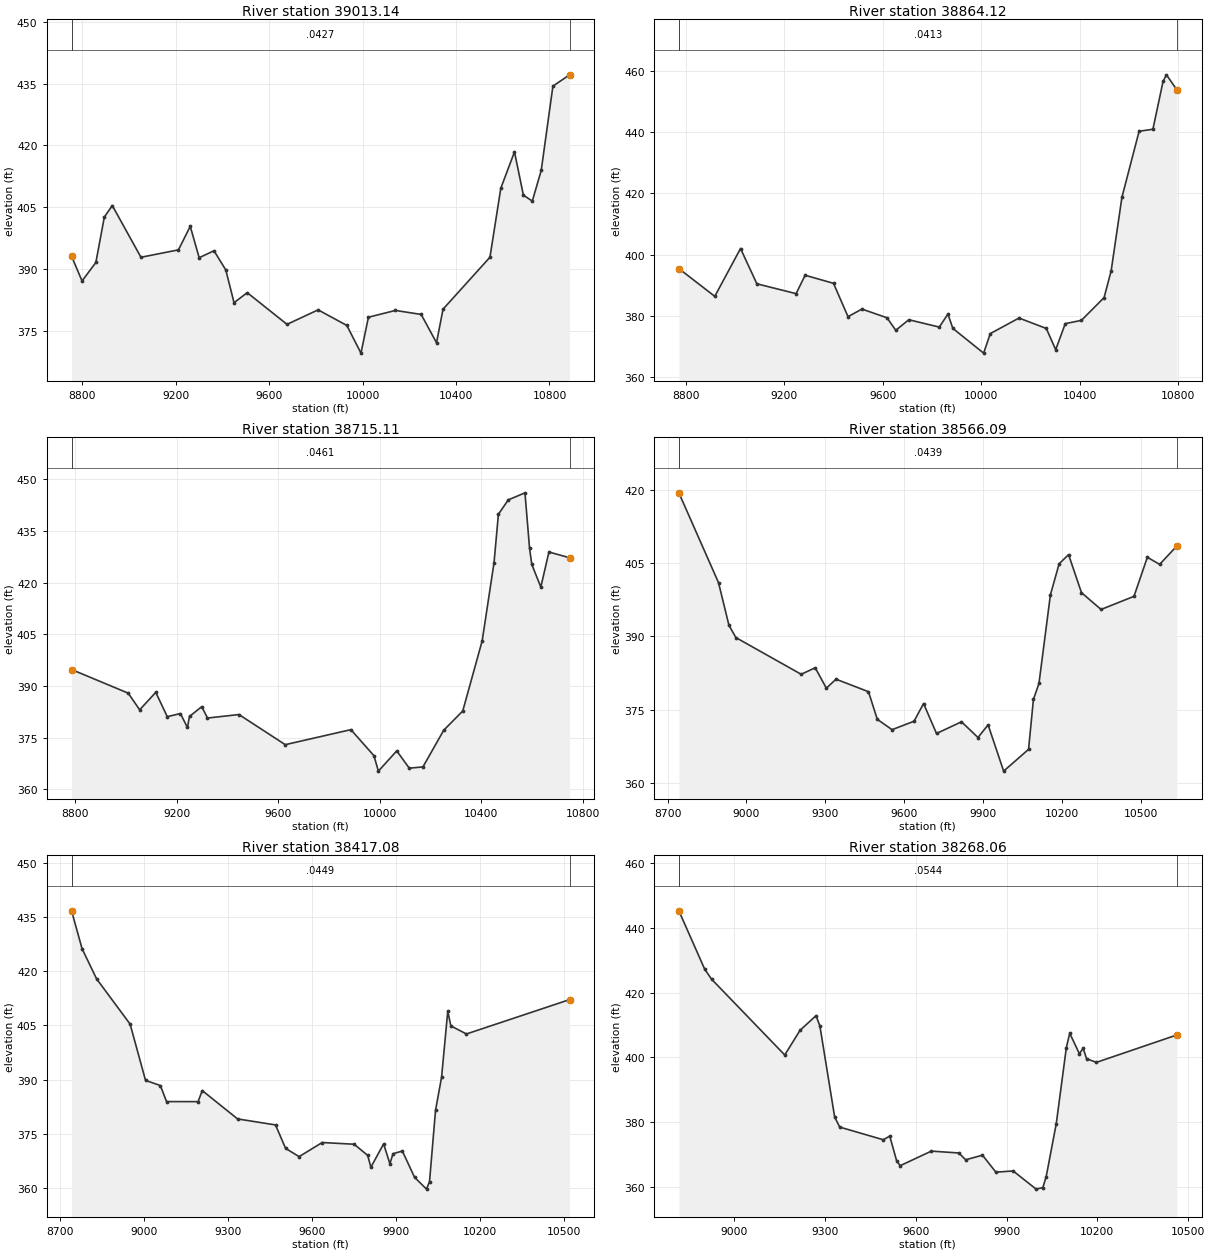
Type RM Length L Ch R = 1 ,39013.14,149.015700,149.015700,149.015700
XS GIS Cut Line= 6
790727.119954588781150.094156399791112.461596557781413.136454957
 791375.95624668 781625.96347879791544.866071309781788.121778396
791885.348390079 782201.99797081792312.563607984782554.848239825
#Sta/Elev= 30
8754.496  393.088799.342387.04768858.537 391.5418894.654402.57188928.815405.3877
 9051.47392.80979211.971 394.6119262.488400.34229300.562392.70329364.019394.3911
9414.628389.72629449.913381.76289506.375 384.2049676.718   376.59809.616380.0235
  9932.6 376.2419993.177369.505110025.05 378.23610140.78379.884610250.78378.9125
10316.54372.028910344.34380.1858 10545.2 392.81910591.71409.6065 10650.2 418.429
10688.33407.908510726.47406.4718 10764.6413.909110814.66434.414410885.77437.1664
#Mann= 3 , 0 , 0
8754.496  0.0427       08754.496  0.0427       010885.77  0.0427       0
#XS Ineff= 2 , 0
       09784.276        10149.06       0
Bank Sta=8754.496,10885.77
Exp/Cntr=0.3,0.1

Type RM Length L Ch R = 1 ,38864.12,149.015600,149.015600,149.015600
XS GIS Cut Line= 6
790674.454349169781171.829168159790976.439315578781388.799240722
 791313.83725472 781695.66107534791424.951459138781829.243054325
791712.255928329782283.107833755792046.109552867782629.642360566
#Sta/Elev= 30
 8771.44395.44818917.237386.39449021.751402.01589088.179390.48589247.462 387.271
9284.126393.28889399.363390.64119458.205379.75539514.767382.24029616.819379.3814
9652.168375.30159705.042 378.7539828.829376.35419863.933380.60719883.854375.9306
10008.93367.849210036.01374.232410152.54379.310910263.46375.908610301.52368.9655
10340.46377.4859 10405.9378.546710498.08385.990510526.73 394.71510570.46  418.72
10640.29440.305310696.29440.963210737.54456.598210751.28458.734410793.46453.8564
#Mann= 3 , 0 , 0
 8771.44  0.0413       0 8771.44  0.0413       010793.46  0.0413       0
#XS Ineff= 2 , 0
       09822.712        10155.31       0
Bank Sta=8771.44,10793.46
Exp/Cntr=0.3,0.1

Type RM Length L Ch R = 1 ,38715.11,149.015600,149.015600,149.015600
XS GIS Cut Line= 6
790582.467262996 781209.79209261790867.650506761781436.423809891
791058.870724755 781625.30260272791253.625880174781865.089820221
791592.571512614782347.750390762791872.582893829782673.676591069
#Sta/Elev= 30
 8786.37394.75399009.698387.89649054.782383.05999118.207 388.1339163.492381.0727
9215.201381.97439242.927377.9412 9251.12381.13959299.327383.97819322.043380.6714
9445.937381.69239628.467 372.9489887.134377.30399977.964369.74459995.473365.2681
10067.81371.148610117.06366.126810170.98366.489710252.99377.138210327.95382.7269
10404.55403.106810451.26425.796410468.39439.807210507.24 443.98610573.07446.0364
10591.02430.053610599.85425.286610635.56418.6836 10667.5428.862810748.67427.1968
#Mann= 3 , 0 , 0
 8786.37  0.0461       0 8786.37  0.0461       010748.67  0.0461       0
#XS Ineff= 2 , 0
       09840.742        10169.66       0
Bank Sta=8786.37,10748.67
Exp/Cntr=0.3,0.1

Type RM Length L Ch R = 1 ,38566.09,149.015700,149.015700,149.015700
XS GIS Cut Line= 6
790477.775864394781252.998066636790717.188570207 781457.58863934
790919.182702182781676.929885397791234.979611122782123.673205773
791372.686529131782267.490635827791697.175733875 782691.30545136
#Sta/Elev= 30
8742.793419.4274 8893.61401.01998933.195392.29348959.584389.77529208.052382.2525
9261.331383.59359303.798379.40519340.477381.25089464.056378.68219497.548373.0252
9553.675370.90629637.362372.63739673.502376.26179722.775370.12419817.796372.5218
9880.521 369.3029919.016371.89869978.145362.4141 10072.9366.876210091.42377.0978
10112.47380.373810155.99398.519210189.15404.890410225.06406.767710274.23398.9753
10348.65395.531910473.89398.220510524.83406.229110571.49404.767610636.93408.5355
#Mann= 3 , 0 , 0
8742.793  0.0439       08742.793  0.0439       010636.93  0.0439       0
#XS Ineff= 2 , 0
       09792.481        10130.61       0
Bank Sta=8742.793,10636.93
Exp/Cntr=0.3,0.1

Type RM Length L Ch R = 1 ,38417.08,149.015600,149.015600,149.015600
XS GIS Cut Line= 6
790415.943035434781278.516376999790712.223764398781550.813936017
 790914.89651341781803.741642183791111.420245226782125.726723382
791278.830033082782483.411475604791429.720224558782718.185402036
#Sta/Elev= 30
8740.582436.7392 8778.05426.26348829.962417.91658949.736405.38019004.901389.7942
9057.815388.38049079.921383.93239192.583383.91549207.594386.9774 9333.67379.1306
 9469.24377.46989505.349370.97739553.495368.68729636.127372.60059750.239372.1205
9798.577369.03789810.005365.75719855.507372.21569877.917366.73089889.123369.5035
9922.466370.2395 9965.98362.974110008.78359.694810019.53361.797610041.03381.5467
10062.54390.661410084.65408.914510095.77404.891310151.37402.645310519.72 412.153
#Mann= 3 , 0 , 0
8740.582  0.0449       08740.582  0.0449       010519.72  0.0449       0
#XS Ineff= 2 , 0
       09766.734        10155.34       0
Bank Sta=8740.582,10519.72
Exp/Cntr=0.3,0.1

Type RM Length L Ch R = 1 ,38268.06,149.015600,149.015600,149.015600
XS GIS Cut Line= 6
  790364.8024479781368.198286377 790597.16049726781597.132869254
790762.962110975781811.577472894 790878.02916277782000.805405395
791147.078536513782548.310085445791255.007898057782735.744429818
#Sta/Elev= 30
8816.905445.20838902.116427.21368924.964424.11229166.788 400.7179217.339408.3331
9270.265412.86449283.011409.62879331.689381.60179348.499378.46649492.251374.5646
9513.817375.68729536.988367.91439548.542366.56839651.304371.05559742.169370.4757
9764.685 368.3749820.239369.79889864.571364.5551 9921.64364.93129997.566359.3223
10019.77359.801410030.88363.201610064.19379.568510097.49403.0262 10108.6407.4278
10140.53401.100810153.09402.781810164.27399.5718 10196.8398.439510462.59406.8992
#Mann= 3 , 0 , 0
8816.905  0.0544       08816.905  0.0544       010462.59  0.0544       0
#XS Ineff= 2 , 0
       09740.718        10132.73       0
Bank Sta=8816.905,10462.59
Exp/Cntr=0.3,0.1