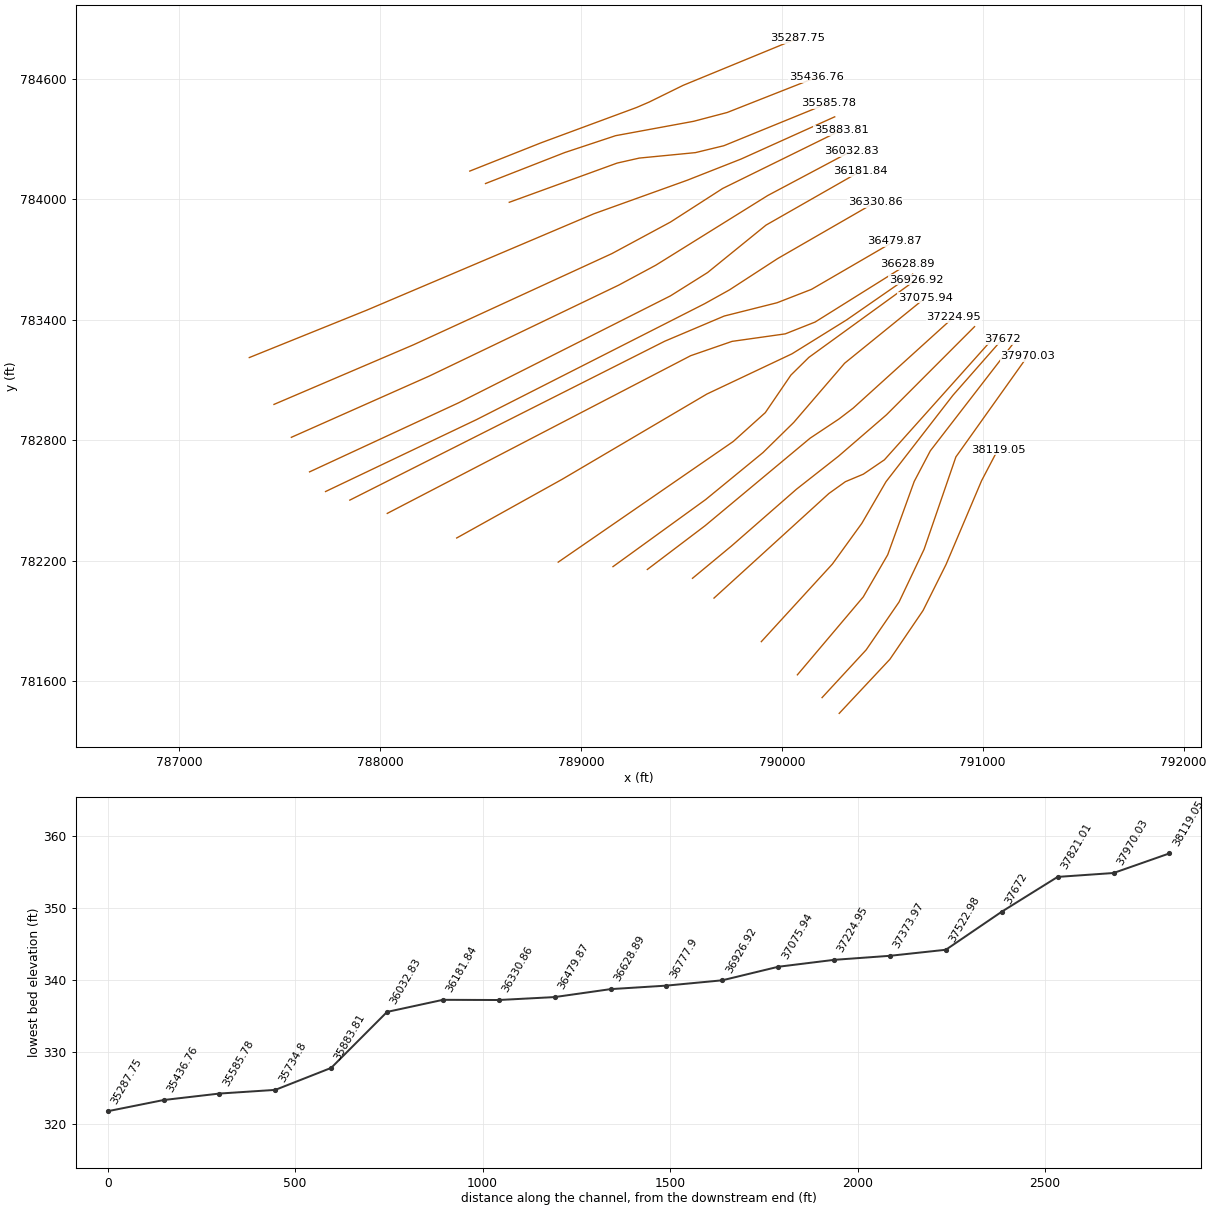
HEC-RAS study 17465_ras.prj: 17465

--- 17465_ras.g01 (geometry) --- (continued)

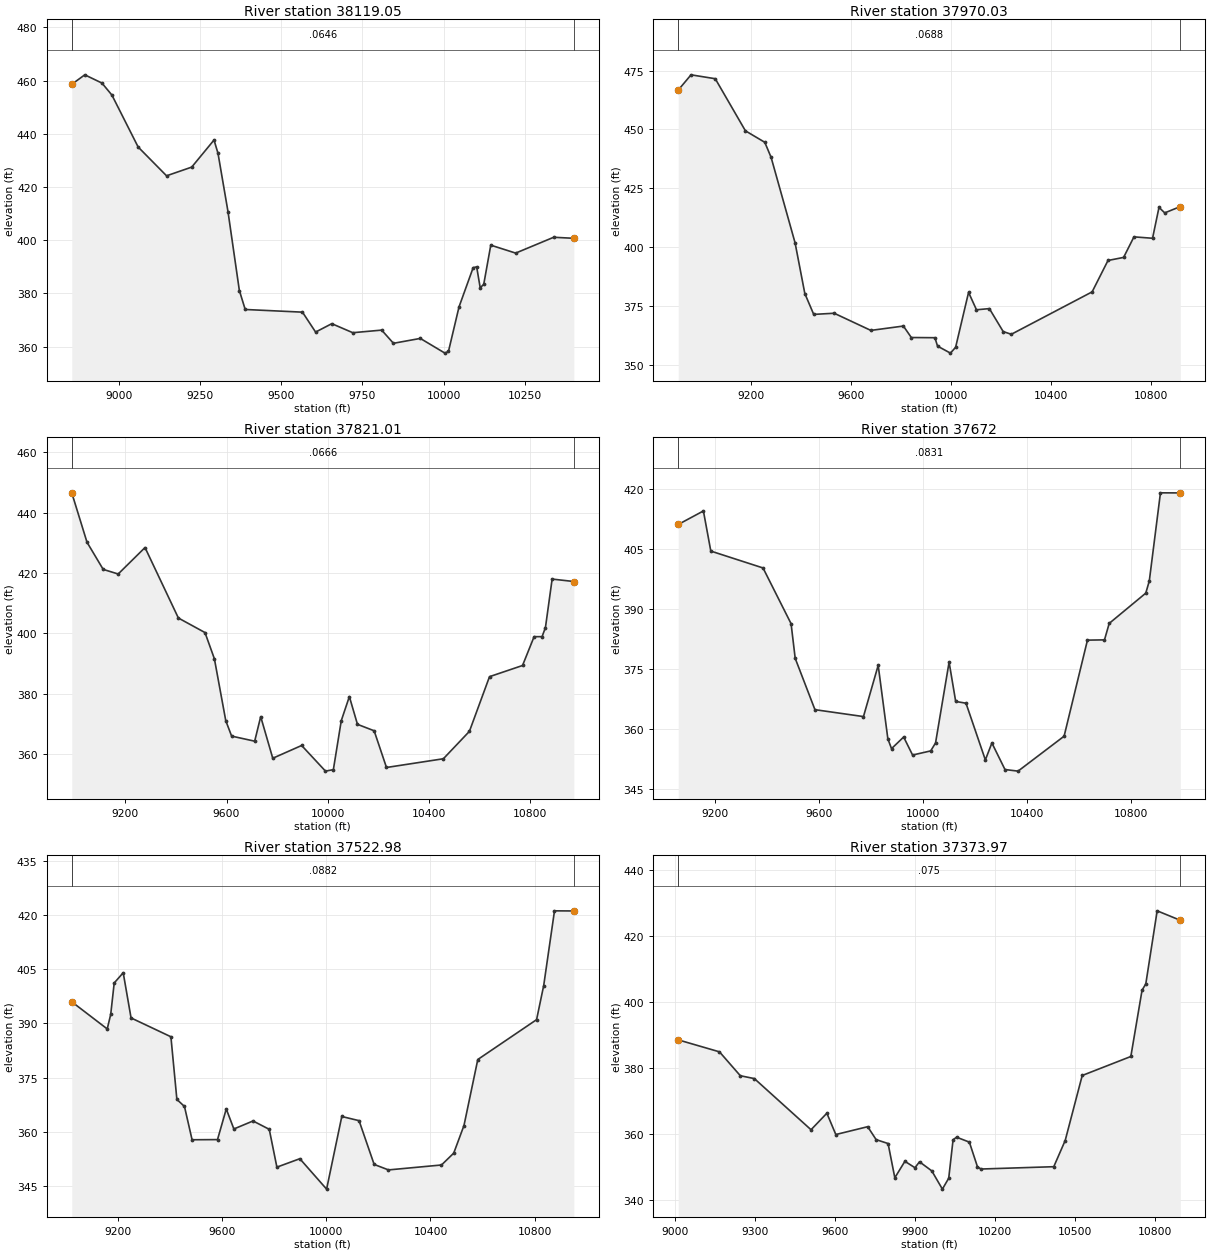
Type RM Length L Ch R = 1 ,38119.05,149.015700,149.015700,149.015700
XS GIS Cut Line= 6
790285.801084711781440.942115847790538.220503684781710.376091716
790703.091110302 781952.89531074790817.579212708782182.118566648
790994.264306167782598.739176913791075.577049234 782753.77768095
#Sta/Elev= 30
 8854.33458.60888894.405462.1705 8947.24459.08178978.056454.55439058.869435.0457
9146.413424.22679223.925427.49379292.651437.66979304.971432.65939335.773 410.732
9370.762381.12029388.763 373.9929565.259372.98749605.695365.50469655.591368.6597
9720.265365.26559809.331366.24199845.565361.2837 9928.35363.118510004.22357.5914
10015.08358.216210047.67374.973410091.13389.686210101.99390.015310112.85382.1901
10123.72383.392810145.48 398.16310222.22395.179410339.24401.125210401.46 400.742
#Mann= 3 , 0 , 0
 8854.33  0.0646       0 8854.33  0.0646       010401.46  0.0646       0
#XS Ineff= 2 , 0
       09712.906        10120.88       0
Bank Sta=8854.33,10401.46
Exp/Cntr=0.3,0.1

Type RM Length L Ch R = 1 ,37970.03,149.015600,149.015600,149.015600
XS GIS Cut Line= 6
790200.539010916781519.450758053790419.852822404781756.929910343
790583.654330273781995.307201923790708.134633688782257.165939249
790866.494144258782717.338226024791224.095858719783219.556119371
#Sta/Elev= 30
8909.966466.7613 8961.17473.24769058.099471.59179178.786449.42989256.301 444.547
9281.554438.14579377.519401.76559416.504380.21489452.034371.34689534.015371.8315
9680.653364.53299810.891366.38749842.651361.50779937.084361.42759947.448357.8575
9999.156354.869310019.87357.363310071.68380.716810103.27373.308310154.88373.8078
10210.22364.034610242.75362.884110566.07380.926310629.56394.280510692.03395.5836
10733.44 404.32510807.83403.728210833.66416.863310856.59414.525810918.91417.2005
#Mann= 3 , 0 , 0
8909.966  0.0688       08909.966  0.0688       010918.91  0.0688       0
#XS Ineff= 2 , 0
       09705.736        10131.61       0
Bank Sta=8909.966,10918.91
Exp/Cntr=0.3,0.1

Type RM Length L Ch R = 1 ,37821.01,149.015600,149.015600,149.015600
XS GIS Cut Line= 6
790077.554589629781632.693839038790405.403596558 782020.47694046
790527.130487568782230.160079088790658.967562822782594.941377677
790739.256902462782747.703909037791149.361344538783278.619496552
#Sta/Elev= 30
 8988.33 446.5179048.546430.1458  9112.5421.15679171.771419.62629277.847428.3911
9409.731405.0445  9514.9400.22669552.055391.54099597.034371.03169620.168365.9306
9711.303364.24719735.088372.37129782.748358.59129896.912362.82579991.126 354.329
 10022.3354.8168 10053.5371.0275 10085.5379.022410117.54369.829210183.46367.6982
10232.23355.534610457.11358.427410560.09367.515610639.48385.620710770.02389.3204
10815.71398.870110847.23 398.87610860.49401.868410887.01417.9466 10972.8417.1384
#Mann= 3 , 0 , 0
 8988.33  0.0666       0 8988.33  0.0666       0 10972.8  0.0666       0
#XS Ineff= 2 , 0
       09731.466        10148.95       0
Bank Sta=8988.33,10972.8
Exp/Cntr=0.3,0.1

Type RM Length L Ch R = 1 ,   37672,149.015600,149.015600,149.015600
XS GIS Cut Line= 6
789898.125274594781797.910931098790251.795317714782184.079376987
790398.866894445782387.490681628790518.591172518782593.823915434
790852.261682295783024.611385152791096.833842753783302.694601534
#Sta/Elev= 30
9058.785411.22319155.503414.60659183.972404.56459384.599400.34049492.399386.3992
9508.252377.71949584.109 364.8779770.578363.1495 9827.14 375.9729864.294357.5863
9878.354355.12359924.991358.03449959.291353.525810029.01354.561110047.56356.5531
10099.61376.763610124.96366.935710164.55366.495610238.95352.301610264.09356.5417
10314.37349.894510364.64349.498610541.56358.239910631.28382.279210696.74382.3467
 10714.9386.468910855.37 394.039 10868.9397.076610911.79419.1424 10988.1419.1194
#Mann= 3 , 0 , 0
9058.785  0.0831       09058.785  0.0831       0 10988.1  0.0831       0
#XS Ineff= 2 , 0
       09796.266        10149.01       0
Bank Sta=9058.785,10988.1
Exp/Cntr=0.3,0.1

Type RM Length L Ch R = 1 ,37522.98,149.015700,149.015700,149.015700
XS GIS Cut Line= 6
789662.659390004782014.726052549790234.235506543782535.132639095
 790316.74564421782594.150972351790405.970343403 782631.51013124
790510.820766603782702.958778627791061.846377986783318.730522884
#Sta/Elev= 30
9024.217395.96779160.192388.47189173.578392.48599186.965401.16839221.519404.0004
9251.603391.51069404.432 386.3079427.341368.99669456.484367.04269485.626357.8533
9583.167357.89779616.767366.3633 9645.91360.83259719.434363.04289781.609360.7416
 9810.92350.28469898.877352.617610001.59344.214110059.84364.279710126.06363.1289
10183.92351.036810238.89349.522710442.23350.884210489.14354.158610528.46361.7917
10581.44380.025410806.89 391.03310834.19400.448910875.62421.100910949.82421.0619
#Mann= 3 , 0 , 0
9024.217  0.0882       09024.217  0.0882       010949.82  0.0882       0
#XS Ineff= 2 , 0
       09780.949        10093.39       0
Bank Sta=9024.217,10949.82
Exp/Cntr=0.3,0.1

Type RM Length L Ch R = 1 ,37373.97,149.015600,149.015600,149.015600
XS GIS Cut Line= 6
789555.668690701782113.242241014789751.308056124782275.376992214
790072.956199765782556.507493552790282.445334094782720.990849141
790520.973225653782926.903715224790959.405463318783365.682608769
#Sta/Elev= 30
9010.812 388.5729165.512384.94619243.672377.71489296.381376.84489508.882361.3564
9568.252366.36479601.851 359.9099721.401362.28189753.084358.3627 9797.89357.1822
9823.165346.81459860.947 351.8019898.729349.85459915.725 351.6569961.859348.8934
10001.59343.375810025.35346.689610041.66358.324910054.78359.098610102.75357.6084
10132.87350.205810145.88349.460910419.34350.167310462.12358.087710526.06377.7884
 10708.4383.542310750.47403.6181 10764.5405.516610807.13427.649310893.95424.7822
#Mann= 3 , 0 , 0
9010.812   0.075       09010.812   0.075       010893.95   0.075       0
#XS Ineff= 2 , 0
       09784.575        10089.24       0
Bank Sta=9010.812,10893.95
Exp/Cntr=0.3,0.1

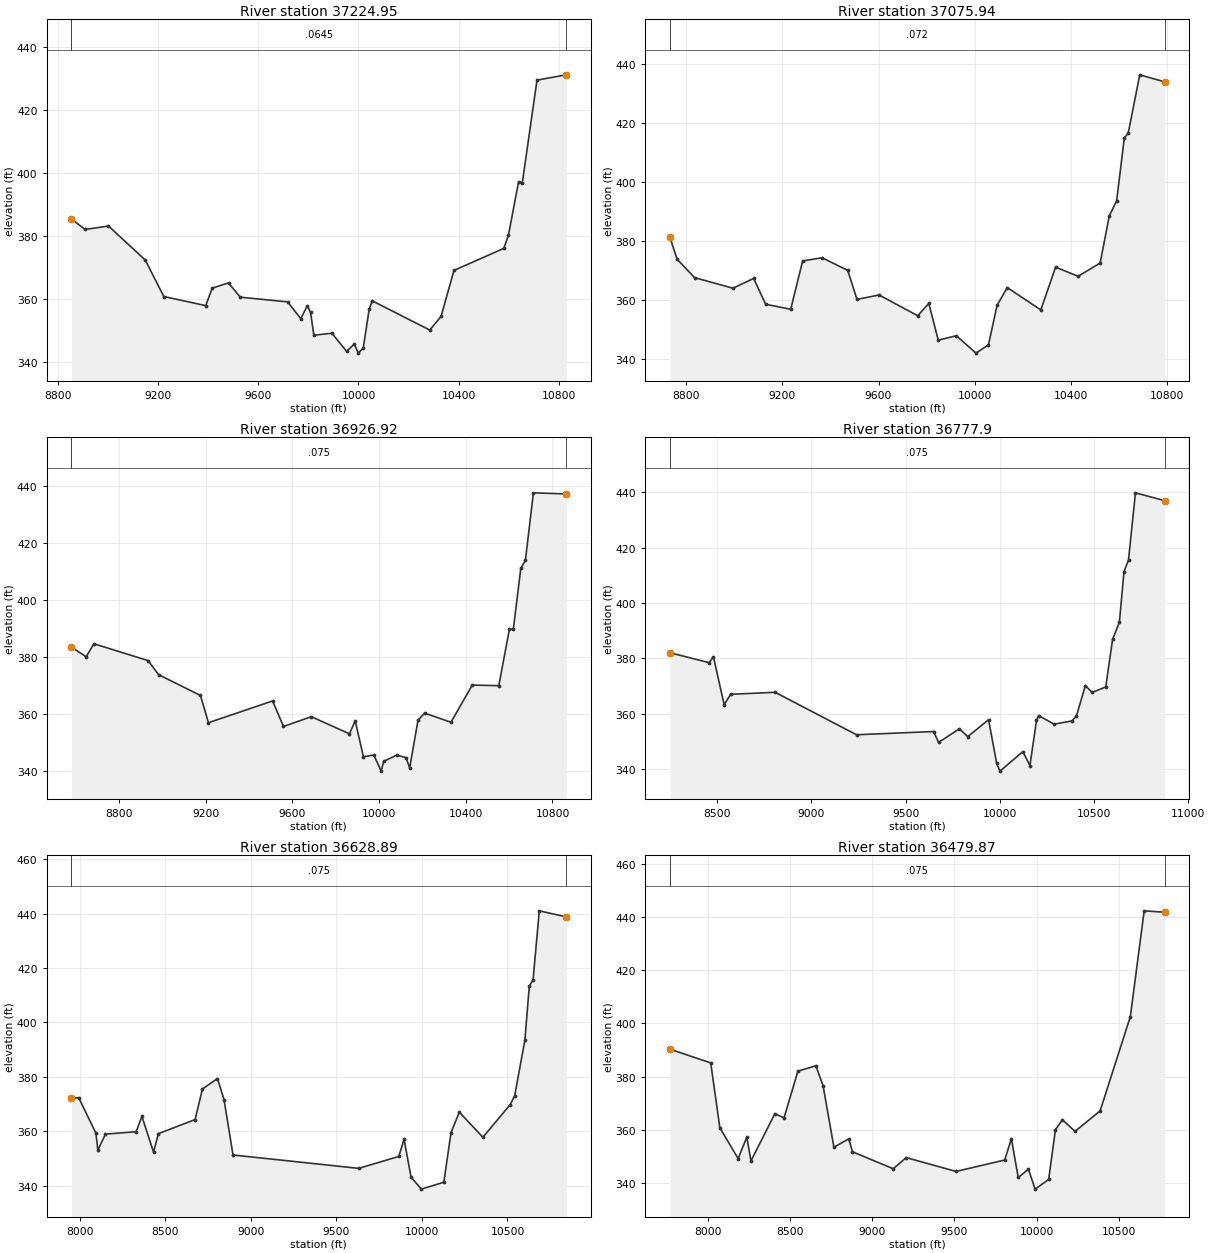
Type RM Length L Ch R = 1 ,37224.95,149.015600,149.015600,149.015600
XS GIS Cut Line= 6
789330.853430372782157.194886482789618.275125104782374.894703187
790141.210622185782810.721813999790284.654349869782906.146350528
790355.073505032782959.933683891790855.677736623  783413.2244835
#Sta/Elev= 30
8852.535385.3976  8907.2382.04019000.707383.13569147.886372.3412  9221.8360.7716
9389.463357.88319415.258363.42229480.473365.08889527.686360.55159716.795359.0737
9769.311353.74239795.569357.85999808.518355.70929821.499348.49539893.906349.1228
9952.636343.35429983.523345.7274    9999342.812910019.06344.439910042.86356.8367
10054.76 359.406 10284.9350.136910330.01354.457210381.57369.048510580.69376.0338
10599.29380.197910639.68397.113510654.42396.636510713.47429.421710830.26431.0954
#Mann= 3 , 0 , 0
8852.535  0.0645       08852.535  0.0645       010830.26  0.0645       0
#XS Ineff= 2 , 0
       09769.466         10098.6       0
Bank Sta=8852.535,10830.26
Exp/Cntr=0.3,0.1

Type RM Length L Ch R = 1 ,37075.94,149.015700,149.015700,149.015700
XS GIS Cut Line= 6
789159.883234898782171.223210213789621.078810377782505.066856143
 789906.37261432782738.880855517790059.271401946782888.751254068
790312.755790186783183.606662262790715.150076425783509.811897441
#Sta/Elev= 30
8731.267 381.1868761.556373.70198834.024367.47298993.992 363.8729080.128367.1942
9129.985 358.4339234.375356.72959284.049373.1218 9364.86374.22149471.849369.9125
9510.464360.0817 9602.26361.58679763.237354.54269809.371 358.7189848.743346.2511
9924.224347.751710005.84341.852610057.94344.679610093.68358.083910136.06 364.082
10275.74356.520810337.45 371.01510431.18367.921810522.81372.410210561.18388.4881
10591.52393.538310623.59414.891610639.62416.437510687.73 436.27310791.65433.8878
#Mann= 3 , 0 , 0
8731.267   0.072       08731.267   0.072       010791.65   0.072       0
#XS Ineff= 2 , 0
       09806.482         10135.5       0
Bank Sta=8731.267,10791.65
Exp/Cntr=0.3,0.1

Type RM Length L Ch R = 1 ,36926.92,149.015600,149.015600,149.015600
XS GIS Cut Line= 6
 788887.18412628 782193.59852169789758.248545549782793.951434166
789917.909827655782937.643922076 790045.22358713783124.380644498
790134.683524457783212.595597477790667.153329576783598.421276246
#Sta/Elev= 30
8579.827383.5603 8647.99380.15058683.514384.7236 8934.08 378.802 8981.91373.8805
  9175.5366.55649212.205356.98879508.355364.63379558.619355.66849686.913359.1029
9862.973353.09479889.505357.66659927.433345.02729975.408345.643210009.46339.9738
10020.86343.412710080.78345.589510124.16344.722410140.83341.104310179.38357.8315
10209.68360.357710331.54357.149210429.65370.209810552.28369.998110601.34389.8935
10619.23389.760710653.78411.249310674.92413.999310711.88 437.74910863.37437.3628
#Mann= 3 , 0 , 0
8579.827   0.075       08579.827   0.075       010863.37   0.075       0
#XS Ineff= 2 , 0
       09887.531        10217.32       0
Bank Sta=8579.827,10863.37
Exp/Cntr=0.3,0.1

Type RM Length L Ch R = 1 , 36777.9,149.015600,149.015600,149.015600
XS GIS Cut Line= 6
788382.045348656782313.812730246788908.147506824782606.694201599
789627.403605117783030.352363008790050.765276813783230.444312836
790322.864272382783399.380147066790651.570308464783627.189930609
#Sta/Elev= 30
8248.987382.00858457.113378.41568479.955380.5397 8537.06363.25858571.323366.9758
8807.553 367.7159239.669352.37359648.578353.54089675.168349.59739785.291354.5372
9830.102   351.79940.241357.82969983.177342.1104   10001339.235910122.34346.2937
10159.79341.245110194.68357.525810206.31359.274810288.38356.203710383.04357.3823
10406.71359.157710454.04370.128210489.83367.6433 10562.3369.657510598.54386.8544
10634.78393.044810658.94411.250510683.09415.560110719.81439.763310875.13436.9316
#Mann= 3 , 0 , 0
8248.987   0.075       08248.987   0.075       010875.13   0.075       0
#XS Ineff= 2 , 0
       09936.173        10232.43       0
Bank Sta=8248.987,10875.13
Exp/Cntr=0.3,0.1

Type RM Length L Ch R = 1 ,36628.89,149.015600,149.015600,149.015600
XS GIS Cut Line= 6
788036.540833588782436.211190734789546.635658373 783221.15937543
789752.737321552783292.411279697790017.267160505783329.748394637
790165.801646172783388.563144743790625.170490198783675.928056643
#Sta/Elev= 30
7952.725372.12847995.448372.30868095.871359.32538107.063353.11078151.831358.9628
8330.901359.82938364.636365.4766 8432.44352.34788460.545359.11218675.239364.3014
8718.178 375.5268805.867379.38948844.336371.59968896.848  351.299630.993346.3729
9865.311350.77039895.888357.11239936.486343.18499996.776338.747510128.25341.2899
10170.07359.513710218.67367.038310356.34357.7954   10516 369.81710542.28 373.126
10601.78393.5486 10627.3413.293510649.48415.655410685.74 440.995 10843.1438.7664
#Mann= 3 , 0 , 0
7952.725   0.075       07952.725   0.075       0 10843.1   0.075       0
#XS Ineff= 2 , 0
       09895.027        10202.73       0
Bank Sta=7952.725,10843.1
Exp/Cntr=0.3,0.1

Type RM Length L Ch R = 1 ,36479.87,149.015700,149.015700,149.015700
XS GIS Cut Line= 6
787850.100207141782502.259663776789417.096731605783292.946058035
789713.565959547783418.477550661789976.392562774783484.581186959
790147.954638149 783551.33840375790562.273169411783792.046187338
#Sta/Elev= 30
7767.939390.30788016.593385.13348072.028360.76028183.561349.13978236.298357.2249
8261.635348.26798406.923366.0018 8463.11364.48488547.029382.02128656.636384.0623
 8700.48376.59298766.677353.39318856.943 356.582 8879.51351.69739127.742345.3163
9206.725349.50579509.783344.29949806.125348.59039846.946356.58039888.628342.0398
9950.732345.09929991.685337.644110073.76341.290210115.16360.002210157.44363.7489
10234.38359.380310387.13367.086710571.24402.594110655.33442.361210780.31441.8299
#Mann= 3 , 0 , 0
7767.939   0.075       07767.939   0.075       010780.31   0.075       0
#XS Ineff= 2 , 0
       0 9841.46        10142.27       0
Bank Sta=7767.939,10780.31
Exp/Cntr=0.3,0.1

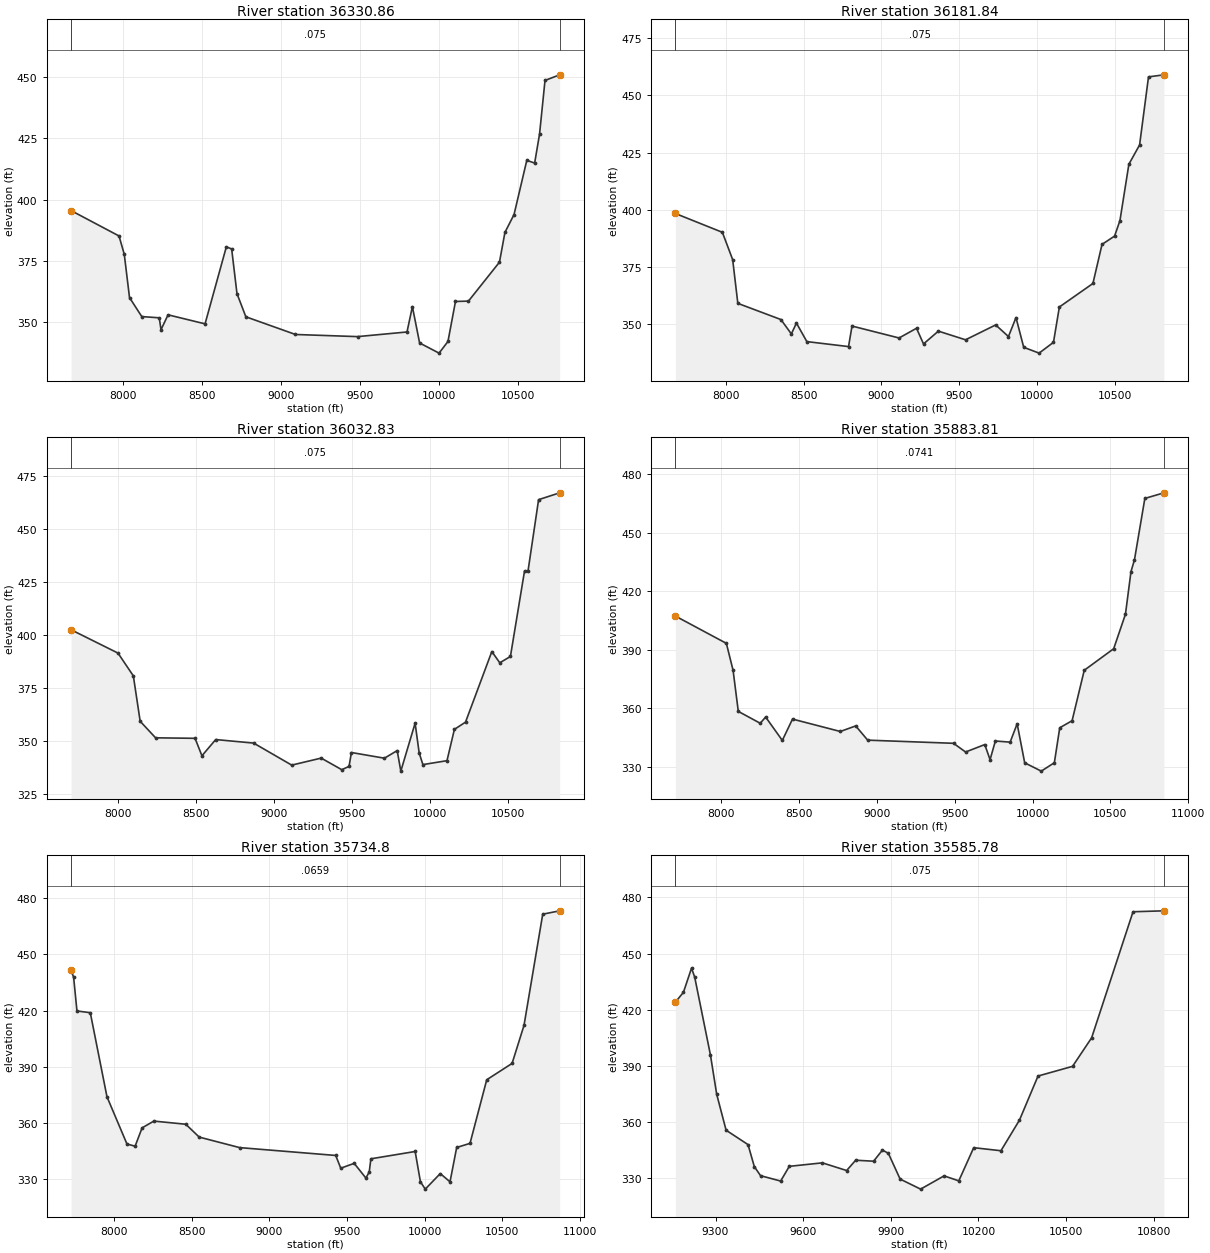
Type RM Length L Ch R = 1 ,36330.86,149.015600,149.015600,149.015600
XS GIS Cut Line= 6
787729.357875275782545.033853089788480.818478617782903.036013996
789615.025147367783479.279638103789739.675766665783548.686871817
789979.191311283783704.336023369790465.163025676783984.390981399
#Sta/Elev= 30
7672.694395.46767976.197385.10118009.431377.62998042.666359.92778120.213352.1758
8230.994351.66368242.111346.79668286.726352.88698521.062349.19318655.816380.6574
8689.505379.80948723.194361.55878779.341352.08219093.769344.85219486.439343.9832
9799.985345.87999833.996356.22739879.814341.3808   10003337.237210059.32342.0019
10106.91358.3416 10189.1358.487910385.49374.4017 10420.1386.564810477.77393.8504
10558.52415.9816 10608.3 414.89510639.27426.698110673.88 448.64210766.65 450.935
#Mann= 3 , 0 , 0
7672.694   0.075       07672.694   0.075       010766.65   0.075       0
#XS Ineff= 2 , 0
       09831.125        10126.48       0
Bank Sta=7672.694,10766.65
Exp/Cntr=0.3,0.1

Type RM Length L Ch R = 1 ,36181.84,149.015600,149.015600,149.015600
XS GIS Cut Line= 6
787649.776235199782642.901018816 788391.38257098782986.530696006
789446.155047391783519.022710502789630.585609086783634.812386914
789921.557463501783871.022107791790391.729828067784139.268270904
#Sta/Elev= 30
7677.533398.37447979.346390.1266 8045.45378.15628078.502359.03558354.801351.9634
8421.941345.67498454.592350.41678521.267342.3089 8788.88340.12598811.181349.1097
9113.068 343.8959225.062348.1403 9269.86341.28079365.211346.88989539.507343.0956
9732.867349.59749814.944344.52029863.226 352.8179912.837339.807610011.56337.2627
10103.79341.9961 10141.6357.450110356.82367.738910415.32384.855210495.94388.4813
10530.31395.282310587.59419.923710656.32428.358810713.53458.1455 10812.3459.0409
#Mann= 3 , 0 , 0
7677.533   0.075       07677.533   0.075       0 10812.3   0.075       0
#XS Ineff= 2 , 0
       09860.321        10164.77       0
Bank Sta=7677.533,10812.3
Exp/Cntr=0.3,0.1

Type RM Length L Ch R = 1 ,36032.83,149.015700,149.015700,149.015700
XS GIS Cut Line= 6
787559.129256209782814.817703109 788245.89589613783119.867502907
789188.604728942783572.419688767789372.882114965783671.427359774
789930.191888831784018.307979963 790344.67222824784238.517026907
#Sta/Elev= 30
7700.901 402.3858001.689  391.368100.039 380.583 8143.75359.14418242.559351.3227
 8495.59351.08988539.769342.83538628.128350.50258871.391348.82659115.357338.4259
  9304.4341.7405 9436.38336.25599482.961337.81949498.143  344.389709.821341.6911
9791.558345.28739814.911335.58349906.458358.23479932.668 344.1369956.412338.6683
10110.85340.519210158.36355.322910229.63358.725510398.33392.082710449.39386.7743
10517.55389.759110607.85 430.08410630.43430.160610698.16463.868410833.24467.0983
#Mann= 3 , 0 , 0
7700.901   0.075       07700.901   0.075       010833.24   0.075       0
#XS Ineff= 2 , 0
       0 9882.87        10182.05       0
Bank Sta=7700.901,10833.24
Exp/Cntr=0.3,0.1

Type RM Length L Ch R = 1 ,35883.81,149.015600,149.015600,149.015600
XS GIS Cut Line= 6
787472.738394843782978.662440183788167.503469299783275.580492124
789154.857792258783729.391277635789446.254302172783886.340837081
789705.930533656784053.473326667790295.048584103784343.177803635
#Sta/Elev= 30
7704.861407.3248 8032.69393.31338075.903379.47458109.343358.43398250.172 352.352
8285.046355.53528392.176343.55438457.716354.49558764.798348.1357 8863.67350.9862
8940.678343.6918 9492.01342.0791 9569.62337.61659692.941341.42869726.849333.6755
9760.891343.24999855.809342.67119900.929352.08339949.336 332.07510055.87327.8122
10139.97332.118210174.58350.045810253.86353.6512   10332379.5216 10521.1390.5631
10596.67408.244810632.33430.122710654.57436.127110721.31467.611810843.72 470.481
#Mann= 3 , 0 , 0
7704.861  0.0741       07704.861  0.0741       010843.72  0.0741       0
#XS Ineff= 2 , 0
       0  9886.8        10202.81       0
Bank Sta=7704.861,10843.72
Exp/Cntr=0.3,0.1

Type RM Length L Ch R = 1 , 35734.8,149.015600,149.015600,149.015600
XS GIS Cut Line= 6
 787349.83223142783211.760336334787935.487365922783448.126369182
  789064.1480577783927.178227322789529.643575732784094.436985591
789797.537322205784199.901853382790263.394644715784409.938839436
#Sta/Elev= 30
7720.184441.53117736.499  437.797758.012419.79317844.061418.85917951.623374.0176
8080.651348.80478133.228347.67458178.219357.43378253.909361.04618459.753359.3767
8546.577352.51358807.517346.90459427.182342.72119459.673335.91619546.314338.5131
 9621.82330.67599643.331333.88819654.086340.93159939.684344.83489973.629328.6764
10004.87324.758810101.62333.052910164.52328.662110207.51346.971310293.48349.1702
10401.42383.101810564.91391.8182 10641.8412.088310762.63471.421710871.78473.2072
#Mann= 3 , 0 , 0
7720.184  0.0659       07720.184  0.0659       010871.78  0.0659       0
#XS Ineff= 2 , 0
       09921.322        10231.02       0
Bank Sta=7720.184,10871.78
Exp/Cntr=0.3,0.1

Type RM Length L Ch R = 1 ,35585.78,149.015700,149.015700,149.015700
XS GIS Cut Line= 6
788643.696885643783984.564481619789180.366480829784179.664948895
 789290.70021829784204.597958637789570.364923012784231.825833107
789711.616965304784266.089416267790231.097250334784478.056980315
#Sta/Elev= 30
9162.501424.03239190.192429.31499217.888 442.2069228.684437.49999282.664395.8866
9304.133374.83239336.299 355.6959411.351348.01429432.795336.30449454.221331.4265
9523.033328.55949552.627336.41659665.755338.27799748.933334.17659779.827339.6762
9841.193339.15439871.521345.10649891.698343.37519932.052329.608510002.19324.2486
10082.38331.317310132.89328.670110183.94346.373710277.18344.7424 10340.6361.0933
10404.08384.624610522.35389.801410587.57405.012410729.36472.331910835.03472.8245
#Mann= 3 , 0 , 0
9162.501   0.075       09162.501   0.075       010835.03   0.075       0
#XS Ineff= 2 , 0
       09878.659        10192.72       0
Bank Sta=9162.501,10835.03
Exp/Cntr=0.3,0.1

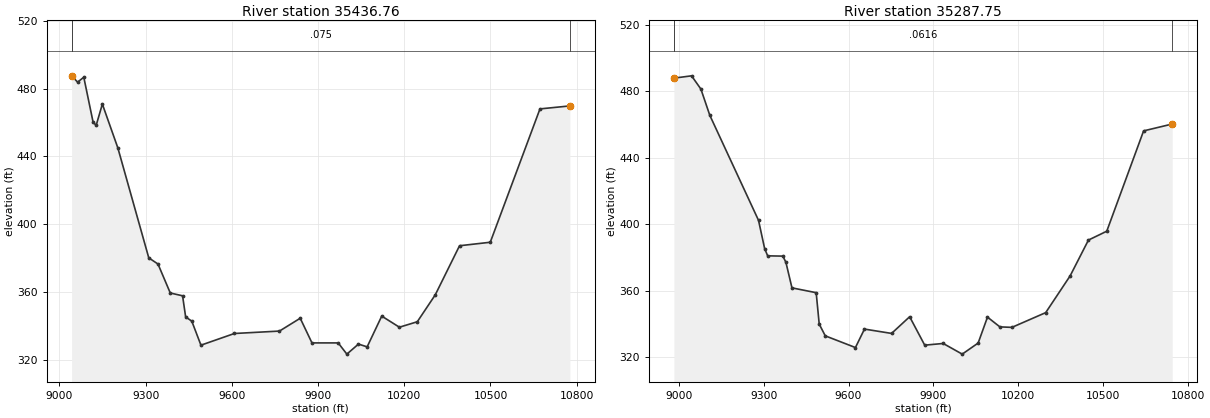
Type RM Length L Ch R = 1 ,35436.76,149.015600,149.015600,149.015600
XS GIS Cut Line= 6
788525.545692995784077.903923811788919.401082997784231.986651839
789172.918771609784316.093761383789561.343033476784387.667246065
789728.308455617784431.546773149790170.502897212784605.855979631
#Sta/Elev= 30
 9042.59487.54329063.535  483.829085.068486.71869117.367460.25919128.134 458.313
9149.666470.86999203.499445.04939311.163380.1428 9343.24376.50139385.998 359.414
9428.756357.76119439.445345.30969460.824342.79919492.678 328.631 9609.07 335.519
9765.915336.9507 9838.09344.52129878.975329.9675 9970.18329.968710000.39323.3484
10040.72329.267110070.97327.641610121.72345.785310183.16339.228410245.46342.4528
10307.93  358.3210392.41387.293510499.33389.352710672.25 468.02810776.39469.7947
#Mann= 3 , 0 , 0
 9042.59   0.075       0 9042.59   0.075       010776.39   0.075       0
#XS Ineff= 2 , 0
       09832.735        10133.23       0
Bank Sta=9042.59,10776.39
Exp/Cntr=0.3,0.1

Type RM Length L Ch R = 1 ,35287.75,149.015600,149.015600,149.015600
XS GIS Cut Line= 6
 788447.11337867784139.865452128788802.192521185 784280.70946689
 789277.55876717784456.553963065789339.865435362784483.399505943
789508.949209064784566.608460739790078.178306937784800.576933742
#Sta/Elev= 30
8982.979487.82029045.253489.2137 9078.27481.26719109.801465.46289281.928402.2763
9303.444385.33699314.202380.92639367.975380.75119378.672377.02239400.068361.6595
9485.649358.75019496.346339.86079517.742332.7941 9624.32325.75419656.249336.8577
9752.035334.25119815.892344.28749869.107327.18849934.376328.206910001.65321.7944
10057.92328.471710090.88344.055210134.71338.186510177.17337.893110296.54346.7542
10382.86368.860310447.59 390.41210512.32395.738410642.47456.091210743.63460.2235
#Mann= 3 , 0 , 0
8982.979  0.0616       08982.979  0.0616       010743.63  0.0616       0
#XS Ineff= 2 , 0
       09822.161        10104.74       0
Bank Sta=8982.979,10743.63
Exp/Cntr=0.3,0.1