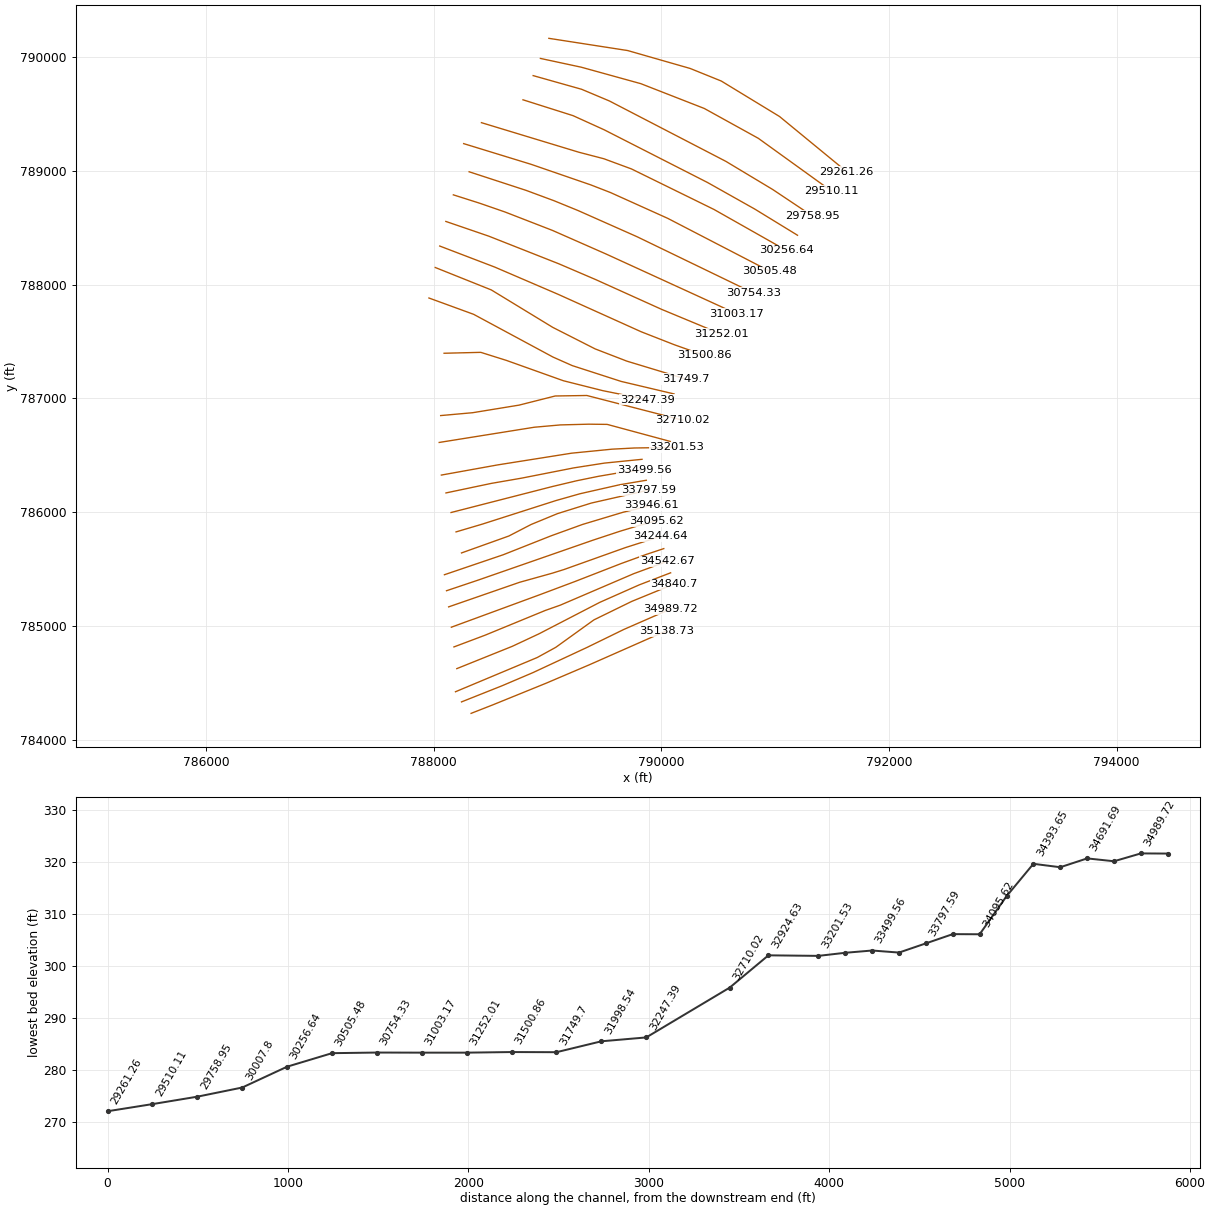
HEC-RAS study 17465_ras.prj: 17465

--- 17465_ras.g01 (geometry) --- (continued)

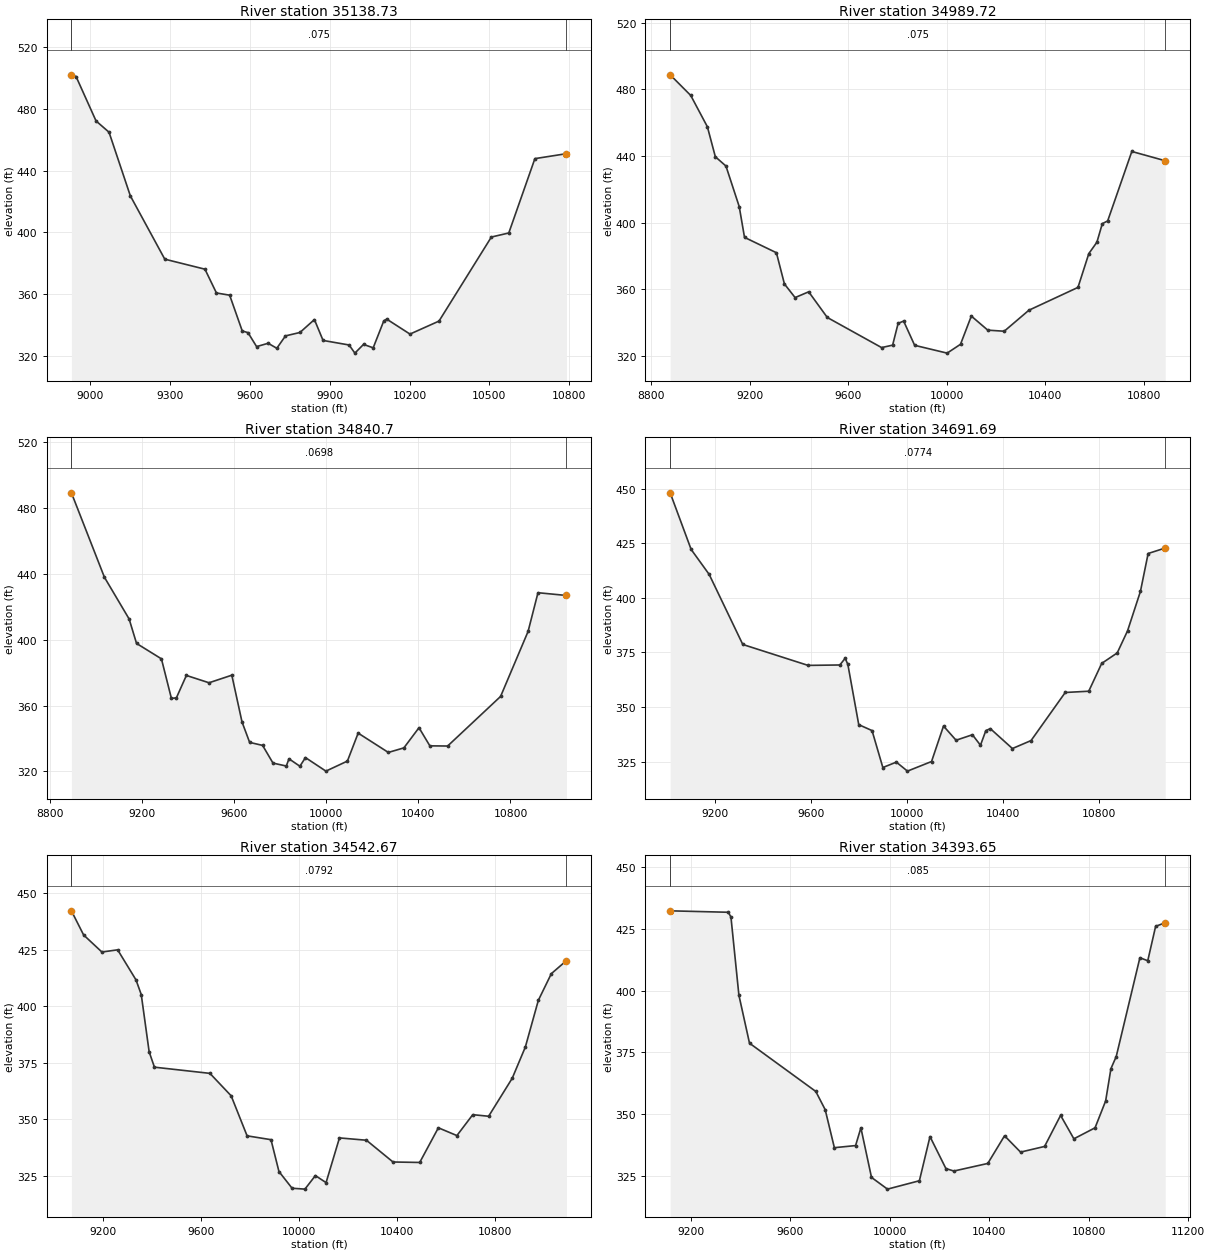
Type RM Length L Ch R = 1 ,35138.73,149.015600,149.015600,149.015600
XS GIS Cut Line= 6
788328.738962064784233.381241247788518.426801756784307.716157421
788987.102737025784498.048179368789366.188346289784659.598014198
789901.978955074784896.183059467790044.444990796784956.472354599
#Sta/Elev= 30
8928.375502.1214 8945.84501.01999021.023472.20059069.849464.89859149.996423.6169
9279.514382.55349430.618376.05549473.791360.62189523.548359.19149570.929335.9753
9592.515334.89939624.895325.83629668.297327.99739700.923324.75419733.549332.7858
9787.926335.00239842.303343.3714 9874.93329.83619972.808326.88669994.559321.6075
10027.07327.267910063.41325.047810103.39342.576210114.32343.664810201.78333.9626
10310.97342.390110507.86396.902910573.45399.543210671.59447.763910790.43450.9766
#Mann= 3 , 0 , 0
8928.375   0.075       08928.375   0.075       010790.43   0.075       0
#XS Ineff= 2 , 0
       09843.268        10117.62       0
Bank Sta=8928.375,10790.43
Exp/Cntr=0.3,0.1

Type RM Length L Ch R = 1 ,34989.72,149.015700,149.015700,149.015700
XS GIS Cut Line= 6
788244.623698686 784334.19618047788601.192222105784476.046746684
788871.898177652 784591.29375564789347.269876951784812.814933617
789670.875213098784970.789368179790080.096666225785149.741963497
#Sta/Elev= 30
8877.345488.75298960.878476.35319028.398457.55359060.688439.56089103.742 433.981
9157.559409.66329179.086391.15389308.564381.92569341.073363.18039384.417354.9933
9439.582358.46159515.061 343.0559735.547324.96739780.249326.4405  9802.6339.5244
9824.951340.87849869.653326.328710001.55321.6392 10055.8326.951210099.69343.8919
10166.45335.437810233.22334.787710333.37347.4028 10532.6361.1113 10576.6381.4133
10609.43388.241910631.28399.362810653.13401.048110751.12442.730710886.75 437.156
#Mann= 3 , 0 , 0
8877.345   0.075       08877.345   0.075       010886.75   0.075       0
#XS Ineff= 2 , 0
       09834.164        10103.11       0
Bank Sta=8877.345,10886.75
Exp/Cntr=0.3,0.1

Type RM Length L Ch R = 1 , 34840.7,149.015600,149.015600,149.015600
XS GIS Cut Line= 6
788191.758560655784423.406100874788909.655453054784724.087712832
789072.644154088784813.476304519789408.217347624785054.933554585
789740.743199498785217.445484823790110.108158841785368.642274575
#Sta/Elev= 30
8894.605489.32179037.795437.99769144.974412.64399177.234397.7628 9285.25388.3888
9328.533364.32479350.174364.69359393.496378.30579491.699373.84649590.661378.4483
 9634.87350.05749668.027337.59869724.262335.7711 9769.33325.01519827.103323.2248
9838.685327.61629886.115323.09949910.263328.3631    9999320.128510092.27326.2375
10138.94 343.23610269.91331.4906 10337.4334.264710402.94 346.52710450.09335.4966
10527.26335.391610757.08365.544710876.35405.051510919.33428.597911042.99 426.918
#Mann= 3 , 0 , 0
8894.605  0.0698       08894.605  0.0698       011042.99  0.0698       0
#XS Ineff= 2 , 0
       0 9869.12        10143.32       0
Bank Sta=8894.605,11042.99
Exp/Cntr=0.3,0.1

Type RM Length L Ch R = 1 ,34691.69,149.015600,149.015600,149.015600
XS GIS Cut Line= 6
788203.383393364784626.501763673788690.938991801784822.580225501
788925.718755789 784932.54912529789459.318408183785208.780409826
  789805.5110956785362.160274729790081.865278244785468.393725199
#Sta/Elev= 30
9014.424448.07829101.687 422.1669176.759410.73399316.651378.65679588.374369.0798
9720.638369.27279742.876372.34389753.995369.5032 9799.27341.95479854.643339.2346
9899.588322.3284 9955.77324.801810002.05320.677510102.31325.0775 10152.1341.3202
10204.36334.8203 10272.4337.332710305.94332.526110328.29339.225410346.89 340.134
10438.87331.019910516.56334.675310658.75356.681210756.57357.258210810.58369.9963
10875.12374.785810918.15384.917610971.74402.9602 11003.8420.301811074.95422.8137
#Mann= 3 , 0 , 0
9014.424  0.0774       09014.424  0.0774       011074.95  0.0774       0
#XS Ineff= 2 , 0
       09882.504         10163.2       0
Bank Sta=9014.424,11074.95
Exp/Cntr=0.3,0.1

Type RM Length L Ch R = 1 ,34542.67,149.015700,149.015700,149.015700
XS GIS Cut Line= 6
788178.215671743784817.166321462788452.905547756 784920.67052989
788980.764981984785137.688158429789111.256791301785183.621095081
789758.604945123785461.101502559790053.296331951785569.296812108
#Sta/Elev= 30
9069.898 442.1589119.713431.47349194.376423.91639258.619424.8987 9333.57411.5805
9354.984405.09989387.253379.7411  9408.8372.95459635.298370.21559722.008360.2784
9787.041342.5635 9884.59340.86639917.106326.77439970.725319.370110023.13318.9773
 10065.9324.974710109.49321.857810164.13 341.647 10274.3340.616810382.71 330.988
10491.75330.780910567.89346.127410643.57342.679610708.33351.933310773.09351.2318
10869.41368.049110922.91381.848910976.08402.558611029.11414.348411090.92420.1316
#Mann= 3 , 0 , 0
9069.898  0.0792       09069.898  0.0792       011090.92  0.0792       0
#XS Ineff= 2 , 0
       0                10166.33       0
Bank Sta=9069.898,11090.92
Exp/Cntr=0.3,0.1

Type RM Length L Ch R = 1 ,34393.65,149.015600,149.015600,149.015600
XS GIS Cut Line= 6
788155.353249358784990.366491086788932.476020309785275.970467309
789240.079590896785391.358677476789645.017415835785548.938651458
789864.989692982785628.928254743790021.689652239785680.928914924
#Sta/Elev= 30
9117.141432.38089350.793431.79779361.454429.88379393.435398.19889436.078378.7557
9702.592359.20719740.295351.82869777.216336.4245  9862.5337.28039883.821344.4725
9926.464324.38679990.698319.6363   10119323.032510161.63340.915910225.59327.9707
10257.56326.963910393.98330.039610461.34341.246710525.72 334.63310622.29336.9287
10686.68349.507510740.06340.020810825.18344.479710867.75355.356110889.03368.4515
10910.31373.351611005.45413.377811037.06412.160211068.67426.091611107.32427.5624
#Mann= 3 , 0 , 0
9117.141   0.085       09117.141   0.085       011107.32   0.085       0
#XS Ineff= 2 , 0
       0                10171.78       0
Bank Sta=9117.141,11107.32
Exp/Cntr=0.3,0.1

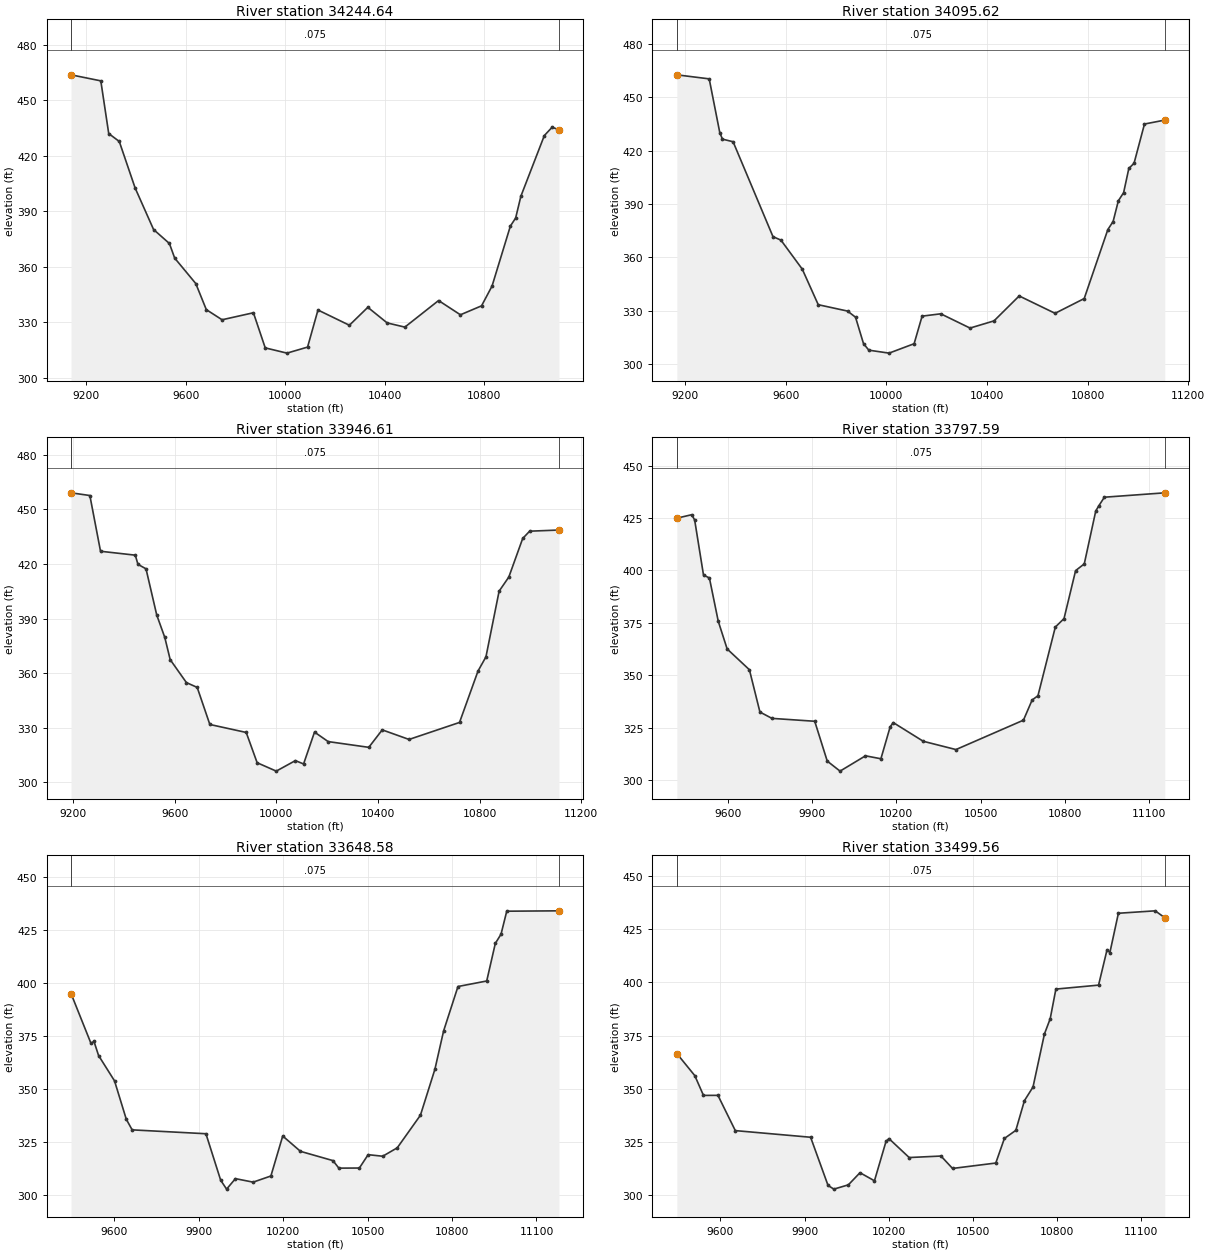
Type RM Length L Ch R = 1 ,34244.64,149.015600,149.015600,149.015600
XS GIS Cut Line= 6
788131.758569935785169.114062522788755.049054136785385.055082797
789041.140299622785464.780297048789145.467276173785497.285341057
789685.118625576785689.980524577789991.555063722785787.361716923
#Sta/Elev= 30
9139.858 463.6389259.384460.38269291.188431.92539333.594427.66349397.203402.5776
9471.414 380.1279535.023372.58179556.226364.70219641.037350.95229683.331336.8732
9746.672331.40159872.606335.1882 9920.06316.226210007.46313.3925 10090.2316.6486
10132.02336.667110258.24328.448410332.32338.125310410.01329.699610481.13327.4405
 10616.6341.785710704.33334.090410789.27338.922410831.43349.5855 10905.2382.0105
10926.27386.315110947.32398.102811041.59 430.85611072.81435.333111100.44433.9867
#Mann= 3 , 0 , 0
9139.858   0.075       09139.858   0.075       011100.44   0.075       0
#XS Ineff= 2 , 0
       0                10160.28       0
Bank Sta=9139.858,11100.44
Exp/Cntr=0.3,0.1

Type RM Length L Ch R = 1 ,34095.62,149.015700,149.015700,149.015700
XS GIS Cut Line= 6
788113.037219457785310.942475271788388.026500904785403.347355259
789403.815830111785756.490579197789637.940341347785833.838002312
789794.337880813785880.993503076 789952.85672881785924.040942363
#Sta/Elev= 30
9166.774462.69549295.432460.42019337.632430.06139348.181426.49559390.381425.0372
9548.943371.63179580.701369.66049665.388353.34139728.904333.32859845.349329.7434
9877.107326.30129908.865311.41529930.036307.739410010.49306.075810110.03311.3717
10141.79326.887610215.91328.204210332.38320.176610427.67324.223110527.76338.2594
10670.46328.475810786.24 336.78710880.24 375.63310901.13380.151310922.02391.8271
10942.91396.383610963.63410.011110984.36 412.924 11025.8 435.00411106.48437.2194
#Mann= 3 , 0 , 0
9166.774   0.075       09166.774   0.075       011106.48   0.075       0
#XS Ineff= 2 , 0
       0                10159.66       0
Bank Sta=9166.774,11106.48
Exp/Cntr=0.3,0.1

Type RM Length L Ch R = 1 ,33946.61,149.015600,149.015600,149.015600
XS GIS Cut Line= 6
788094.480104076785451.526682742788611.804582037785627.187061389
789029.304866312785792.431021781789308.357353702785893.381661283
789665.183803261786000.685143325789914.165382553786060.695484465
#Sta/Elev= 30
9191.801459.09719265.819457.62039307.803426.97479444.631424.8267 9455.19419.7767
9486.866417.3216  9529.1391.92789560.788379.6204 9582.06367.40459645.878354.7846
9688.422352.12339738.205331.7472  9881.4327.35759924.403310.7192 9999.66306.0992
10074.98  311.8810107.26310.0412 10150.3327.560310203.99322.337610363.98319.1781
10416.92328.783610522.46323.517910721.22332.867210794.04361.143210825.25368.9288
10877.08405.041310915.29 412.79910969.89433.994410997.24438.011311112.79438.6388
#Mann= 3 , 0 , 0
9191.801   0.075       09191.801   0.075       011112.79   0.075       0
#XS Ineff= 2 , 0
       0                10162.02       0
Bank Sta=9191.801,11112.79
Exp/Cntr=0.3,0.1

Type RM Length L Ch R = 1 ,33797.59,149.015600,149.015600,149.015600
XS GIS Cut Line= 6
788244.633251103785642.888265048788660.553259882785791.613456925
788855.643060111785892.652390236 789087.50625859785988.170645793
789386.196117191786081.458944173789885.815846433786194.711500688
#Sta/Elev= 30
9418.285424.91099471.217426.57159481.726424.07199513.253397.79549534.271396.4183
9565.799 375.7719597.462362.57219676.754352.6527 9714.25 332.4889757.084329.4728
9909.431328.09399954.007309.10819999.647304.321310090.24311.620910145.15310.2198
10178.09325.413210189.03327.475610296.05318.551210412.49 314.602 10652.9328.6149
10683.86338.241810704.51340.249310766.44373.010310797.41 377.047 10838.7399.9209
10869.55403.118810910.49428.359310920.72430.681410941.19434.914111156.27437.0032
#Mann= 3 , 0 , 0
9418.285   0.075       09418.285   0.075       011156.27   0.075       0
#XS Ineff= 2 , 0
       0                10195.76       0
Bank Sta=9418.285,11156.27
Exp/Cntr=0.3,0.1

Type RM Length L Ch R = 1 ,33648.58,149.015600,149.015600,149.015600
XS GIS Cut Line= 6
 788196.81280981785827.793971378788426.599306144785895.845151139
789072.706457874786102.542511725789285.815759389786163.045176389
789633.725795089 786241.91810382789868.107096619786281.484374787
#Sta/Elev= 30
9445.853394.9044 9516.77371.35099527.212372.3776  9543.6365.66959600.305353.6972
9642.072335.58029662.956 330.548 9925.15328.71879977.611306.75249998.595302.5523
10030.03 307.50310092.96305.850710156.04308.756310198.09327.645310261.16320.3989
10376.69316.019610397.54 312.468 10470.5 312.51910501.67318.825710553.49318.0915
10605.16322.068110687.49337.460410738.94359.170610769.81377.259810820.95398.2643
10923.08 400.86710953.65418.622710973.95422.977510994.25433.834411179.92434.0128
#Mann= 3 , 0 , 0
9445.853   0.075       09445.853   0.075       011179.92   0.075       0
#XS Ineff= 2 , 0
       0                10212.18       0
Bank Sta=9445.853,11179.92
Exp/Cntr=0.3,0.1

Type RM Length L Ch R = 1 ,33499.56,149.015700,149.015700,149.015700
XS GIS Cut Line= 6
788152.788083943785998.022911397789042.950080668786226.377319009
789258.504263125786277.523798688789448.041128039786316.181352433
789609.066194923786343.643916358789848.936129224786375.422115036
#Sta/Elev= 30
9444.878366.58529508.912356.2216 9539.79 346.9449591.343346.9624 9653.29 330.417
9921.726327.2959 9983.86304.687510004.58302.947910056.37304.961510097.73310.6524
10149.32 306.85810190.59325.370110200.91326.669410273.14317.775410386.55318.4795
10427.66 312.65210581.82315.195310612.46326.725510653.29330.541410683.91344.4721
10714.52350.877610755.35375.828810775.76382.903710796.07396.8477 10948.2398.7085
10978.48415.334810988.58413.991511018.86432.441611150.05433.582311184.19430.3512
#Mann= 3 , 0 , 0
9444.878   0.075       09444.878   0.075       011184.19   0.075       0
#XS Ineff= 2 , 0
       0                10206.99       0
Bank Sta=9444.878,11184.19
Exp/Cntr=0.3,0.1

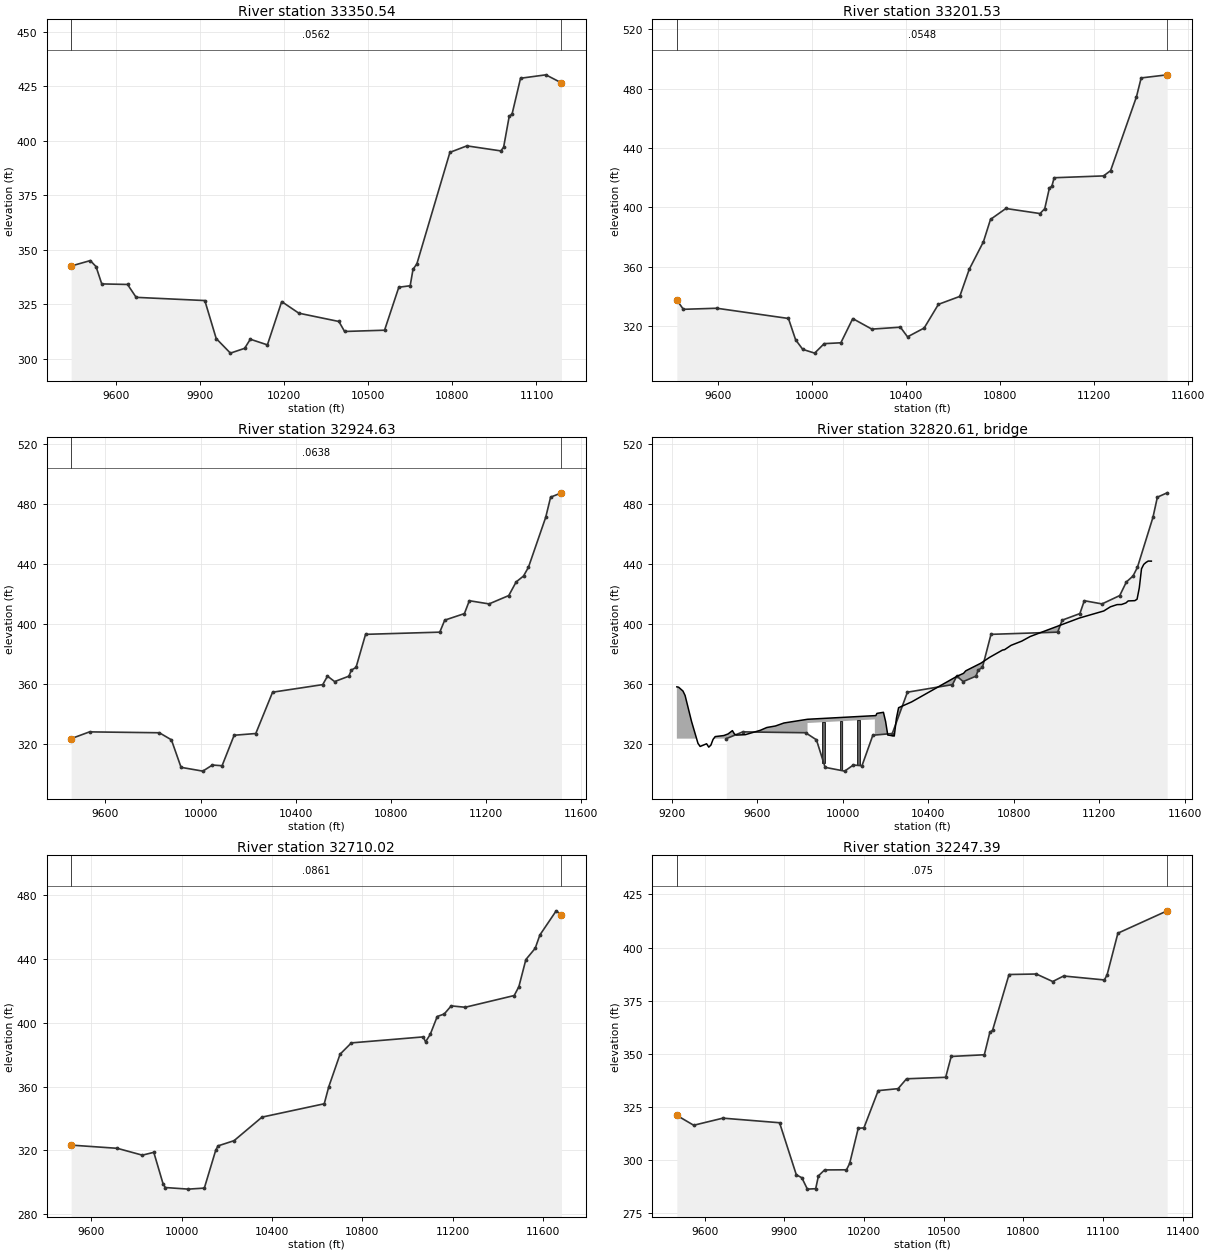
Type RM Length L Ch R = 1 ,33350.54,149.015600,149.015600,149.015600
XS GIS Cut Line= 6
788108.278424612786170.126927478 788507.72304571786254.183121391
788771.806913576786299.870995958789231.794880787786390.319371472
 789499.75967757786432.159798526789830.556612449786465.481747242
#Sta/Elev= 30
9440.405342.52679508.588345.02339529.026342.26269549.464334.30559641.435334.0548
9672.092328.13489917.042326.66019957.654309.2096 10008.3302.509410059.01304.7066
10079.29 308.89810140.27306.299310191.26326.181610252.45320.854610395.22317.0459
10415.61312.456110558.15313.040510608.96332.773910649.53333.466810659.67341.0318
10673.33343.490910791.21394.736610851.84397.716410972.66395.410810982.72397.0433
11002.86411.355511012.92412.316511043.11 428.77311133.48430.351311189.17426.6504
#Mann= 3 , 0 , 0
9440.405  0.0562       09440.405  0.0562       011189.17  0.0562       0
#XS Ineff= 2 , 0
       0                10204.03       0
Bank Sta=9440.405,11189.17
Exp/Cntr=0.3,0.1

Type RM Length L Ch R = 1 ,33201.53,276.902800,276.902800,276.902800
XS GIS Cut Line= 6
788067.691119802786327.064506075788562.718686746786416.421235828
789212.771016973786519.468105371  789567.7824758786554.585960837
789765.162629021786564.988193042790135.557886762786570.582353302
#Sta/Elev= 30
9424.206337.58889451.956331.40969594.218332.12279899.067325.24339929.543310.8991
9959.918304.444210010.55301.915210051.09308.297710122.02308.875210172.69325.1612
10253.77318.077310375.38319.375910405.76312.874910476.51318.823910537.14334.7549
10627.92 340.08410668.18358.310310728.57376.847410758.76391.930910824.23399.2655
10969.47395.864910989.49399.138711009.52 413.17811019.54414.092111029.55419.9667
11239.73 421.19411269.74424.752811379.77474.454211399.77 487.14311510.33489.2351
#Mann= 3 , 0 , 0
9424.206  0.0548       09424.206  0.0548       011510.33  0.0548       0
#XS Ineff= 2 , 0
       0                10194.27       0
Bank Sta=9424.206,11510.33
Exp/Cntr=0.3,0.1

Type RM Length L Ch R = 1 ,32924.63,214.609300,214.609300,214.609300
XS GIS Cut Line= 6
788048.633629841786613.597540542788884.287937544786747.323530896
789114.733243118786767.777705645 789361.20075729786774.124535608
789524.542275821786772.271666669790079.125985146786622.532916442
#Sta/Elev= 30
9455.976323.67339533.048328.18399826.746327.59229877.512322.88829918.126304.5448
10009.49302.019910050.06306.085510090.63305.612510141.33325.931110232.36327.0901
10303.07354.624910513.95359.6783   10534365.330510564.03361.702410624.08365.3139
10634.08369.297810654.09371.1727 10694.1393.184311006.28394.6453   11027402.6361
11109.86407.016711130.58415.594811213.44413.467711296.31419.026811327.38428.1018
11358.46432.054411379.17 437.89311451.68471.1431 11472.4484.6088 11518.1 487.502
#Mann= 3 , 0 , 0
9455.976  0.0638       09455.976  0.0638       0 11518.1  0.0638       0
#XS Ineff= 2 , 0
       0                10183.61       0
Bank Sta=9455.976,11518.1
Exp/Cntr=0.3,0.1

Type RM Length L Ch R = 3 ,32820.61,,,
BEGIN DESCRIPTION:
END DESCRIPTION:
Bridge Culvert--1,0,-1,-1, 0
Deck Dist Width WeirC Skew NumUp NumDn MinLoCord MaxHiCord MaxSubmerge Is_Ogee
79.804650,55.000000,2.6,0, 60, 60, , , 0.95, 0, 0,0,,
 9224.50 9232.87 9252.98 9263.04 9293.22 9323.40 9333.46 9363.63 9373.69 9383.75
 9393.81 9403.87 9444.10 9464.22 9484.34 9494.40 9504.46 9544.69 9615.10 9645.28
 9685.52 9725.75 9835.83 9835.8310150.8310150.8310155.4210160.5010190.8910201.02
10211.1510241.5410251.6710261.8010322.5910535.3510565.7410575.8710646.7910687.32
10747.8210757.8310787.8410837.8710877.8911107.3611221.6011252.7611283.9211304.69
11325.4611335.8511367.0011377.3911387.7711398.1611408.5511418.9311429.3211444.22
  358.20  357.94  355.42  352.45  335.14  320.50  318.47  320.25  318.01  319.35
  323.16  325.04  325.73  326.81  329.01  326.64  326.05  326.32  329.23  331.09
  332.10  334.11  336.58  336.58  339.00  339.00  339.03  340.51  341.22  335.10
  326.08  325.42  337.29  344.29  348.14  365.27  367.20  368.86  373.97  377.83
  382.70  382.98  385.85  388.66  391.77  404.05  408.76  411.54  413.00  413.07
  414.14  415.45  415.64  416.62  424.12  436.86  439.78  441.08  442.02  441.98
 -641.80 -642.06 -644.58 -647.55 -664.86 -679.50 -681.53 -679.75 -681.99 -680.65
 -676.84 -674.96 -674.27 -673.19 -670.99 -673.36 -673.95 -673.68 -670.77 -668.91
 -667.90 -665.89 -663.42  334.08  336.50 -661.00 -660.97 -659.49 -658.78 -664.90
 -673.92 -674.58 -662.71 -655.71 -651.86 -634.73 -632.80 -631.14 -626.03 -622.17
 -617.30 -617.02 -614.15 -611.34 -608.23 -595.95 -591.24 -588.46 -587.00 -586.93
 -585.86 -584.55 -584.36 -583.38 -575.88 -563.14 -560.22 -558.92 -557.98 -558.02
 9224.50 9232.87 9252.98 9263.04 9293.22 9323.40 9333.46 9363.63 9373.69 9383.75
 9393.81 9403.87 9423.98 9444.10 9464.22 9484.34 9494.40 9504.46 9534.63 9725.75
 9844.38 9844.3810155.4210159.3810159.3810190.8910201.0210211.1510241.5410251.67
10261.8010322.5910535.3510565.7410575.8710646.7910687.3210747.8210757.8310787.84
10837.8710877.8911107.3611128.1311200.8311221.6011252.7611283.9211304.6911325.46
11335.8511367.0011377.3911386.0211387.7711398.1611408.5511418.9311429.3211444.22
  358.20  357.94  355.42  352.45  335.14  320.50  318.47  320.25  318.01  319.35
  323.16  325.04  324.97  325.73  326.81  329.01  326.64  326.05  326.11  334.11
  336.50  336.50  339.03  340.18  340.18  341.22  335.10  326.08  325.42  337.29
  344.29  348.14  365.27  367.20  368.86  373.97  377.83  382.70  382.98  385.85
  388.66  391.77  404.05  404.48  408.24  408.76  411.54  413.00  413.07  414.14
  415.45  415.64  416.62  422.46  424.12  436.86  439.78  441.08  442.02  441.98
 -641.80 -642.06 -644.58 -647.55 -664.86 -679.50 -681.53 -679.75 -681.99 -680.65
 -676.84 -674.96 -675.03 -674.27 -673.19 -670.99 -673.36 -673.95 -673.89 -665.89
 -663.50  334.00  336.53  337.68 -659.82 -658.78 -664.90 -673.92 -674.58 -662.71
 -655.71 -651.86 -634.73 -632.80 -631.14 -626.03 -622.17 -617.30 -617.02 -614.15
 -611.34 -608.23 -595.95 -595.52 -591.76 -591.24 -588.46 -587.00 -586.93 -585.86
 -584.55 -584.36 -583.38 -577.54 -575.88 -563.14 -560.22 -558.92 -557.98 -558.02
Pier Skew, UpSta & Num, DnSta & Num=  ,9911.58, 2 ,9920.13, 2 , 0 , 0 , 0 ,,
   12.00   12.00
 -662.95  337.05
   12.00   12.00
 -662.88  337.12
Pier Skew, UpSta & Num, DnSta & Num=  ,9993.33, 2 ,10001.88, 2 , 0 , 0 , 0 ,,
   12.00   12.00
 -662.29  337.71
   12.00   12.00
 -662.22  337.78
Pier Skew, UpSta & Num, DnSta & Num=  ,10075.08, 2 ,10083.63, 2 , 0 , 0 , 0 ,,
   12.00   12.00
 -661.62  338.38
   12.00   12.00
 -661.55  338.45
BR Coef=-1 , 0 , 0 ,, 0 ,,,0.8,0,1,0,
WSPro=,,,, 1 ,,,, 0 ,,,, 0 ,,,,-1 ,-1 ,-1 , 0 , 0 , 0 , 0 , 0
BC Design=,, 0 ,, 0 ,,,,,,

Type RM Length L Ch R = 1 ,32710.02,462.629700,462.629700,462.629700
XS GIS Cut Line= 6
788061.563934933786849.745744176788343.059864253786875.012174577
788751.078529716786941.703704581789067.841262966787021.838472009
789345.619040728 787026.17874977790187.632929623786809.164860889
#Sta/Elev= 30
9510.958 323.3719715.043321.36899825.945317.07689876.654 318.8579917.374299.3103
9927.553296.806110029.29295.805410100.38 296.45210150.78320.153410160.85322.8804
10231.92326.1485 10355.7340.898910631.16349.267110651.16 359.90910701.17380.3053
10751.17387.395711069.33391.143211079.66 388.03911100.31392.704911131.29403.9133
11162.27405.499111193.25410.572311255.21409.710111472.08 417.05211492.73422.6019
11523.71439.595811565.02446.646711585.67454.965311657.95470.105611681.33467.4079
#Mann= 3 , 0 , 0
9510.958  0.0861       09510.958  0.0861       011681.33  0.0861       0
#XS Ineff= 2 , 0
       0                10195.96       0
Bank Sta=9510.958,11681.33
Exp/Cntr=0.3,0.1

Type RM Length L Ch R = 1 ,32247.39,248.843600,248.843600,248.843600
XS GIS Cut Line= 6
788091.547716097787397.344274128788413.950419247787405.183924809
788640.370210767787334.030646205 789139.64774695787155.798733503
789485.610890269787068.712090686789877.187169552786989.638083607
#Sta/Elev= 30
9495.062320.94159558.533316.29579668.566319.6415 9881.92317.48119944.991 292.979
9965.838291.57659986.685286.217710017.98286.424410028.43292.489410051.58295.2619
10133.96 295.31810145.92298.300310178.18314.848510199.68315.076710253.44332.6009
10328.33333.533110360.16338.1773 10507.5338.880210528.37348.693710653.12349.4895
10673.84360.017710684.21 361.03510746.11387.285610848.97387.518510910.69383.9851
10951.78386.576911105.14384.725811115.36387.053511156.21406.744311341.68417.2712
#Mann= 3 , 0 , 0
9495.062   0.075       09495.062   0.075       011341.68   0.075       0
#XS Ineff= 2 , 0
       09851.608        10208.45       0
Bank Sta=9495.062,11341.68
Exp/Cntr=0.3,0.1

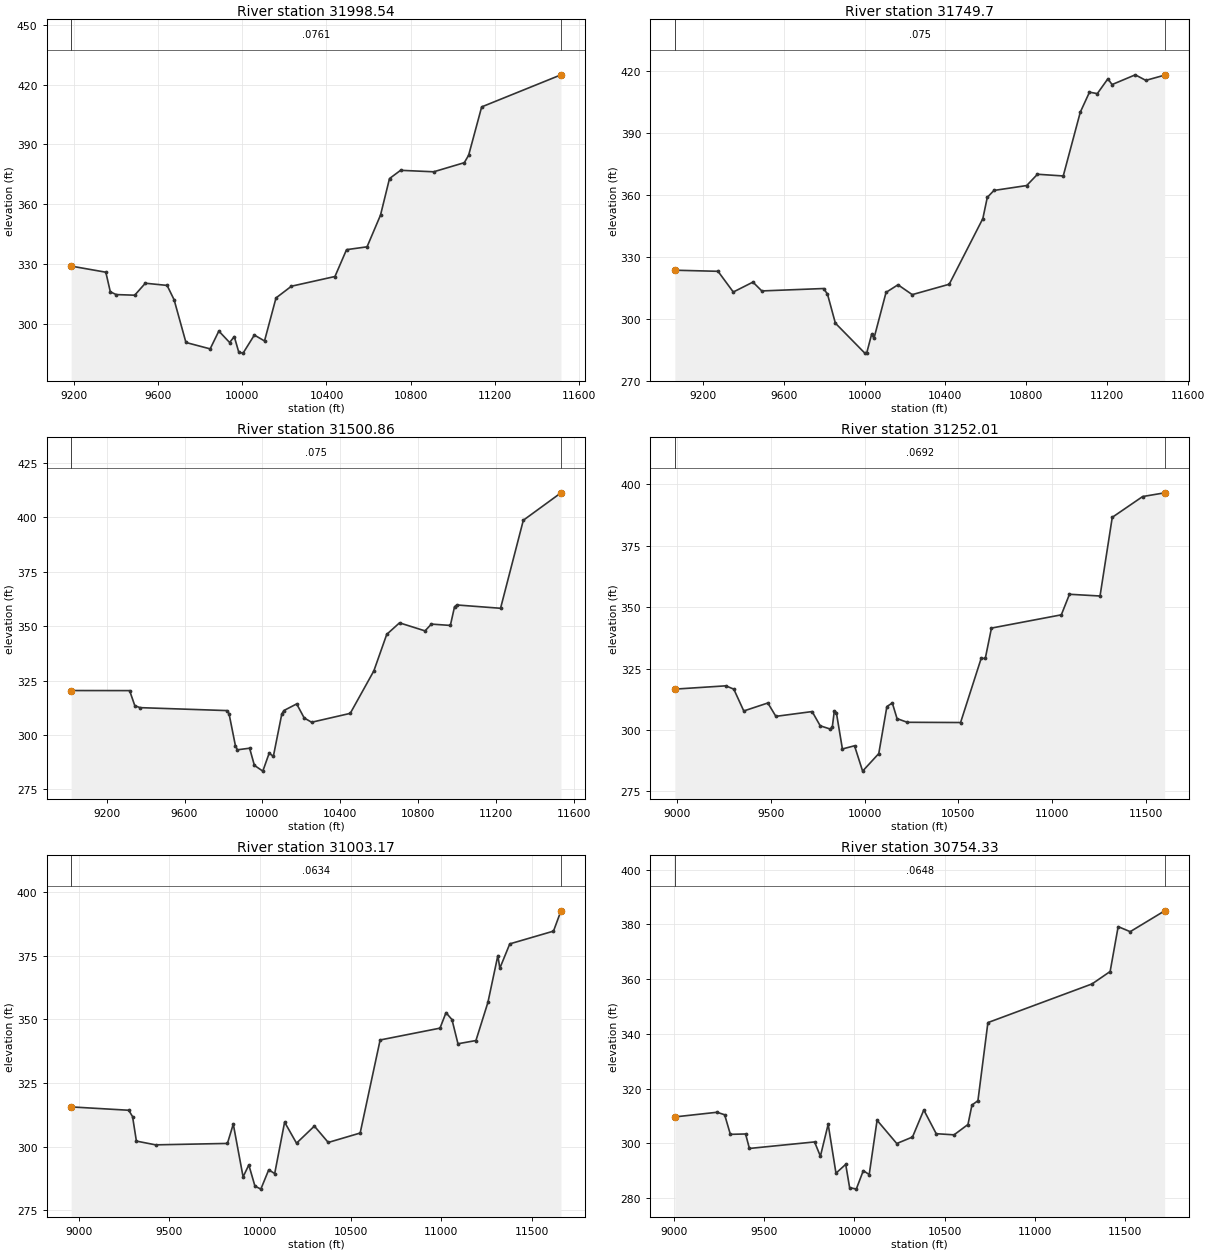
Type RM Length L Ch R = 1 ,31998.54,248.843500,248.843500,248.843500
XS GIS Cut Line= 6
787958.290364902787882.712135061788351.255437109787739.264133902
789048.631580395787363.701898577789217.927463852787288.601645411
789646.769374827787149.969481574790112.138547072787039.869512656
#Sta/Elev= 30
 9186.59329.06579351.343326.00349372.643316.20589400.459314.79979488.563314.4874
9539.116320.48969642.593319.38979675.851312.21039732.127290.80439847.184287.6006
9888.448 296.5259939.733290.79439961.842293.75639983.229285.922710003.69285.4724
10057.24294.5232 10105.6291.574510160.15313.114410233.36 318.986 10440.3323.8517
10495.36337.294810592.88  338.72 10656.9 354.62210699.57372.9133 10752.3377.0417
10909.53376.302411055.05380.865211075.68384.608711137.58408.805611514.52424.8707
#Mann= 3 , 0 , 0
 9186.59  0.0761       0 9186.59  0.0761       011514.52  0.0761       0
#XS Ineff= 2 , 0
       09840.281        10188.63       0
Bank Sta=9186.59,11514.52
Exp/Cntr=0.3,0.1

Type RM Length L Ch R = 1 , 31749.7,248.843600,248.843600,248.843600
XS GIS Cut Line= 6
788013.980208162788150.719505779788506.636553153787953.544510933
 789046.60738638 787624.53442289789418.595576639787435.565853175
789696.890448626787328.158152479790214.842702178787171.152215277
#Sta/Elev= 30
9062.599323.54549276.061323.01879351.453312.98099448.648 317.7859492.412313.5069
9797.598314.67749816.955311.98939856.054297.891810001.49283.374810011.27283.5783
10035.09292.4566   10047290.603410106.55312.812810165.54316.489510235.97 311.717
10418.63316.739810584.92348.5701 10606.9358.846810639.88362.192510801.65364.5702
10854.93370.041410982.31369.210111066.55400.124211111.96409.808211150.67409.1098
 11202.8416.274911223.66 413.49511338.34418.2112 11390.4415.524411483.52418.0586
#Mann= 3 , 0 , 0
9062.599   0.075       09062.599   0.075       011483.52   0.075       0
#XS Ineff= 2 , 0
       09787.977        10124.05       0
Bank Sta=9062.599,11483.52
Exp/Cntr=0.3,0.1

Type RM Length L Ch R = 1 ,31500.86,248.843600,248.843600,248.843600
XS GIS Cut Line= 6
788053.163552413788339.289350007788536.606765323788154.382206117
789092.863279042787915.350770281789823.310718439787586.028723532
790113.407200536787472.463872874790377.325993743787378.848248855
#Sta/Elev= 30
9017.764320.44339318.052320.41289344.708313.4878 9371.69312.5817 9817.69311.2311
9828.613309.85379861.384295.13979871.813293.20459934.452293.94159958.928286.0567
10002.23283.402810034.77 291.62610056.46290.218610099.84309.710110110.68311.2624
10176.15314.295310214.77307.844110252.94305.869810451.31 309.95210572.61329.4833
10638.78 346.26310704.49351.559810835.41347.866210868.01350.980110965.58350.3716
10987.11358.978910998.95359.7789 11223.4 358.25411340.38398.7141 11533.8411.3204
#Mann= 3 , 0 , 0
9017.764   0.075       09017.764   0.075       0 11533.8   0.075       0
#XS Ineff= 2 , 0
       09797.068        10122.13       0
Bank Sta=9017.764,11533.8
Exp/Cntr=0.3,0.1

Type RM Length L Ch R = 1 ,31252.01,248.843500,248.843500,248.843500
XS GIS Cut Line= 6
 788107.05751879 788555.36335338788483.665209059788426.228985442
789101.097933236788182.640905653789422.907186842 788044.72791446
790002.729030049787782.949131541790524.001146865787566.337357638
#Sta/Elev= 30
8988.112316.67789260.174 318.0189302.683316.66319355.818307.7825 9484.16 311.034
9527.026305.59089720.453307.54239763.521301.74859817.357300.41279828.124 301.294
9838.891307.81189849.658307.13659881.959292.31179946.561293.61369989.759283.2887
10075.92290.436610119.24309.584810148.12311.041910173.38304.674610227.72 303.174
 10512.3303.078710622.13329.1984 10644.1329.186310677.05341.533311049.69346.9267
11093.16355.299411256.17  354.5911321.37386.627311483.45 395.08811600.87396.6009
#Mann= 3 , 0 , 0
8988.112  0.0692       08988.112  0.0692       011600.87  0.0692       0
#XS Ineff= 2 , 0
       09835.288         10138.5       0
Bank Sta=8988.112,11600.87
Exp/Cntr=0.3,0.1

Type RM Length L Ch R = 1 ,31003.17,248.843600,248.843600,248.843600
XS GIS Cut Line= 6
788172.906893317788789.022424274788403.791127618788715.558478728
788627.224805728788638.198015938789043.733616041788476.565281291
789516.684436052788268.261036751790662.687027515787743.614092044
#Sta/Elev= 30
 8957.83315.57879275.476314.26399296.641311.76839317.806302.1546 9423.63300.6784
9820.038301.23519852.389308.8225 9906.51288.09159938.141292.79139971.783284.5069
10004.44283.288410048.12290.893310080.88289.386610135.62309.595410201.29301.3308
10299.81308.042110376.44301.617910552.52305.317310662.66341.860610993.09346.5087
11026.13352.596411059.17349.854511092.21340.375611191.34341.642811257.41356.6214
11312.23375.0041 11323.2370.034311378.02379.599211619.25384.608411660.57392.5804
#Mann= 3 , 0 , 0
 8957.83  0.0634       0 8957.83  0.0634       011660.57  0.0634       0
#XS Ineff= 2 , 0
       09856.039        10141.75       0
Bank Sta=8957.83,11660.57
Exp/Cntr=0.3,0.1

Type RM Length L Ch R = 1 ,30754.33,248.843600,248.843600,248.843600
XS GIS Cut Line= 6
788311.573210161788991.693476339788811.156790173788828.558847877
789059.931143368788736.388013756 789270.20678498788650.347056328
789785.384860856788421.755616739790806.793331714 787927.81954177
#Sta/Elev= 30
9003.711309.67249237.908311.37559279.926310.45579311.603303.31399396.077303.4464
9417.195298.15889778.622300.54199810.869295.31249854.064306.99779897.259 289.128
9951.253292.3499 9972.85283.885410009.87283.307210048.85290.050510081.58288.6282
10125.23308.450210234.35299.961210321.64302.329810384.33312.203510453.18303.5447
10552.05303.130110629.22306.902510651.33314.0121 10684.5315.591510739.78344.1103
11317.53358.241111417.65362.768211462.15379.1603 11528.9 377.31211720.01384.9236
#Mann= 3 , 0 , 0
9003.711  0.0648       09003.711  0.0648       011720.01  0.0648       0
#XS Ineff= 2 , 0
       09853.398        10138.94       0
Bank Sta=9003.711,11720.01
Exp/Cntr=0.3,0.1

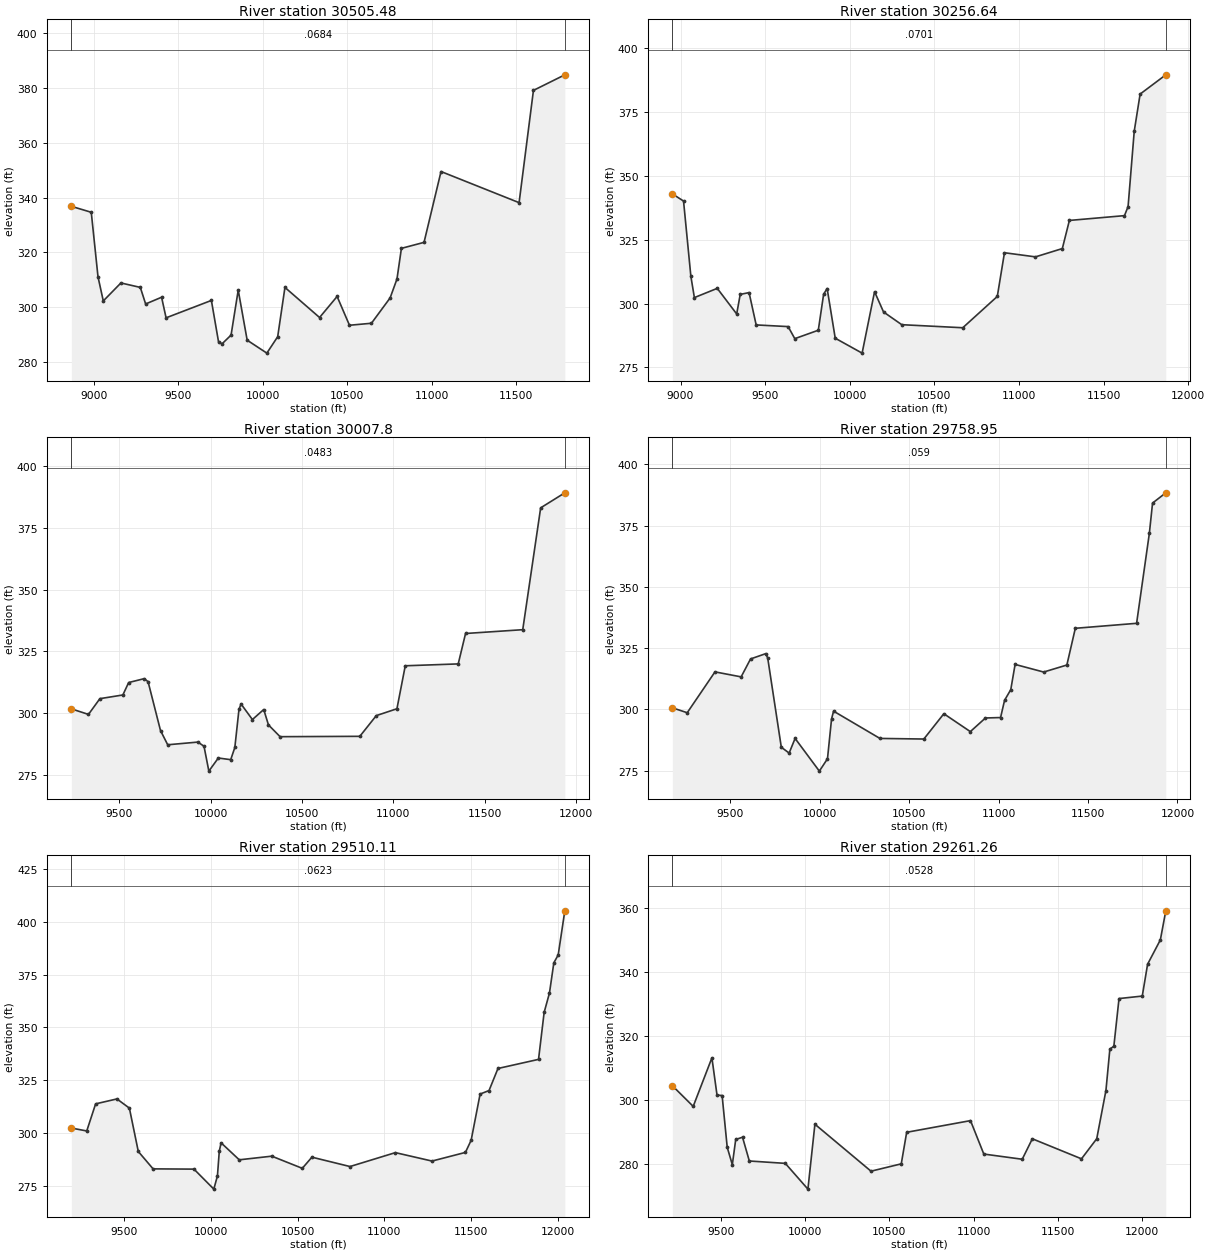
Type RM Length L Ch R = 1 ,30505.48,248.843500,248.843500,248.843500
XS GIS Cut Line= 6
788263.786449187  789238.9381207788856.525003457789057.067734197
789381.067894956788876.195030019789553.299347423788809.243806027
790056.954097537788582.212745578790953.833280947788117.585785688
#Sta/Elev= 30
8866.629336.8202 8984.63334.63919024.513311.07959055.837302.25129160.248 308.821
9275.126307.20079306.617301.14579401.087303.60469427.672296.08279696.014302.4379
9738.367287.29979759.558  286.619812.534289.77719854.915306.19579907.892287.9185
10024.48283.187710088.66289.186510131.58 307.19210336.62296.201410440.56303.8922
10513.73293.370310643.86294.100410754.52303.363310795.09 310.27510821.34321.4637
 10955.3323.652211055.94349.526611518.25338.156911603.25379.171511789.02384.8552
#Mann= 3 , 0 , 0
8866.629  0.0684       08866.629  0.0684       011789.02  0.0684       0
#XS Ineff= 2 , 0
       09858.494        10144.23       0
Bank Sta=8866.629,11789.02
Exp/Cntr=0.3,0.1

Type RM Length L Ch R = 1 ,30256.64,248.843600,248.843600,248.843600
XS GIS Cut Line= 6
 788419.65345544789423.144582625789275.731025285789163.377906498
789494.852207043789106.295108392789736.830098989789017.024067442
790462.843007608788660.594860081 791095.75321379788302.367443218
#Sta/Elev= 30
8951.635342.89819017.946340.09349061.162310.66039081.955 302.3169217.113305.9289
9331.942295.91289352.823303.56519405.044304.27529446.998291.62149635.792290.9675
9675.192286.25029814.097289.54349845.563303.64899866.349305.87039914.086286.4224
10072.95280.587410146.48304.629610199.54296.686910307.23291.712710667.62290.5178
10871.64302.763710913.95319.867311097.17318.248911255.84321.500811297.56332.5058
11623.07 334.38311644.34337.931911680.67367.418311715.47381.944911867.16389.4759
#Mann= 3 , 0 , 0
8951.635  0.0701       08951.635  0.0701       011867.16  0.0701       0
#XS Ineff= 2 , 0
       09872.585        10162.15       0
Bank Sta=8951.635,11867.16
Exp/Cntr=0.3,0.1

Type RM Length L Ch R = 1 , 30007.8,248.843500,248.843500,248.843500
XS GIS Cut Line= 6
788784.668217217789624.088426907789224.389508569789484.768093568
789497.949669039789360.564916167790407.996464675788896.386434646
790821.230466275788663.959304917791196.757832723788433.876812836
#Sta/Elev= 30
9238.955301.78469332.602299.53399395.085305.91089520.692307.39789552.359312.4364
9637.147314.00329658.464312.79649726.471293.0105 9765.84287.24449931.048288.3336
9964.382286.63539990.853276.575910042.59281.885810110.36281.213110132.95286.1636
10155.55301.547610166.84303.749810228.97297.456210290.91301.513210316.69 295.293
10380.34290.517810816.34 290.66210906.37 299.04411019.26 301.82511064.81319.2159
11354.36 319.97311394.46 332.28511707.16333.824111805.13383.1435 11937.2389.2211
#Mann= 3 , 0 , 0
9238.955  0.0483       09238.955  0.0483       0 11937.2  0.0483       0
#XS Ineff= 2 , 0
       09858.567        10188.82       0
Bank Sta=9238.955,11937.2
Exp/Cntr=0.3,0.1

Type RM Length L Ch R = 1 ,29758.95,248.843600,248.843600,248.843600
XS GIS Cut Line= 6
788874.159816529789836.441374424 789299.76236999789716.445401202
789543.959567655789613.729813834790567.379510462789083.122458202
790979.168409063788835.628049485791327.016309346788603.475097838
#Sta/Elev= 30
9175.925300.65249259.247298.64719414.375 315.3139560.663313.27639613.293320.5893
9698.759322.76939709.452320.88389785.272284.55519829.107282.18719862.366288.1637
9998.016 274.81410043.48279.862410066.22296.118110077.59299.287710336.68288.1566
10582.23287.911510694.09298.231910842.19290.940110926.71296.499711011.23296.6791
11033.63303.723511068.24308.061911092.48318.359311252.22315.247211381.89318.1124
11429.17333.099511771.78335.129911843.14371.855711860.98384.201511935.05388.3789
#Mann= 3 , 0 , 0
9175.925   0.059       09175.925   0.059       011935.05   0.059       0
#XS Ineff= 2 , 0
       09691.279        10115.44       0
Bank Sta=9175.925,11935.05
Exp/Cntr=0.3,0.1

Type RM Length L Ch R = 1 ,29510.11,248.843600,248.843600,248.843600
XS GIS Cut Line= 6
788937.836811651789987.539328948789296.421948228789910.519787879
789819.798717103789765.824962277790377.365959526789548.003050482
790852.599045513789285.415613207791495.082091891788822.299002632
#Sta/Elev= 30
9196.247302.31659285.111300.9383  9336.2 313.7759458.948316.11139530.791311.7609
  9582.2291.21089667.435282.98139903.128282.860210017.56273.383710038.44279.6689
10048.89291.242610059.33295.330810164.15287.271310351.71288.997310527.49283.2359
10582.95288.522910802.49284.086711064.11290.674511275.22286.677311467.78290.7765
11500.77296.513211552.49318.425911603.94320.082811655.38330.538511889.24334.8486
 11921.6357.098811952.24366.279311977.44380.579912002.64384.336312040.75405.2218
#Mann= 3 , 0 , 0
9196.247  0.0623       09196.247  0.0623       012040.75  0.0623       0
#XS Ineff= 2 , 0
       0                10091.08       0
Bank Sta=9196.247,12040.75
Exp/Cntr=0.3,0.1

Type RM Length L Ch R = 1 ,29261.26,248.843500,248.843500,248.843500
XS GIS Cut Line= 6
789012.216728669790164.034047291789704.282511761790056.790599992
790253.709384645789899.292625575790526.850234472789788.877669144
791038.497455614789477.391781235791626.861284466788993.877280215
#Sta/Elev= 30
9211.529304.40959335.458297.92369446.484313.12349476.764301.46549507.044301.3147
9537.324285.10759567.604 279.676 9587.79 287.5569628.163288.26399668.537280.8223
9882.121280.076910016.23272.010510057.77292.336310390.68277.627210570.27279.9285
10602.37289.811910981.15293.462111060.14 282.99411288.19281.367511348.15287.7764
11639.87281.500211730.35287.793811784.93302.893411808.29315.873911831.94316.7547
11862.64331.690912000.57332.4681 12032.2342.449912107.86350.055612140.23359.1649
#Mann= 3 , 0 , 0
9211.529  0.0528       09211.529  0.0528       012140.23  0.0528       0
#XS Ineff= 2 , 0
       0                10070.58       0
Bank Sta=9211.529,12140.23
Exp/Cntr=0.3,0.1