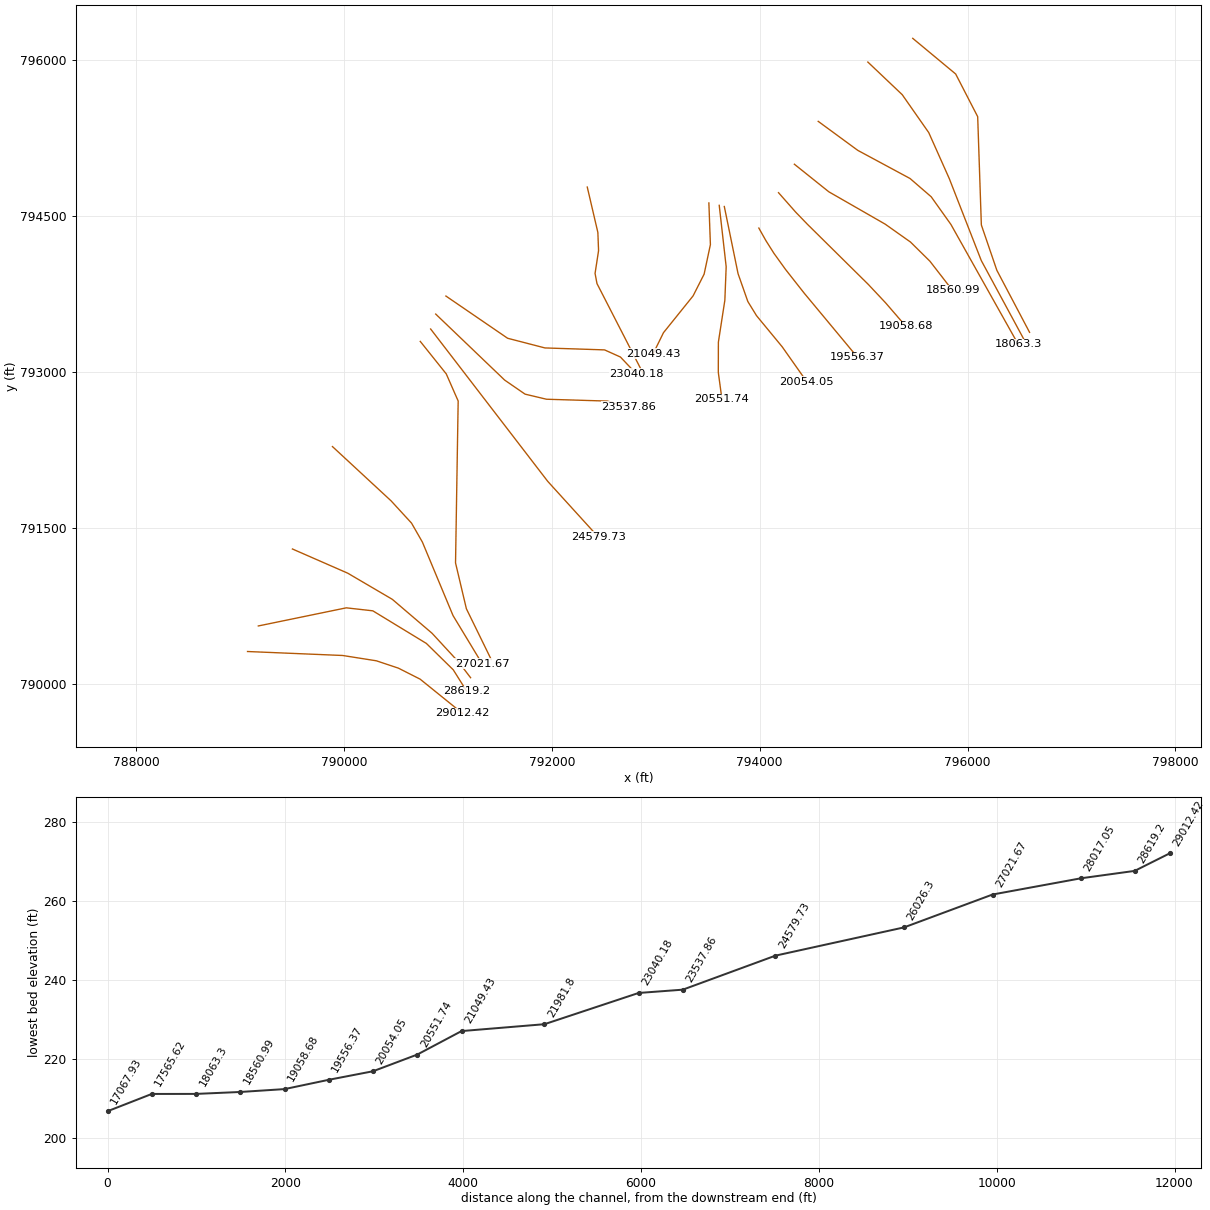
HEC-RAS study 17465_ras.prj: 17465

--- 17465_ras.g01 (geometry) --- (continued)

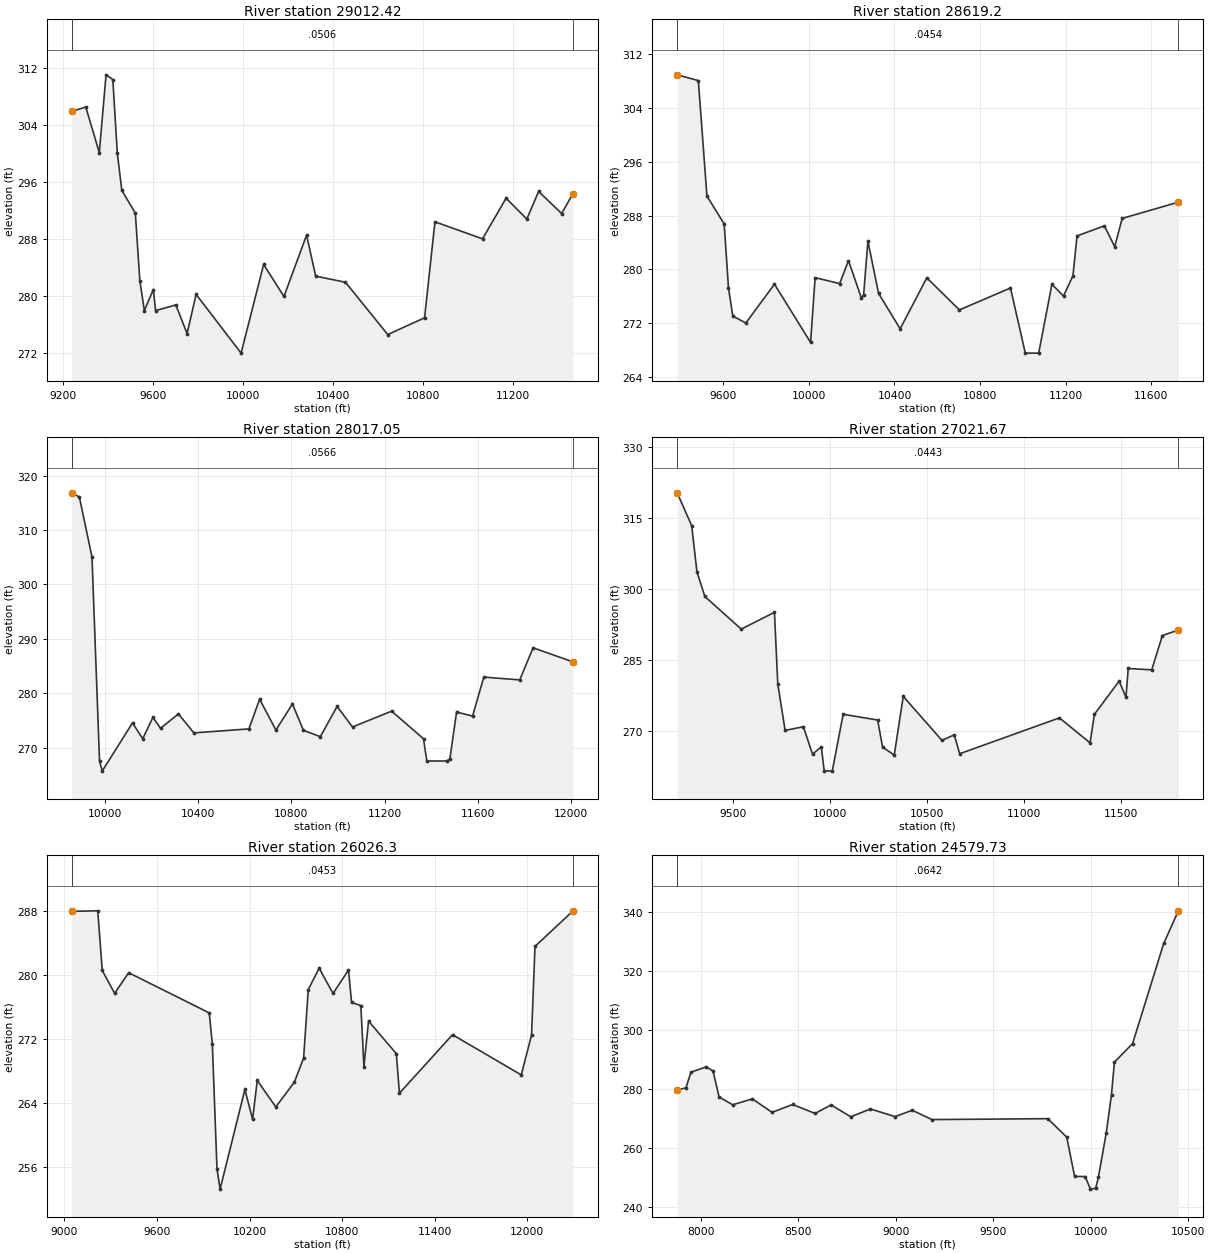
Type RM Length L Ch R = 1 ,29012.42,393.225100,393.225100,393.225100
XS GIS Cut Line= 6
789072.778075606790307.738938287789987.659323484790269.536615103
 790312.16345048790218.417779177790524.463419706 790147.51590693
790732.990048975790041.888025776791141.005240619789712.600045472
#Sta/Elev= 30
 9238.93305.88389301.338306.49549361.507   300.19391.544311.01149421.582310.3547
9441.607300.02529461.632294.79869521.683291.61919541.689 282.1669561.695  277.95
9601.706280.89469611.709277.93719701.735278.7404 9751.75274.71669791.762280.2254
9991.824271.980910092.01284.412910182.29279.925110282.88288.523410323.35 282.781
10455.74281.920110643.76274.584910807.43276.935610853.51290.400411064.95288.0097
11169.81293.7056 11261.9290.785511314.41294.655611416.72291.556111466.72294.3564
#Mann= 3 , 0 , 0
 9238.93  0.0506       0 9238.93  0.0506       011466.72  0.0506       0
#XS Ineff= 2 , 0
       0                10082.52       0
Bank Sta=9238.93,11466.72
Exp/Cntr=0.3,0.1

Type RM Length L Ch R = 1 , 28619.2,602.149200,602.149200,602.149200
XS GIS Cut Line= 6
789176.362996876 790553.53366676790022.701934457790727.948934019
790278.102339506790699.193814129790793.381247222 790385.33786872
791052.079095393790131.410229012791181.860016197789925.044878215
#Sta/Elev= 30
9384.981308.92089483.698308.0634 9523.82 290.9019604.328286.7579 9624.49277.2741
9644.653273.06519705.621272.03349839.431277.801910008.01269.143510029.18278.7793
10143.96 277.88210185.01281.305110245.62275.7273 10255.7276.169510275.72284.2123
10325.76276.418210426.44271.167210551.03278.741210703.06273.977510941.76 277.234
11011.01 267.55211073.51 267.55211135.38277.778211189.58276.043211233.53279.0388
11252.75284.977411380.32286.471911428.68283.367911463.44 287.57411726.05289.9942
#Mann= 3 , 0 , 0
9384.981  0.0454       09384.981  0.0454       011726.05  0.0454       0
#XS Ineff= 2 , 0
       0                10282.82       0
Bank Sta=9384.981,11726.05
Exp/Cntr=0.3,0.1

Type RM Length L Ch R = 1 ,28017.05,995.374200,995.374200,995.374200
XS GIS Cut Line= 6
789504.588215292791294.063164651790036.780001789791061.308789313
790465.455826938 790809.82799007790848.369612187790482.892944753
791103.518122643790206.231569499791218.629314154 790055.78015992
#Sta/Elev= 30
9859.098316.82799891.921316.05629945.887305.03989978.266267.61179989.502265.6912
 10119.7274.556810163.43 271.63810207.17  275.5810239.97273.557310316.51276.2127
10382.76 272.71610618.76273.452610664.59 278.90310734.44273.235810805.19278.0312
10852.36 273.18810924.91272.018810996.64277.575411062.74273.811211230.56  276.71
11367.12271.639611381.43267.552911466.57 267.55211480.06267.897311508.87276.5576
11577.36275.799711625.71282.968111779.65282.454211837.01 288.35412007.55285.7664
#Mann= 3 , 0 , 0
9859.098  0.0566       09859.098  0.0566       012007.55  0.0566       0
#XS Ineff= 2 , 0
       0                10645.39       0
Bank Sta=9859.098,12007.55
Exp/Cntr=0.3,0.1

Type RM Length L Ch R = 1 ,27021.67,995.374300,995.374300,995.374300
XS GIS Cut Line= 6
789889.743727516792279.371543402790454.486882811791756.498762484
790650.423524825791542.972576149790754.819242538791360.683870013
791049.710393088790653.356797401791330.936285908790188.374256469
#Sta/Elev= 30
9213.658320.41179288.196313.46429315.335303.73219356.045298.49559543.446291.6018
9714.424295.14789731.582280.00929769.417270.17849863.325270.96959910.617265.1649
9955.621 266.7139970.648261.659910012.12261.578110068.29 273.59610245.85272.3824
10271.06266.655110331.33 264.96810377.66277.377310577.11268.074810640.33 269.251
10668.37265.255411182.02272.836611339.64 267.55211362.33273.600111489.32280.6062
11524.56277.201811536.32 283.27611657.28282.988311712.03290.239411794.49291.4164
#Mann= 3 , 0 , 0
9213.658  0.0443       09213.658  0.0443       011794.49  0.0443       0
#XS Ineff= 2 , 0
       0                10255.16       0
Bank Sta=9213.658,11794.49
Exp/Cntr=0.3,0.1

Type RM Length L Ch R = 1 , 26026.3,1446.568100,1446.568100,1446.568100
XS GIS Cut Line= 6
790734.501933429793291.182470893790984.528304884792978.695562415
791099.118761171792717.675567376791073.740403746791160.158928413
791178.073355075790719.210006999791417.241109263790230.397481399
#Sta/Elev= 30
 9046.89288.02139215.614288.08159244.753280.61619325.224277.75799415.941280.3407
9938.301275.31229958.417271.4186 9988.59255.791310008.73253.262210169.56265.7295
10219.56261.987110249.57266.859710369.64263.545510489.94266.637310550.18269.6649
10580.31278.227610650.59280.910510740.88277.742210841.07280.672510861.09276.6154
10921.11276.227310941.11268.600310971.12274.284711151.23270.211711171.28265.2599
11515.38272.582711961.07 267.55212027.82272.5399 12050.2 283.63412295.84288.0599
#Mann= 3 , 0 , 0
 9046.89  0.0453       0 9046.89  0.0453       012295.84  0.0453       0
#XS Ineff= 2 , 0
       09908.794        10817.06       0
Bank Sta=9046.89,12295.84
Exp/Cntr=0.3,0.1

Type RM Length L Ch R = 1 ,24579.73,1041.867500,1041.867500,1041.867500
XS GIS Cut Line= 3
790834.181061864793410.587782875 791961.00215745791944.508723035
792445.656392068791411.389064938
#Sta/Elev= 30
7880.168279.67417925.052280.34987950.277285.64948029.199287.45268063.789 286.093
8094.838277.27548164.689 274.6368265.589276.63768366.488272.08378472.262274.7344
 8587.13271.70788669.187274.59068770.086 270.5748870.986273.2189 8997.11 270.638
9085.398272.78129186.297269.63299779.793269.94069877.249263.70019917.793250.4161
9971.851250.3585 9998.88246.111710025.91246.405710039.42250.084610079.97265.1051
10106.85278.095110121.71289.039810215.11295.360910374.44 329.18610449.74340.2336
#Mann= 3 , 0 , 0
7880.168  0.0642       07880.168  0.0642       010449.74  0.0642       0
#XS Ineff= 2 , 0
       09764.942                       0
Bank Sta=7880.168,10449.74
Exp/Cntr=0.3,0.1

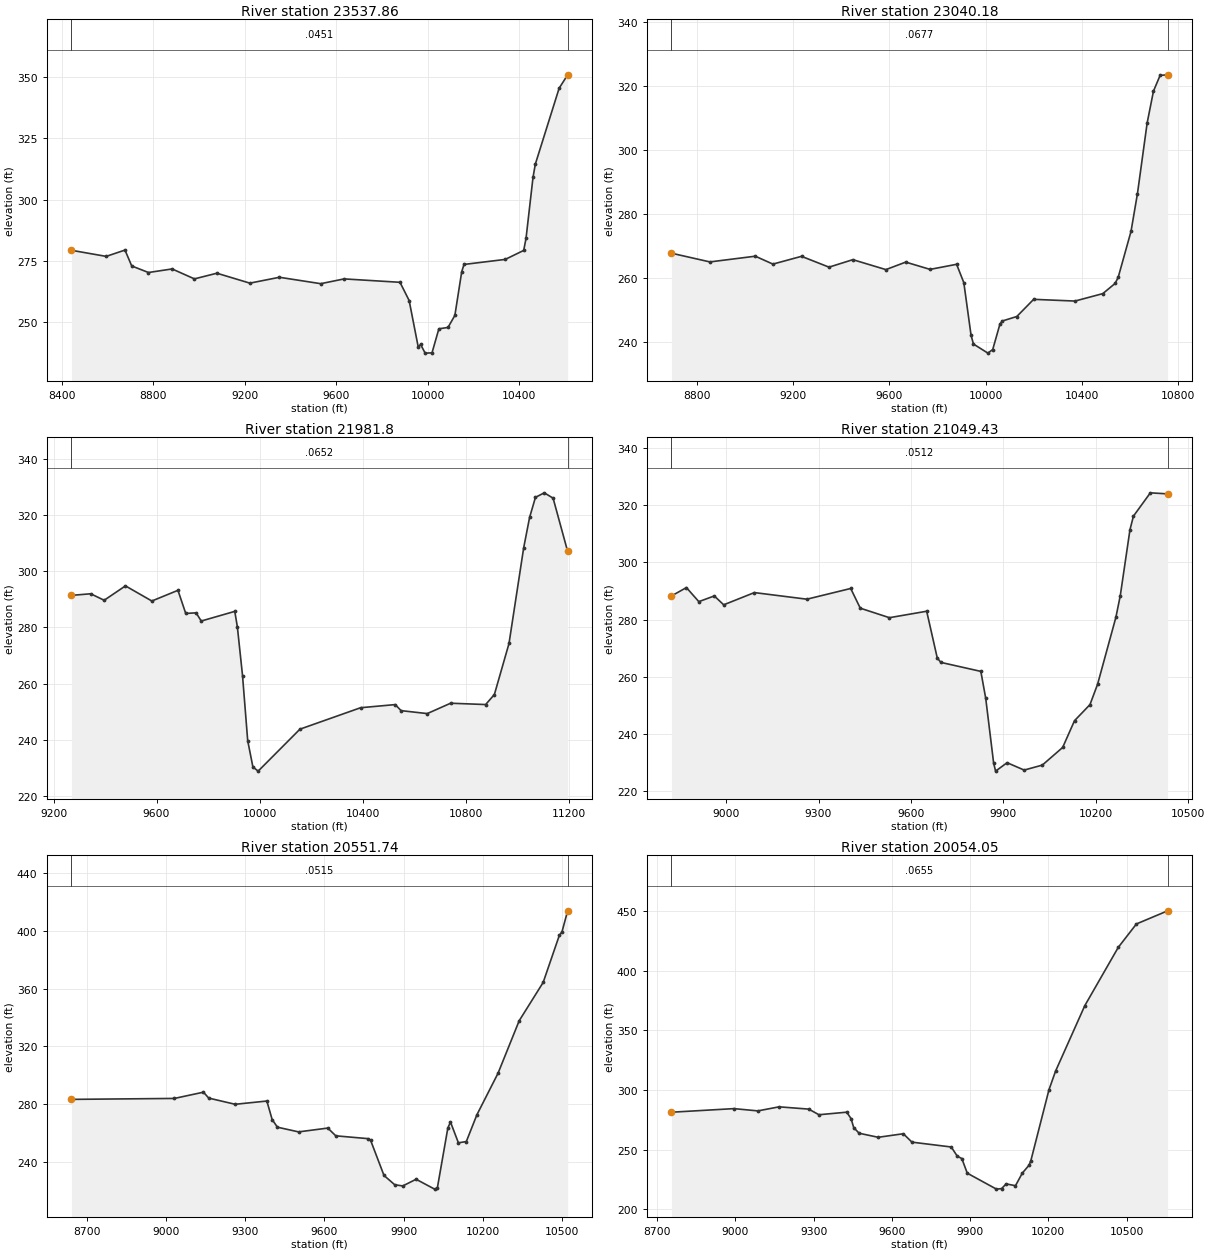
Type RM Length L Ch R = 1 ,23537.86,497.687100,497.687100,497.687100
XS GIS Cut Line= 6
790883.152760838793554.014368636791546.222287945792919.081907613
791742.756418049792783.741411918791949.062419556792734.824362759
792535.152474115792717.056984033 792739.69296994792661.749602517
#Sta/Elev= 30
8442.004279.34228593.855276.86158676.011279.43728705.564272.96118778.759270.3033
8882.191271.75648979.702267.71129078.015270.01579222.152265.97969351.601268.3631
9532.139265.75729634.547267.70179878.831266.31889918.854258.90819958.855239.8773
9968.855 241.0569988.856237.503810018.86237.613810048.86247.398110088.86247.9569
10118.86252.843510148.86270.649110158.87 273.586 10339.1 275.63210419.88279.2908
10430.06 284.17410460.61308.993510470.79314.406810574.84345.2722 10612.1350.7313
#Mann= 3 , 0 , 0
8442.004  0.0451       08442.004  0.0451       0 10612.1  0.0451       0
#XS Ineff= 2 , 0
       0                               0
Bank Sta=8442.004,10612.1
Exp/Cntr=0.3,0.1

Type RM Length L Ch R = 1 ,23040.18,1058.372700,1058.372700,1058.372700
XS GIS Cut Line= 6
790981.278329518793727.511750945791574.913324436793321.402314505
791933.680457044793228.380517133792507.532979973793209.500856662
792660.215238431793140.866926862792813.874595574792978.534981262
#Sta/Elev= 30
8694.383267.89168854.298265.16639042.909266.95429116.088264.48589234.968266.9137
9349.271263.53159448.285265.87049585.774262.76419668.052265.10829769.255262.8326
9879.592264.42139909.596258.6859  9939.6242.27839949.613239.5096 10009.7236.6661
10029.74 237.799 10059.8245.770110069.81246.712610129.82248.109910199.85253.4754
10371.58252.9389 10487.2255.2603 10538.4258.445810551.28260.368110604.46274.6999
10631.26286.504910671.56308.581510697.82318.535210725.43323.466510756.63323.6291
#Mann= 3 , 0 , 0
8694.383  0.0677       08694.383  0.0677       010756.63  0.0677       0
#XS Ineff= 2 , 0
       0                               0
Bank Sta=8694.383,10756.63
Exp/Cntr=0.3,0.1

Type RM Length L Ch R = 1 , 21981.8,932.375800,932.375800,932.375800
XS GIS Cut Line= 6
792341.056686114794776.202629724 792443.12459018794338.742624502
792449.753262656794163.912397806792416.154674991793945.005161056
792434.604189269793847.461558255792881.861500362792976.190355092
#Sta/Elev= 30
9269.775291.42749344.516291.99619396.775289.68159479.448294.81319581.901289.4186
9683.283293.22869713.528284.97999753.704285.20419773.778282.28129903.908285.7215
9913.957280.23569934.054262.84559954.151239.61929974.386230.23639994.762228.7642
10157.01243.723310392.71251.373510527.19 252.48610549.73250.332910651.48249.2803
10742.15252.975610878.16252.504810912.16 256.08210968.94274.2762   11026308.4318
11048.83319.199311071.65326.380111105.89327.988911140.17326.086111196.66307.1012
#Mann= 3 , 0 , 0
9269.775  0.0652       09269.775  0.0652       011196.66  0.0652       0
#XS Ineff= 2 , 0
       0                               0
Bank Sta=9269.775,11196.66
Exp/Cntr=0.3,0.1

Type RM Length L Ch R = 1 ,21049.43,497.687200,497.687200,497.687200
XS GIS Cut Line= 6
793511.067343835794623.206473642793525.760200106794222.593489517
793465.227782084793938.134276849793359.110553997793728.933524222
793074.269407986793374.979652258792974.453670277793171.948164924
#Sta/Elev= 30
8822.689288.2806 8871.28291.20968911.575286.29328961.739288.2874 8992.27285.1824
 9091.89 289.4619262.284287.1492 9404.52290.89769435.528284.01149530.137280.6815
9651.099282.93859685.461266.5812 9697.18  265.059826.898261.90549842.692252.5151
9868.427229.83779874.781227.0255 9912.13229.97099967.519 227.39210026.38229.1305
10092.48235.307810130.92244.6618 10181.1250.2821 10205.8257.401710265.14280.7785
10279.47288.3801 10310.9311.442610322.25316.2127 10377.1324.346510433.12323.9789
#Mann= 3 , 0 , 0
8822.689  0.0512       08822.689  0.0512       010433.12  0.0512       0
#XS Ineff= 2 , 0
       0                               0
Bank Sta=8822.689,10433.12
Exp/Cntr=0.3,0.1

Type RM Length L Ch R = 1 ,20551.74,497.687100,497.687100,497.687100
XS GIS Cut Line= 6
793610.666822723794600.221978514793677.430244179 794009.52020941
793664.801845178793687.607041197793602.511751059793283.939807162
793601.757824759792992.834814684793636.869041792792734.101814108
#Sta/Elev= 30
 8642.26283.29389031.858283.9435 9142.07288.27859162.086284.18079262.145279.8863
9382.166282.14399402.185269.32719422.204264.01349502.368260.75589612.949263.4044
9643.195258.03549764.775256.08319774.939 254.9749825.759230.57399866.415224.1218
9896.907 223.2949947.374227.925410017.52221.085710027.53221.577810067.54 263.409
10077.54 267.61910107.55 253.18510137.56254.070810177.58272.600410257.59301.3883
10337.77337.804110428.56364.357710489.62396.8752 10499.8399.409710521.26413.9755
#Mann= 3 , 0 , 0
 8642.26  0.0515       0 8642.26  0.0515       010521.26  0.0515       0
#XS Ineff= 2 , 0
       0                               0
Bank Sta=8642.26,10521.26
Exp/Cntr=0.3,0.1

Type RM Length L Ch R = 1 ,20054.05,497.687100,497.687100,497.687100
XS GIS Cut Line= 6
793659.534961344794588.944715756 793791.80514467793942.793688124
793885.818627453793674.983387209793969.440766052793538.744138849
794216.295033108793239.348677357794452.313137635792904.409710831
#Sta/Elev= 30
8755.025281.33728994.683284.35339086.296282.44979167.729285.85159281.321283.9474
9320.418279.22949426.999281.37249443.453276.03929453.807268.47339474.515263.7204
9547.651260.31679643.909263.29679677.053256.24829827.638252.1916 9851.09244.3992
9868.246242.53029889.094230.2396   10001216.860510020.68217.294210038.23  221.24
10073.95219.728310100.14230.2747 10126.1236.9504   10133240.796910202.28300.1135
10227.61315.7741 10339.8370.712310467.99419.545710537.59439.179910657.22450.1838
#Mann= 3 , 0 , 0
8755.025  0.0655       08755.025  0.0655       010657.22  0.0655       0
#XS Ineff= 2 , 0
       0                               0
Bank Sta=8755.025,10657.22
Exp/Cntr=0.3,0.1

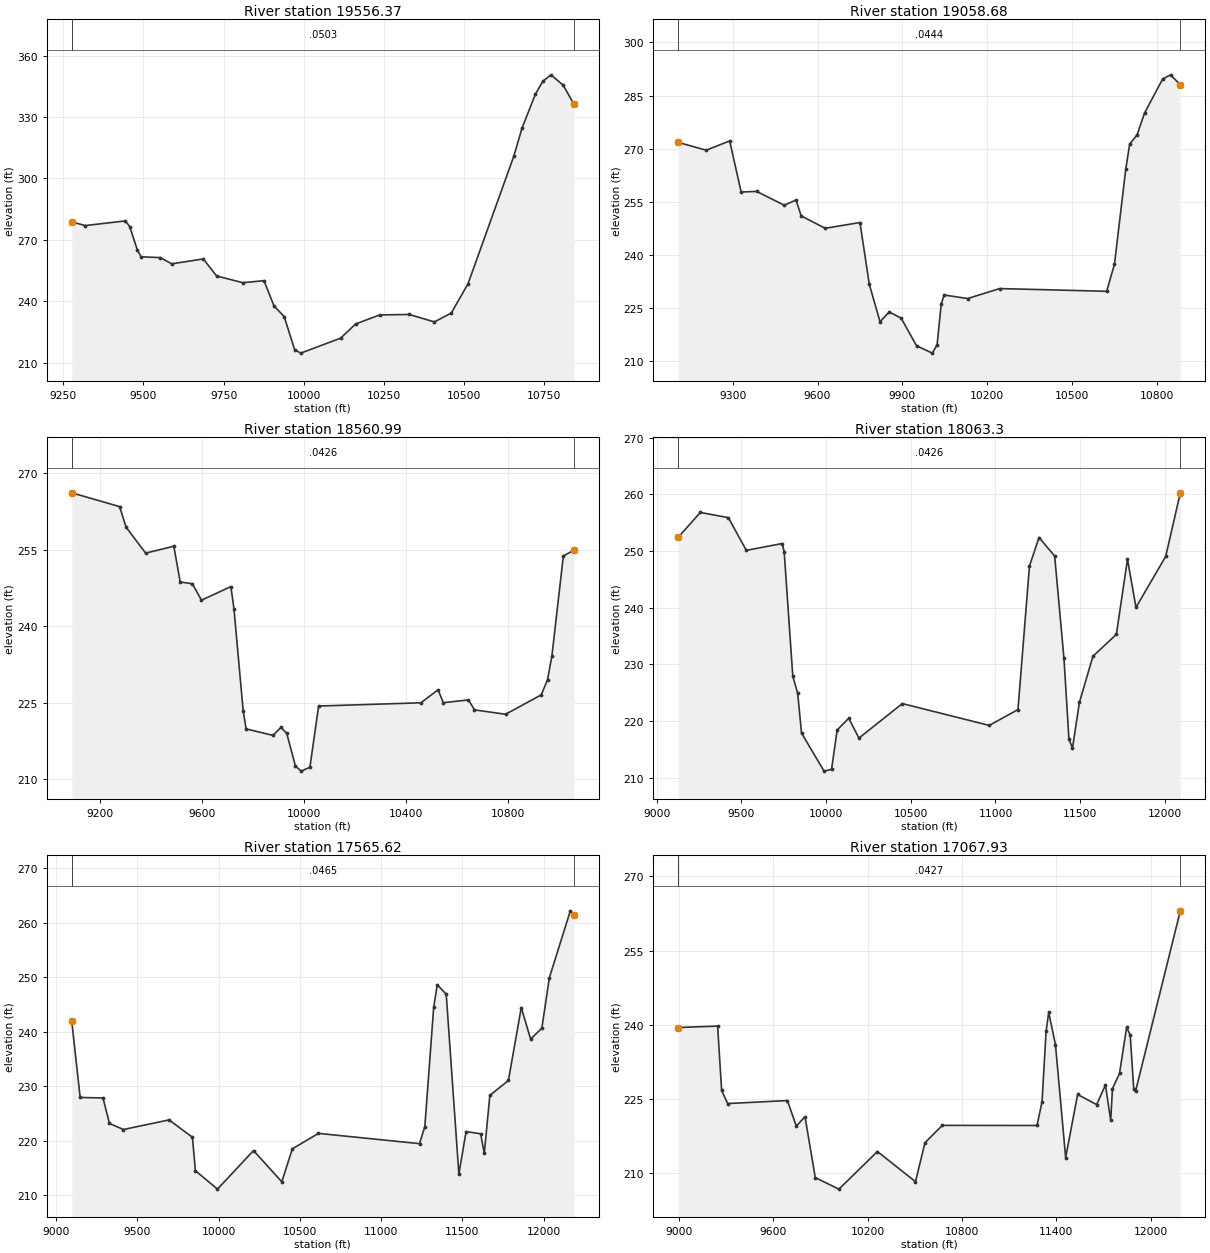
Type RM Length L Ch R = 1 ,19556.37,497.687100,497.687100,497.687100
XS GIS Cut Line= 6
793991.651711973794381.637899292794059.434177289794261.194174194
794137.108178219794138.370249329794248.803518588793983.178967528
794428.385715216793754.989479767794940.288227234793139.131905809
#Sta/Elev= 30
9276.381278.79339318.249276.98799443.716  279.279457.418276.42919481.135264.9451
9492.914261.73399552.073261.34989588.332 258.3179686.718260.68789727.916252.4019
9809.716249.0943 9876.03250.08449906.801237.85439939.163232.46169971.524216.3934
9990.509214.699810114.89221.9989 10161.7228.937610237.03233.353510328.89233.5706
10407.62229.945310460.01234.2687 10512.1248.489110655.01310.816310680.78324.5625
10722.16341.062710745.19  347.3610770.96350.602510809.47345.4953 10842.4336.3051
#Mann= 3 , 0 , 0
9276.381  0.0503       09276.381  0.0503       0 10842.4  0.0503       0
#XS Ineff= 2 , 0
       0                               0
Bank Sta=9276.381,10842.4
Exp/Cntr=0.3,0.1

Type RM Length L Ch R = 1 ,19058.68,497.687200,497.687200,497.687200
XS GIS Cut Line= 6
794181.117262872 794721.97416663794345.435563948794535.786801164
794456.415819849794420.713386755795042.800501656793841.470823481
795212.052102543793661.280901971795404.679987347793438.262143035
#Sta/Elev= 30
9107.752271.78779206.674269.58349289.525272.20259330.127257.7917 9385.01257.9606
 9482.26254.06499524.071255.53499542.314251.05069627.268247.55919750.077249.1858
9783.017231.75489820.952221.20889853.265223.95269895.353222.24419950.047214.4112
10005.79212.344110022.71 214.71510037.18226.135110047.28228.749710130.42  227.74
10244.02 230.55810621.99229.782710649.52237.431110689.71264.376610703.37271.3347
10729.46273.9016 10755.8280.0665 10819.9289.677710847.82290.844410882.24288.0319
#Mann= 3 , 0 , 0
9107.752  0.0444       09107.752  0.0444       010882.24  0.0444       0
#XS Ineff= 2 , 0
       0                               0
Bank Sta=9107.752,10882.24
Exp/Cntr=0.3,0.1

Type RM Length L Ch R = 1 ,18560.99,497.687100,497.687100,497.687100
XS GIS Cut Line= 6
794333.561939007794995.809973748794665.243486375794730.371217507
795206.928745984794419.416581735795450.714094365794247.108371446
795637.573045618794062.789271268795855.377071747793781.629853753
#Sta/Elev= 30
 9090.78266.13929278.102263.44459303.813259.39849380.304254.32459490.658255.6783
9515.715248.67299563.373248.32229599.111245.10489714.305247.77129726.362243.4156
9762.429223.43079773.892219.89199879.226218.62059910.517  220.199933.182219.0152
 9967.18212.60869989.845211.616610023.91212.374710058.11224.367410458.93225.0032
10526.07227.550610546.83225.026710645.34225.567310668.88223.620910790.66222.7582
10930.69226.564910955.16229.547310972.23234.159411017.06253.762911058.23254.8862
#Mann= 3 , 0 , 0
 9090.78  0.0426       0 9090.78  0.0426       011058.23  0.0426       0
#XS Ineff= 2 , 0
       0                               0
Bank Sta=9090.78,11058.23
Exp/Cntr=0.3,0.1

Type RM Length L Ch R = 1 , 18063.3,497.687100,497.687100,497.687100
XS GIS Cut Line= 6
794563.075380375795408.084118408794943.574497514795129.145581361
795446.397274522794858.333375718795649.986186626794682.463538221
 795839.39906545794416.725325968796487.710489808793262.034379217
#Sta/Elev= 30
9126.518252.41929257.122 256.7939422.443255.87799528.567250.10379740.643251.3128
9752.169249.84549803.065227.88019832.063224.8454 9854.57 217.8469987.623211.1266
 10031.9211.439510065.15218.394810133.37220.460210193.68216.956510449.75223.0531
10963.18219.195411132.84221.9957 11200.7247.341811257.26252.3665 11349.5249.1059
11404.41 231.02311433.81216.821411454.57215.1591 11495.7 223.25711575.58231.4083
11713.96235.2732 11779.6248.530311829.78240.041912005.36249.040712091.53260.2595
#Mann= 3 , 0 , 0
9126.518  0.0426       09126.518  0.0426       012091.53  0.0426       0
#XS Ineff= 2 , 0
       0                11277.87       0
Bank Sta=9126.518,12091.53
Exp/Cntr=0.3,0.1

Type RM Length L Ch R = 1 ,17565.62,497.687100,497.687100,497.687100
XS GIS Cut Line= 6
795040.534414071795978.673368071795371.111489671795664.969553267
795626.313859768795300.043963894795823.939130489794857.369896397
796131.770872161794069.038281609796538.663684862793316.627088207
#Sta/Elev= 30
9096.501241.91169148.249227.95089288.656227.85799328.403223.18219414.437222.0654
9694.927223.82669838.998220.65139857.338214.51339993.312211.118810214.99218.2008
10389.17212.465810454.08218.520910614.89221.3561 11236.7219.468111269.43222.6134
11323.97244.531411345.94248.643811401.03246.918611478.86213.904211523.42221.6888
11612.78221.279411635.42 217.68611669.38228.328411783.78231.069511862.93244.4567
11920.51238.666911989.62240.6755 12035.9249.935212164.92262.219412186.47261.5394
#Mann= 3 , 0 , 0
9096.501  0.0465       09096.501  0.0465       012186.47  0.0465       0
#XS Ineff= 2 , 0
       09737.796           11371       0
Bank Sta=9096.501,12186.47
Exp/Cntr=0.3,0.1

Type RM Length L Ch R = 1 ,17067.93,1493.061400,1493.061400,1493.061400
XS GIS Cut Line= 6
795472.323428711796206.887486839795885.538135843795863.622276978
796097.132680231795453.258506728796132.444000358794411.474075467
796281.631549693793975.104385834796596.257078163793378.334295319
#Sta/Elev= 30
8996.258239.43569246.708239.72899272.341226.7005 9310.79 224.0589690.885224.6546
9747.264219.47689802.484221.41149867.762209.072410018.32206.742610263.09214.3483
10505.21208.252810565.64216.137210675.89219.642511278.21219.616511310.07224.4077
11335.84238.656911352.61242.523611395.54235.940911460.26213.130211536.43225.8904
11657.61223.844111713.17 227.81811746.78220.673711757.98227.080611802.83230.1496
11848.13239.462911870.78237.962111893.43 226.93311904.76 226.53412189.52263.0475
#Mann= 3 , 0 , 0
8996.258  0.0427       08996.258  0.0427       012189.52  0.0427       0
#XS Ineff= 2 , 0
       09650.966         11370.2       0
Bank Sta=8996.258,12189.52
Exp/Cntr=0.3,0.1