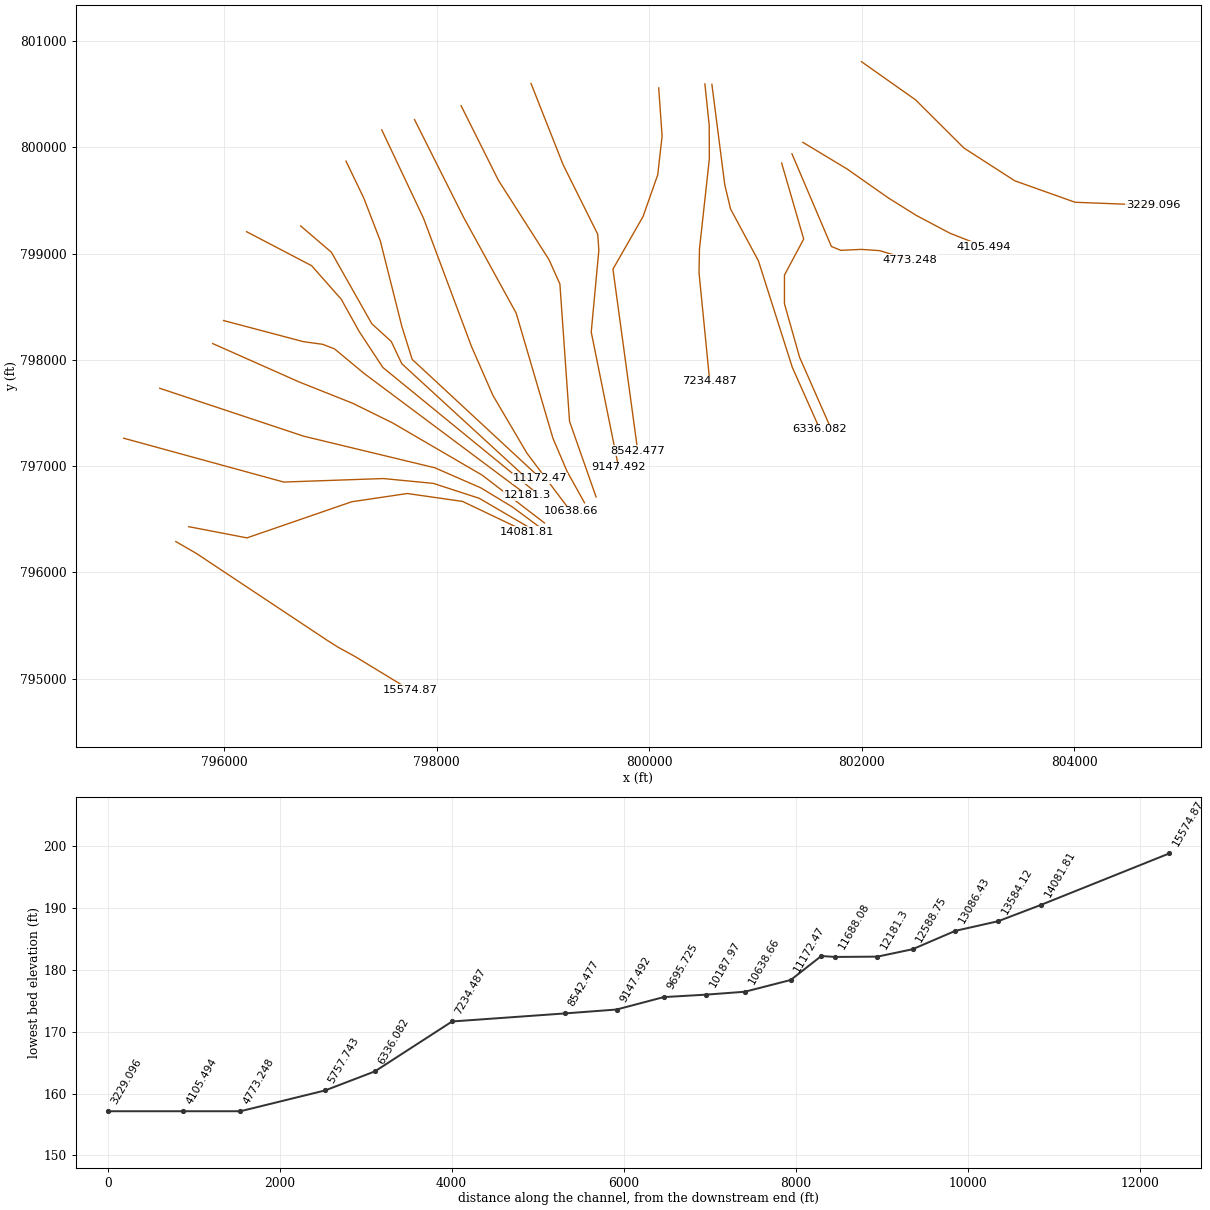
HEC-RAS study 17465_ras.prj: 17465

--- 17465_ras.g01 (geometry) --- (continued)

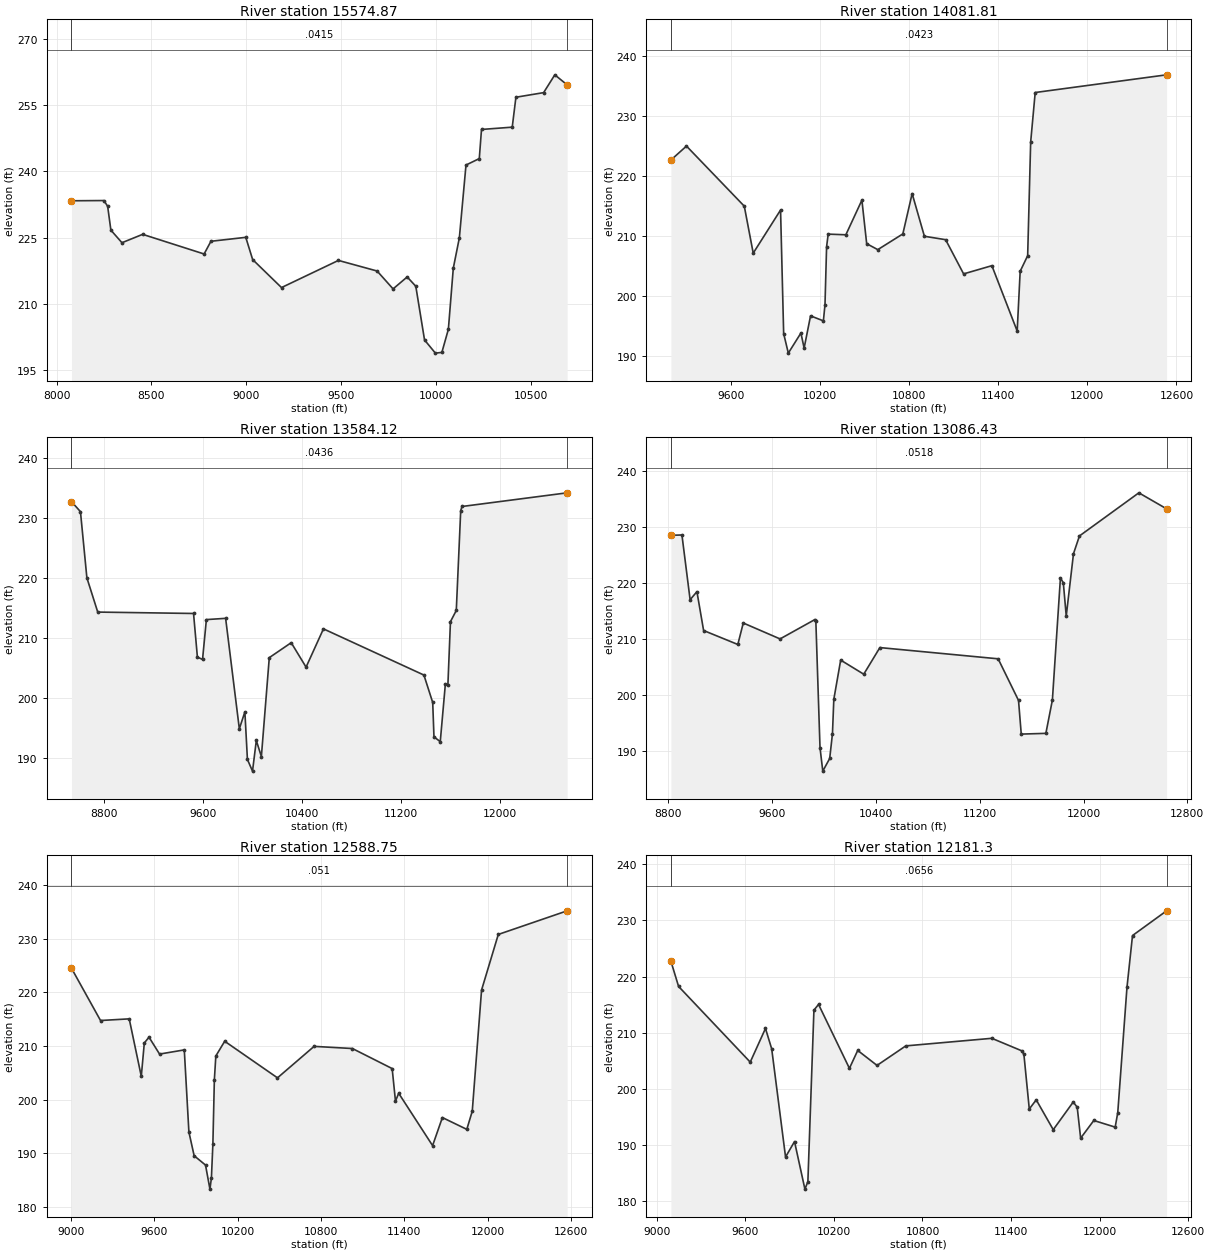
Type RM Length L Ch R = 1 ,15574.87,1493.061400,1493.061400,1493.061400
XS GIS Cut Line= 6
795545.086300257796290.278642997 795736.58087337796179.802191392
796981.815414757795352.978792116797074.439923495795294.996901378
797234.581018358795206.847885251797750.056578403794893.428579284
#Sta/Elev= 30
8078.313233.34748248.966 233.3998268.977232.1142 8286.02226.7065 8344.33 223.853
8453.385225.75028777.159221.30298813.134224.18118996.632225.07279032.871220.0424
9184.874213.70179484.665219.84819688.522217.44959772.654213.40369846.916216.1074
9892.325213.99969938.347201.84989995.424 198.86610029.65199.0279 10063.9204.2641
10089.85218.086610121.76224.960510156.76241.437210226.77242.895310238.44249.4897
10400.33250.007510419.74256.780510565.68257.823510624.64261.853310689.56259.5806
#Mann= 3 , 0 , 0
8078.313  0.0415       08078.313  0.0415       010689.56  0.0415       0
#XS Ineff= 2 , 0
       08909.054                       0
Bank Sta=8078.313,10689.56
Exp/Cntr=0.3,0.1

Type RM Length L Ch R = 1 ,14081.81,497.687100,497.687100,497.687100
XS GIS Cut Line= 6
795667.149712407796430.171542323796214.795417732796324.905667021
797201.222999146796664.877266841797723.589553396 796742.26839351
   798243.119597796667.874792428798846.637804894796380.237779702
#Sta/Elev= 30
9196.617222.7086 9301.53225.03729690.721215.02039750.842207.19499934.861214.3793
9955.765193.78549987.122190.534510071.93 193.88310093.54191.374910136.75196.7448
10223.19195.9095   10234198.5984 10244.8208.2722 10255.6210.364110374.46 210.255
10482.47216.0243 10514.6208.7712 10589.4 207.77910758.03 210.39810820.65217.1185
 10903.2210.005711046.06209.437411167.08 203.73811357.43205.105811527.81194.2121
 11547.9204.176111598.32  206.7711618.61225.719911649.05233.961412533.46236.9085
#Mann= 3 , 0 , 0
9196.617  0.0423       09196.617  0.0423       012533.46  0.0423       0
#XS Ineff= 2 , 0
       09906.963        10732.92       0
Bank Sta=9196.617,12533.46
Exp/Cntr=0.3,0.1

Type RM Length L Ch R = 1 ,13584.12,497.687100,497.687100,497.687100
XS GIS Cut Line= 6
795054.892736256797262.562563151796560.215210617796850.157758787
797497.477650642796883.117513061797968.735352069796837.547122434
798400.717632711796696.897308558798898.106887519796406.234918386
#Sta/Elev= 30
8535.478232.80158608.307231.11778660.248220.09488748.029214.39089522.469214.1573
9553.634206.89769595.187206.49549626.351 213.1399781.931213.34789892.707194.9417
9937.544197.76359958.103  189.849999.221187.893710030.04192.998710070.87190.3168
10134.86206.799810312.08209.290610432.22205.217210572.76211.594911384.96203.8981
11456.05199.3276 11466.2193.612311517.06192.799411558.26202.384811578.86202.2894
11599.46212.789311646.63214.660611682.41231.288211692.92231.981412542.79234.2573
#Mann= 3 , 0 , 0
8535.478  0.0436       08535.478  0.0436       012542.79  0.0436       0
#XS Ineff= 2 , 0
       09876.456        10607.84       0
Bank Sta=8535.478,12542.79
Exp/Cntr=0.3,0.1

Type RM Length L Ch R = 1 ,13086.43,497.687200,497.687200,497.687200
XS GIS Cut Line= 6
795393.987373173797732.392481744 796750.37861824797281.044934183
797982.182730705796984.517713904798414.408973843796795.888275906
 798714.38203609796614.339810356798955.614768624796435.282266468
#Sta/Elev= 30
8819.046228.56218904.166228.62158967.208217.02949019.743218.47289071.229211.5155
9334.954209.01499376.982212.85959660.671210.01069929.345213.48089936.442213.2067
9968.552190.53769989.958186.338210043.29188.603910064.49193.028110075.06199.1997
10127.93206.218610305.69203.692210430.12208.458611341.73206.4479 11498.8199.0011
11519.85192.968611709.62193.1012 11759.9199.068911821.95220.936911844.26220.0509
11866.61214.103411922.48225.260711968.45 228.44612426.45236.167312640.13233.3045
#Mann= 3 , 0 , 0
8819.046  0.0518       08819.046  0.0518       012640.13  0.0518       0
#XS Ineff= 2 , 0
       09901.087        10505.46       0
Bank Sta=8819.046,12640.13
Exp/Cntr=0.3,0.1

Type RM Length L Ch R = 1 ,12588.75,407.446500,407.446500,407.446500
XS GIS Cut Line= 6
795892.415634602798153.196669698 796705.13623482 797792.15778029
797211.577589273797590.498101458797584.446628153 797406.81638898
798427.839054286796915.124243841799014.387237787796464.968360603
#Sta/Elev= 30
 9004.35224.51979213.589214.7699 9420.02215.07959506.938204.37629528.667210.5887
9562.445211.66529638.439208.51869816.381209.29759849.537194.00579887.222189.5838
9969.149187.844910000.93183.361910011.54185.425610022.16191.767810032.78203.7267
10043.39208.162710107.11 210.90710487.06204.089110750.51209.953211026.13209.5517
11312.29205.818111336.12199.758411359.24201.216311603.23191.465411673.64196.6964
11849.41194.495411888.65197.8719 11955.6220.441112076.07230.803712571.45235.2016
#Mann= 3 , 0 , 0
 9004.35   0.051       0 9004.35   0.051       012571.45   0.051       0
#XS Ineff= 2 , 0
       09758.358        10172.86       0
Bank Sta=9004.35,12571.45
Exp/Cntr=0.3,0.1

Type RM Length L Ch R = 1 , 12181.3,493.222000,493.222000,493.222000
XS GIS Cut Line= 6
795994.552573442798369.726980001796745.720179409798171.068063349
796926.838404775798146.134764329797038.681107134798103.040817305
797313.820671529797874.347035825798849.818202466796726.657130212
#Sta/Elev= 30
9096.156222.74459148.238 218.242 9633.47204.77339736.711210.76699778.774207.1397
9872.617187.88459933.365 190.63210003.74182.165410023.87183.4984 10064.8214.0194
10096.09215.044110305.17203.6639 10361.4 206.85110492.15204.185310686.84207.6593
11269.58209.009111473.28206.771911486.76206.152611523.22 196.427 11570.3 198.056
 11685.5192.7458 11820.9197.672911847.78196.741211871.02191.236811960.13194.3817
12104.91193.201612122.41  195.7812184.82218.082112222.27227.299412452.99231.6993
#Mann= 3 , 0 , 0
9096.156  0.0656       09096.156  0.0656       012452.99  0.0656       0
#XS Ineff= 2 , 0
       09779.234        10163.07       0
Bank Sta=9096.156,12452.99
Exp/Cntr=0.3,0.1

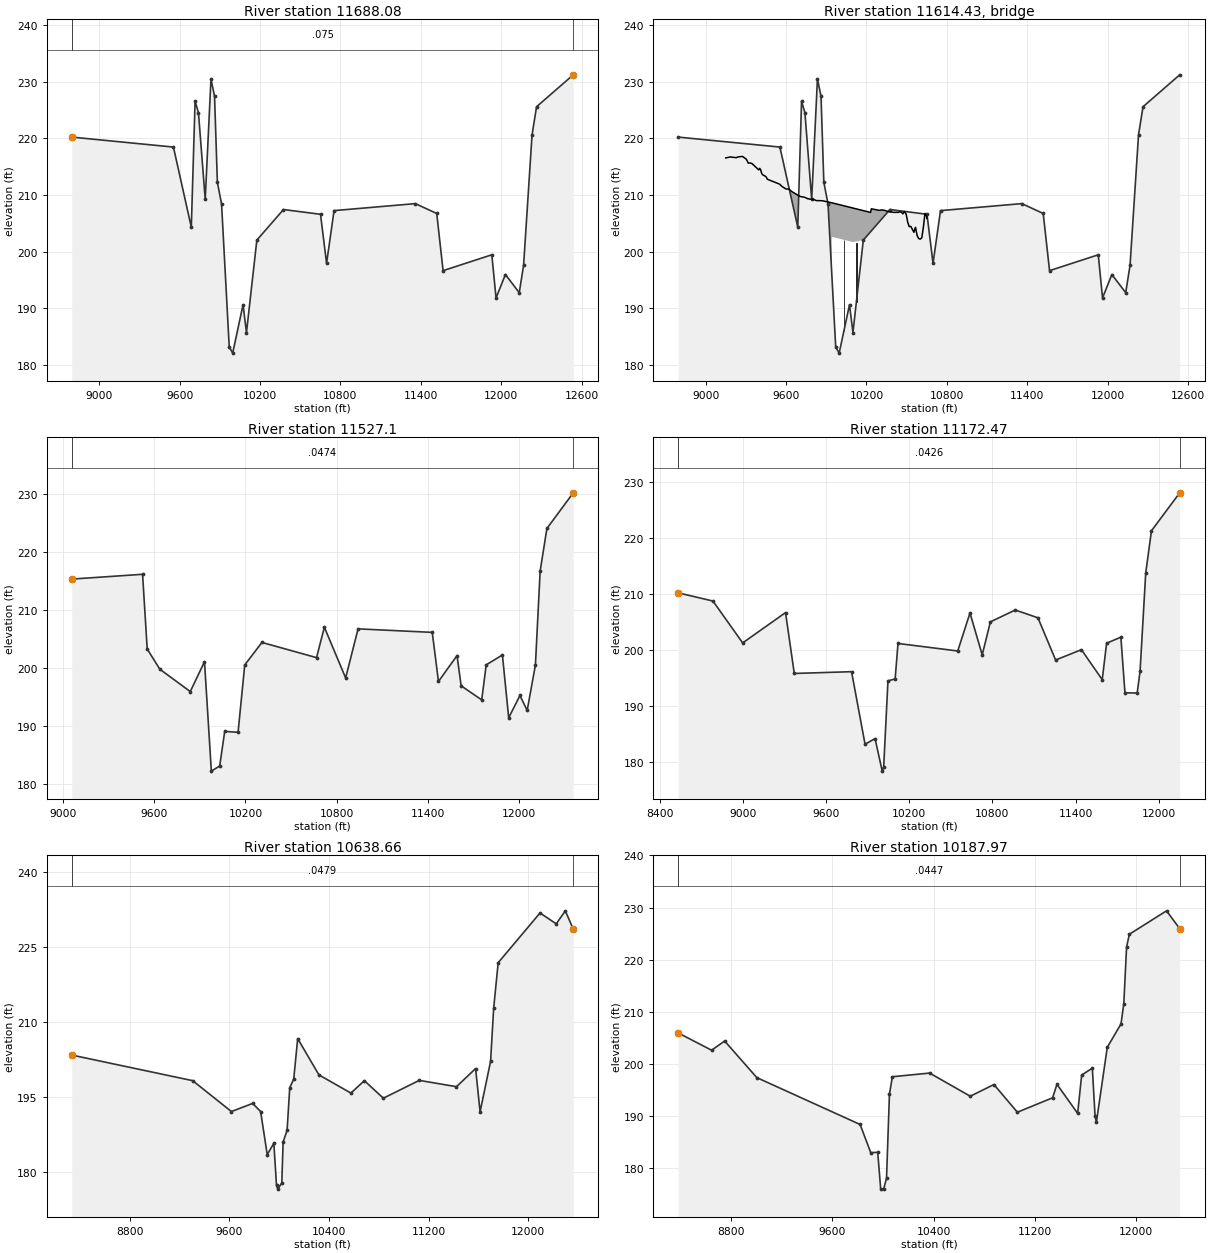
Type RM Length L Ch R = 1 ,11688.08,160.974500,160.974500,160.974500
XS GIS Cut Line= 6
 796210.92931363799205.823796868 796823.14686203798885.879898578
797101.695429593798570.316036105 797270.07594955798267.609483406
797492.704910994 797928.78943707798947.040424705796740.546019092
#Sta/Elev= 30
8795.291220.21129553.936218.45469687.321204.32949715.535226.53059740.675224.5239
 9791.09209.22679834.044230.46169860.721227.41839881.756212.25969913.068208.3992
9970.283183.21819996.069182.116410073.27190.650110098.93185.750110176.26 202.047
10374.93207.437410651.29206.599410696.48197.948910752.24207.248411359.17208.4808
11518.35206.743911565.77196.659611929.28199.458711960.89191.847712030.66195.9756
12133.97 192.77712166.36197.613312229.58220.6173 12263.1 225.56612536.92231.1928
#Mann= 3 , 0 , 0
8795.291   0.075       08795.291   0.075       012536.92   0.075       0
#XS Ineff= 2 , 0
       09892.016        10237.05       0
Bank Sta=8795.291,12536.92
Exp/Cntr=0.3,0.1

Type RM Length L Ch R = 3 ,11614.43,,,
BEGIN DESCRIPTION:
END DESCRIPTION:
Bridge Culvert--1,0,-1,-1, 0
Deck Dist Width WeirC Skew NumUp NumDn MinLoCord MaxHiCord MaxSubmerge Is_Ogee
55.487250,50.000000,2.6,0, 60, 60, , , 0.95, 0, 0,0,,
 9149.73 9185.44 9227.65 9241.72 9275.44 9303.87 9318.09 9332.30 9346.52 9396.47
 9403.39 9410.54 9417.61 9424.61 9446.04 9452.75 9460.26 9551.23 9570.97 9600.72
 9619.34 9644.61 9703.87 9739.43 9763.14 9810.55 9824.23 9869.78 9940.88 9940.88
10214.8810214.8810230.3810236.2110295.3010311.8810330.8910365.8610401.1310436.41
10448.1610459.9210471.6810483.4410495.2010501.9710506.9610518.7110530.4710553.99
10559.0010565.7510578.0110589.2710601.0210612.7810624.5410636.3010648.0610650.06
  216.54  216.71  216.58  216.72  216.80  216.30  215.62  215.65  215.53  214.42
  214.71  214.43  213.84  213.58  213.30  213.14  212.78  211.92  211.48  211.05
  211.06  210.58  209.75  209.59  209.33  209.18  209.02  208.99  208.63  208.63
  207.02  207.02  206.93  207.57  207.29  207.37  207.32  207.06  206.94  206.94
  207.04  206.97  206.68  207.09  206.66  205.93  205.25  204.43  204.47  203.42
  203.86  204.29  202.83  202.32  202.22  202.45  204.37  206.76  206.29  205.88
 -783.46 -783.29 -783.42 -783.28 -783.20 -783.70 -784.38 -784.35 -784.47 -785.58
 -785.29 -785.57 -786.16 -786.42 -786.70 -786.86 -787.22 -788.08 -788.52 -788.95
 -788.94 -789.42 -790.25 -790.41 -790.67 -790.82 -790.98 -791.01 -791.37  202.63
  201.02 -792.98 -793.07 -792.43 -792.71 -792.63 -792.68 -792.94 -793.06 -793.06
 -792.96 -793.03 -793.32 -792.91 -793.34 -794.07 -794.75 -795.57 -795.53 -796.58
 -796.14 -795.71 -797.17 -797.68 -797.78 -797.55 -795.63 -793.24 -793.71 -794.12
 9149.73 9185.44 9227.65 9241.72 9275.44 9303.87 9318.09 9332.30 9346.52 9396.47
 9403.39 9410.54 9417.61 9424.61 9446.04 9452.75 9460.26 9551.23 9570.97 9600.72
 9619.34 9644.61 9712.47 9739.43 9763.14 9810.55 9824.23 9869.78 9925.82 9925.82
10199.8210199.8210230.3810236.2110295.3010311.8810330.8910365.8610401.1310436.41
10448.1610459.9210471.6810483.4410495.2010501.9710506.9610518.7110530.4710553.99
10559.0010565.7510578.0110589.2710601.0210612.7810624.5410636.3010648.0610650.06
  216.54  216.71  216.58  216.72  216.80  216.30  215.62  215.65  215.53  214.42
  214.71  214.43  213.84  213.58  213.30  213.14  212.78  211.92  211.48  211.05
  211.06  210.58  209.66  209.59  209.33  209.18  209.02  208.99  208.71  208.71
  207.11  207.11  206.93  207.57  207.29  207.37  207.32  207.06  206.94  206.94
  207.04  206.97  206.68  207.09  206.66  205.93  205.25  204.43  204.47  203.42
  203.86  204.29  202.83  202.32  202.22  202.45  204.37  206.76  206.29  205.88
 -783.46 -783.29 -783.42 -783.28 -783.20 -783.70 -784.38 -784.35 -784.47 -785.58
 -785.29 -785.57 -786.16 -786.42 -786.70 -786.86 -787.22 -788.08 -788.52 -788.95
 -788.94 -789.42 -790.34 -790.41 -790.67 -790.82 -790.98 -791.01 -791.29  202.71
  201.11 -792.89 -793.07 -792.43 -792.71 -792.63 -792.68 -792.94 -793.06 -793.06
 -792.96 -793.03 -793.32 -792.91 -793.34 -794.07 -794.75 -795.57 -795.53 -796.58
 -796.14 -795.71 -797.17 -797.68 -797.78 -797.55 -795.63 -793.24 -793.71 -794.12
Pier Skew, UpSta & Num, DnSta & Num=  ,10031.54, 2 ,10016.48, 2 , 0 , 0 , 0 ,,
    4.00    4.00
 -791.91  208.09
    4.00    4.00
 -791.82  208.18
Pier Skew, UpSta & Num, DnSta & Num=  ,10124.21, 2 ,10109.15, 2 , 0 , 0 , 0 ,,
    4.00    4.00
 -792.45  207.55
    4.00    4.00
 -792.36  207.64
BR Coef=-1 , 0 , 0 ,, 0 ,,,0.8,0,1,0,
WSPro=,,,, 1 ,,,, 0 ,,,, 0 ,,,,-1 ,-1 ,-1 , 0 , 0 , 0 , 0 , 0
BC Design=,, 0 ,, 0 ,,,,,,

Type RM Length L Ch R = 1 , 11527.1,354.634400,354.634400,354.634400
XS GIS Cut Line= 6
796719.812618434799260.179492101797009.148500502799012.177307442
 797389.26665467798339.502289668797571.746049076798174.021775931
797671.350265145797963.757164598  798898.4293136796837.768241301
#Sta/Elev= 30
9056.853215.29439522.943216.12239553.333203.27049636.461199.79819836.663195.9477
9930.318201.08369975.425182.264610030.35 183.152 10063.3189.095410151.18188.9417
10195.12200.524410308.16204.400510667.64201.784310718.88207.021810858.96198.2935
10940.74206.734511428.83206.129711469.71197.687111591.85202.1381   11619196.9391
11754.23194.516611783.81200.544411890.44202.245911931.71191.439612005.67195.2734
12053.31 192.70612107.59200.508512138.78216.683312183.15224.002112356.55 230.133
#Mann= 3 , 0 , 0
9056.853  0.0474       09056.853  0.0474       012356.55  0.0474       0
#XS Ineff= 2 , 0
       09887.562        10222.17       0
Bank Sta=9056.853,12356.55
Exp/Cntr=0.3,0.1

Type RM Length L Ch R = 1 ,11172.47,533.808900,533.808900,533.808900
XS GIS Cut Line= 6
797146.648289591799869.651487082797314.034705997799521.873784006
 797469.66898483799118.207496032797671.781309932798315.655277506
797769.318867415798004.267101333798974.818202466796886.379352421
#Sta/Elev= 30
8533.657210.25738784.131 208.7938998.684 201.3089307.687206.72589370.821 195.847
9783.903196.16429881.295183.19429953.466184.201910005.14 178.38810015.48179.0493
10046.52194.524810098.25194.868410118.95201.210610549.83199.867410638.07206.6604
10726.31199.165710785.14205.070910964.59207.189711128.25205.797511255.76  198.25
11441.92200.099811591.93194.739911623.43201.249111726.37202.335511755.79192.3842
11844.03192.346811864.69 196.20611905.61213.800711946.98221.354512150.84228.1381
#Mann= 3 , 0 , 0
8533.657  0.0426       08533.657  0.0426       012150.84  0.0426       0
#XS Ineff= 2 , 0
       09627.896        10138.19       0
Bank Sta=8533.657,12150.84
Exp/Cntr=0.3,0.1

Type RM Length L Ch R = 1 ,10638.66,450.686600,450.686600,450.686600
XS GIS Cut Line= 6
797482.916182516800164.138768216797875.269976686799333.889892637
798326.638925612798127.403036635798528.684982334797665.792797813
798849.077527182797121.472877561799260.358021048796575.107231295
#Sta/Elev= 30
8333.472203.33179304.666198.20119615.687192.01699786.221193.64929850.021192.0236
9903.188183.40079956.356185.66629977.622177.25619988.256176.485110020.15 177.726
10030.79185.934910062.71188.266310083.99196.794510115.91198.528310147.83206.6191
10318.36199.3577 10575.2195.721710683.11198.202910835.54194.688411124.06198.2614
11422.54196.995111576.37200.629111612.32191.955811696.58202.080711721.59212.7621
11757.65221.824212093.57231.776812223.98229.602412296.57 232.209 12360.5228.5458
#Mann= 3 , 0 , 0
8333.472  0.0479       08333.472  0.0479       0 12360.5  0.0479       0
#XS Ineff= 2 , 0
       09414.675           10074       0
Bank Sta=8333.472,12360.5
Exp/Cntr=0.3,0.1

Type RM Length L Ch R = 1 ,10187.97,492.247800,492.247800,492.247800
XS GIS Cut Line= 6
797790.892255405800261.177294641798253.655501908799339.671309446
798747.769219188798439.548026397799093.542269592797262.188180865
799226.754162439796950.354543776799390.647491661796655.018182725
#Sta/Elev= 30
8381.504205.96578645.712202.64738748.524204.41959002.904197.39659819.321188.4111
9903.181 183.0149958.601183.06769981.814176.063710004.98176.014810028.06178.1122
10051.14194.224110074.22197.565410368.39 198.26910690.03193.830110877.06196.0749
11062.36190.759711340.71193.527711375.23196.112911538.75190.540211570.42 197.884
11654.89199.210111676.14190.109911686.89 188.83511772.89203.206611881.49207.6987
11903.49211.5817 11925.5222.460511947.51224.886612241.06229.3802 12345.5225.9546
#Mann= 3 , 0 , 0
8381.504  0.0447       08381.504  0.0447       0 12345.5  0.0447       0
#XS Ineff= 2 , 0
       09325.117        10083.73       0
Bank Sta=8381.504,12345.5
Exp/Cntr=0.3,0.1

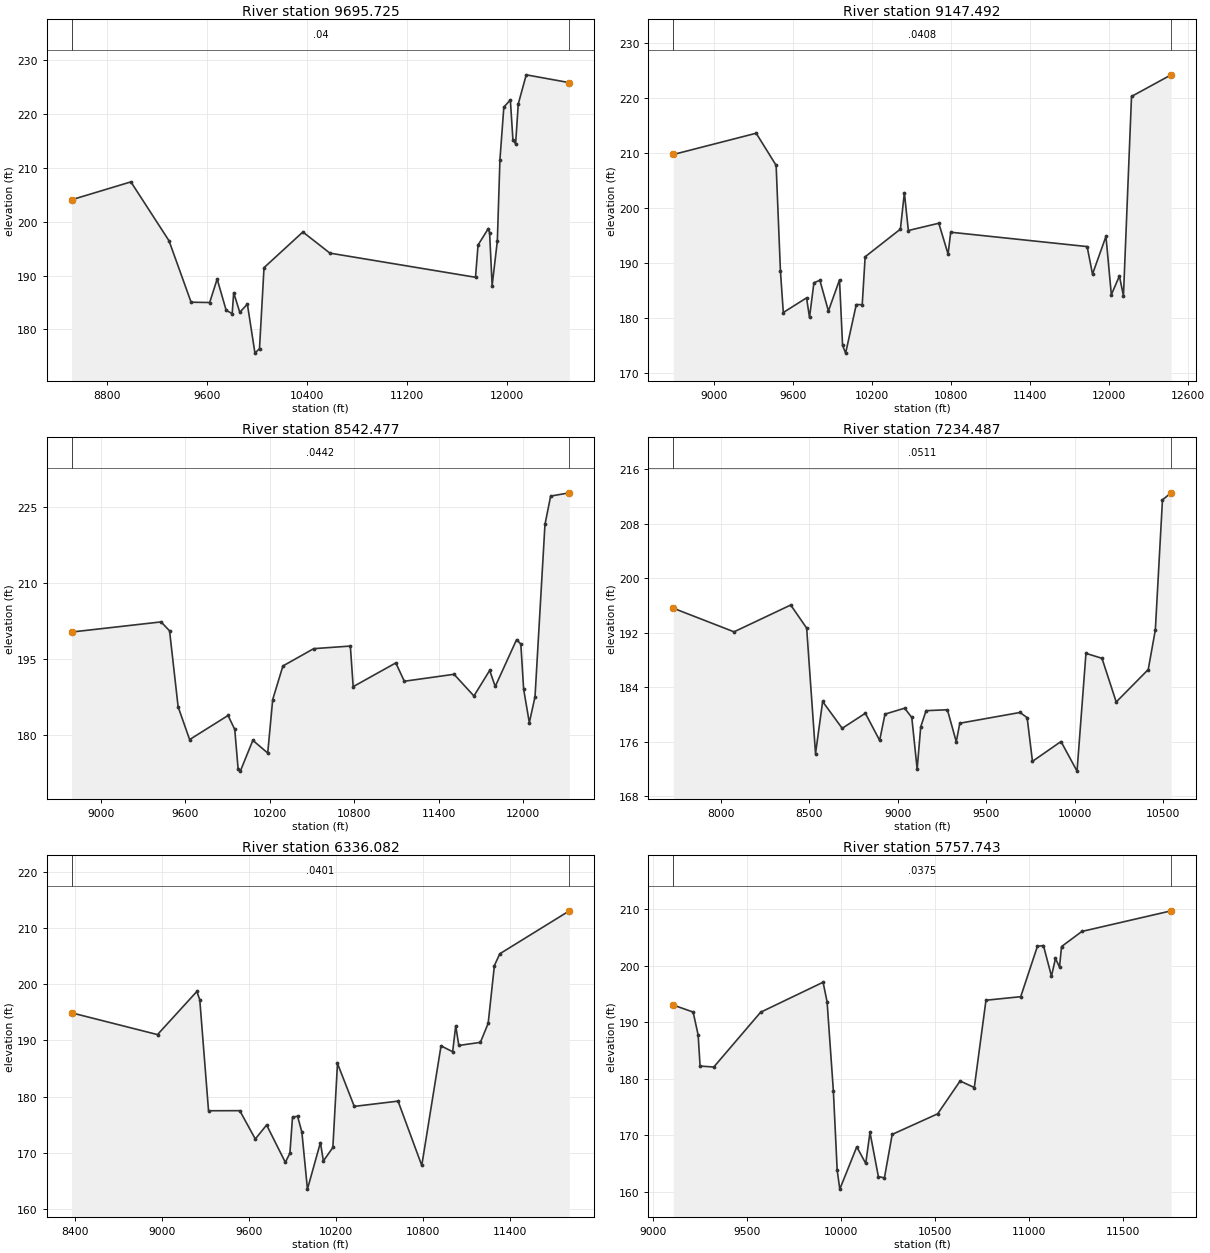
Type RM Length L Ch R = 1 ,9695.725,548.233000,548.233000,548.233000
XS GIS Cut Line= 6
798229.317459597800391.563972465798580.049425973799690.001347762
799055.543877535798944.565982137799158.990210555798714.491631138
799250.000940837797420.693132081799499.618905452796710.059866225
#Sta/Elev= 30
8518.164204.04178992.376207.3598 9296.95196.44779473.548185.05539622.116184.9993
9681.821189.35279753.468183.58269801.848182.92999813.989186.81419862.552183.1856
9923.257184.70639983.961175.618310020.21176.454810056.32191.460710366.94 198.073
 10582.9194.154111746.49189.675411766.96 195.66211848.85198.709911859.08197.9305
11879.56188.139411921.01196.410611941.81211.492811973.01221.227512025.01222.5431
12045.83 215.08112067.07214.419512088.31221.806912152.02 227.201 12496.6225.7516
#Mann= 3 , 0 , 0
8518.164    0.04       08518.164    0.04       0 12496.6    0.04       0
#XS Ineff= 2 , 0
       0                10091.81       0
Bank Sta=8518.164,12496.6
Exp/Cntr=0.3,0.1

Type RM Length L Ch R = 1 ,9147.492,605.015100,605.015100,605.015100
XS GIS Cut Line= 6
798887.509198555800600.629669302799188.455024148799838.016283601
799515.319774432799181.000965482799525.566477525799030.749121894
799453.984869182798261.379352406  799710.9293136796990.546019077
#Sta/Elev= 30
8694.271209.75919322.709213.6286 9474.03207.78519506.592188.59039528.453181.0015
9704.849183.66989727.127180.10559760.544186.4177 9805.84186.86459870.602181.2773
9954.836186.94519977.983175.010910001.13173.609910081.88182.448310126.99182.4261
10149.22191.147210416.51 196.17410446.71202.794410476.84195.9241 10707.8197.2475
10778.09191.641110798.17195.613411832.81192.999811873.62187.985411975.64194.8517
12016.45184.243112077.66187.654212108.27184.026212169.49220.3213 12469.9224.2564
#Mann= 3 , 0 , 0
8694.271  0.0408       08694.271  0.0408       0 12469.9  0.0408       0
#XS Ineff= 2 , 0
       0                 10238.5       0
Bank Sta=8694.271,12469.9
Exp/Cntr=0.3,0.1

Type RM Length L Ch R = 1 ,8542.477,1307.990700,1307.990700,1307.990700
XS GIS Cut Line= 6
800088.736132581 800558.67712174800120.859197654800105.613362743
800079.660039899799740.839674657799941.401810336799348.185584806
799658.346029891798853.283732585799891.484869152797143.323796868
#Sta/Elev= 30
8792.742 200.3539428.481202.34729488.971 200.5979549.842 185.6329631.461179.1836
9904.443183.92759952.125181.17629976.049173.39149991.787172.972110080.62179.0354
10186.31176.537110221.78187.065510294.16193.671610513.03197.083110773.22197.5932
 10793.4189.601811096.18194.275711156.73190.668511509.97192.037311651.27187.7692
11762.99192.795911802.65189.639311954.04198.848911984.32197.9916 12004.5 189.082
12044.87182.503412085.24187.616212155.89221.537812196.26227.120712329.16227.7597
#Mann= 3 , 0 , 0
8792.742  0.0442       08792.742  0.0442       012329.16  0.0442       0
#XS Ineff= 2 , 0
       0                 10349.1       0
Bank Sta=8792.742,12329.16
Exp/Cntr=0.3,0.1

Type RM Length L Ch R = 1 ,7234.487,898.404600,898.404600,898.404600
XS GIS Cut Line= 6
800523.428066332800595.870162459800564.054536469800206.614303616
800565.386125011799891.126528186800472.432526068799043.584621893
800468.220842256 798819.52821761800569.126642659797796.394737451
#Sta/Elev= 30
7731.818195.61368074.876192.14668395.064196.08628485.176192.69258535.289174.2367
8575.378181.90738685.907177.96598816.766180.17918897.512 176.1928927.791180.0542
9038.817180.92439079.189179.56149109.469171.97859129.656178.17889159.905180.5589
9280.411180.69319330.488175.99519350.502178.71449690.812 180.2969730.937179.5313
9761.031173.11119922.214176.0277 10012.9 171.67510063.25188.982210153.76188.2544
10234.17181.835610415.08 186.60110455.29192.431410495.53211.534810544.46212.5706
#Mann= 3 , 0 , 0
7731.818  0.0511       07731.818  0.0511       010544.46  0.0511       0
#XS Ineff= 2 , 0
       0                10108.53       0
Bank Sta=7731.818,10544.46
Exp/Cntr=0.3,0.1

Type RM Length L Ch R = 1 ,6336.082,578.338700,578.338700,578.338700
XS GIS Cut Line= 6
800589.201633113800592.216075416800710.215246862799648.881583077
800765.027752305799419.253637673801027.195253566798931.351515121
801345.697997931797930.015203401801606.076659689797344.874746866
#Sta/Elev= 30
8373.346 194.9148966.472191.04699237.956198.70889258.122197.2399 9318.62177.5185
9534.241177.5329 9641.36172.49569719.377174.99069848.732168.34649880.154169.9902
9898.145 176.3799932.939176.54699962.746173.720710001.08163.5957 10090.7171.8614
10111.21168.600410176.53170.994910208.43185.921210324.31178.292610626.48179.2295
10790.04167.799710922.97189.0424 11003.2188.000811024.43192.609111045.67189.1184
 11194.6189.664811248.27193.042911291.25203.3107 11328.5205.402111808.55213.0311
#Mann= 3 , 0 , 0
8373.346  0.0401       08373.346  0.0401       011808.55  0.0401       0
#XS Ineff= 2 , 0
       0                10817.47       0
Bank Sta=8373.346,11808.55
Exp/Cntr=0.3,0.1

Type RM Length L Ch R = 1 ,5757.743,984.495500,984.495500,984.495500
XS GIS Cut Line= 6
801245.651535779799851.657130212801453.030648381799136.675615937
801272.149303436798797.762439936 801271.84635058798528.118708745
801414.663889468798023.734008551801700.215598196797374.711131737
#Sta/Elev= 30
9108.457193.01899213.813191.78889240.335 187.7589250.747 182.2489323.632182.0835
9572.792191.76229904.619197.05289925.947193.60129959.253177.91419979.667 163.843
9993.551160.5168 10083.8167.988610131.44165.050510153.99170.536810198.54162.7435
 10230.7162.500410272.05170.181710513.72173.815810633.17 179.61610708.57178.4572
10770.69193.876110955.39194.501911044.11203.397211076.13203.538811118.83198.1342
11140.19201.253811161.61199.728311172.42203.357811280.43206.022811754.99209.6644
#Mann= 3 , 0 , 0
9108.457  0.0375       09108.457  0.0375       011754.99  0.0375       0
#XS Ineff= 2 , 0
       0                10788.79       0
Bank Sta=9108.457,11754.99
Exp/Cntr=0.3,0.1

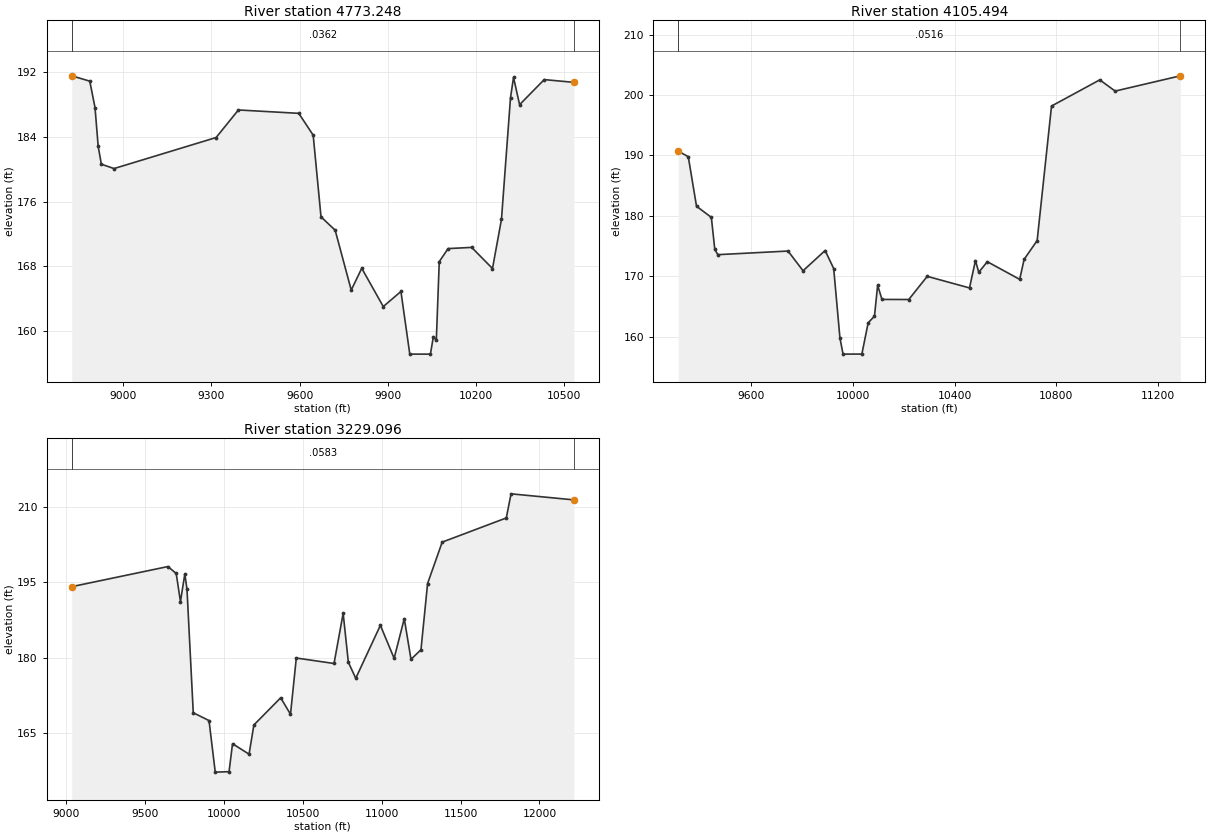
Type RM Length L Ch R = 1 ,4773.248,667.753300,667.753300,667.753300
XS GIS Cut Line= 6
801342.535236358799938.544752889801713.804557515799066.836836303
801802.543688578 799030.36858191801994.171080927799039.362149341
 802166.86005089799027.553224721802449.130781411 798943.97540632
#Sta/Elev= 30
8825.219191.56018886.463190.90018904.274187.63298915.023182.84078925.773180.6352
8968.932180.09559315.937183.93149391.809187.33939596.971186.92319646.002184.2263
9672.611 174.1239720.769172.47259775.368165.06659811.146167.76499884.314163.0315
9944.369164.89639974.459157.151910044.63157.151910054.65159.317810064.67158.8731
10074.67 168.58610104.67170.199810184.84170.348310255.63 167.73710286.18173.8101
10316.91188.862110327.21191.3609 10347.8187.992310431.47191.093710532.26190.7526
#Mann= 3 , 0 , 0
8825.219  0.0362       08825.219  0.0362       010532.26  0.0362       0
#XS Ineff= 2 , 0
       0                               0
Bank Sta=8825.219,10532.26
Exp/Cntr=0.3,0.1

Type RM Length L Ch R = 1 ,4105.494,876.398900,876.398900,876.398900
XS GIS Cut Line= 6
801445.028524458800046.771191612801859.900780857799796.743488088
802249.551060647799523.462093472802513.894061804799358.221145555
802829.169665843799191.403941944803150.060361564799065.333898276
#Sta/Elev= 30
9312.945190.7182 9352.45 189.7969384.815181.60939443.178179.75979456.719174.4601
9468.703173.59989744.702174.19889803.789170.9364 9890.51174.28659924.237 171.307
9948.823159.80019961.116157.151910035.07157.166310059.81162.334510084.55163.4199
10097.09168.531410114.07166.197210219.48166.183410292.02170.0121 10458.3168.0997
10481.65172.621310494.73170.684610528.34172.437510655.63169.514410673.15172.8329
 10724.3175.927910780.77198.172910970.53202.503211030.99200.649111287.24 203.172
#Mann= 3 , 0 , 0
9312.945  0.0516       09312.945  0.0516       011287.24  0.0516       0
#XS Ineff= 2 , 0
       09801.006                       0
Bank Sta=9312.945,11287.24
Exp/Cntr=0.3,0.1

Type RM Length L Ch R = 1 ,3229.096,0.000000,0.000000,0.000000
XS GIS Cut Line= 6
801996.851475401800805.263690455802505.136904145800446.914290616
802961.299465369799992.544086835803439.440023092 799684.60723884
804006.564284614799482.629285382804742.349238321799454.355958845
#Sta/Elev= 30
9036.532194.12439645.936 198.1339698.385196.74799725.287191.13259752.889 196.671
 9766.69193.57449806.372168.98919906.234167.42789945.633157.151910033.21157.2404
 10055.2162.818910159.97160.727810190.53166.553610360.34171.968910422.48168.6888
10459.33179.899310698.41178.807210756.16188.796710789.14 179.05110835.99175.8574
10992.03186.414111079.24179.835711143.41 187.74411186.15179.633211249.32181.5542
11291.22194.746611383.77202.999911790.01207.8216 11820.1212.629112217.99 211.421
#Mann= 3 , 0 , 0
9036.532  0.0583       09036.532  0.0583       012217.99  0.0583       0
#XS Ineff= 2 , 0
       0                               0
Bank Sta=9036.532,12217.99
Exp/Cntr=0.3,0.1